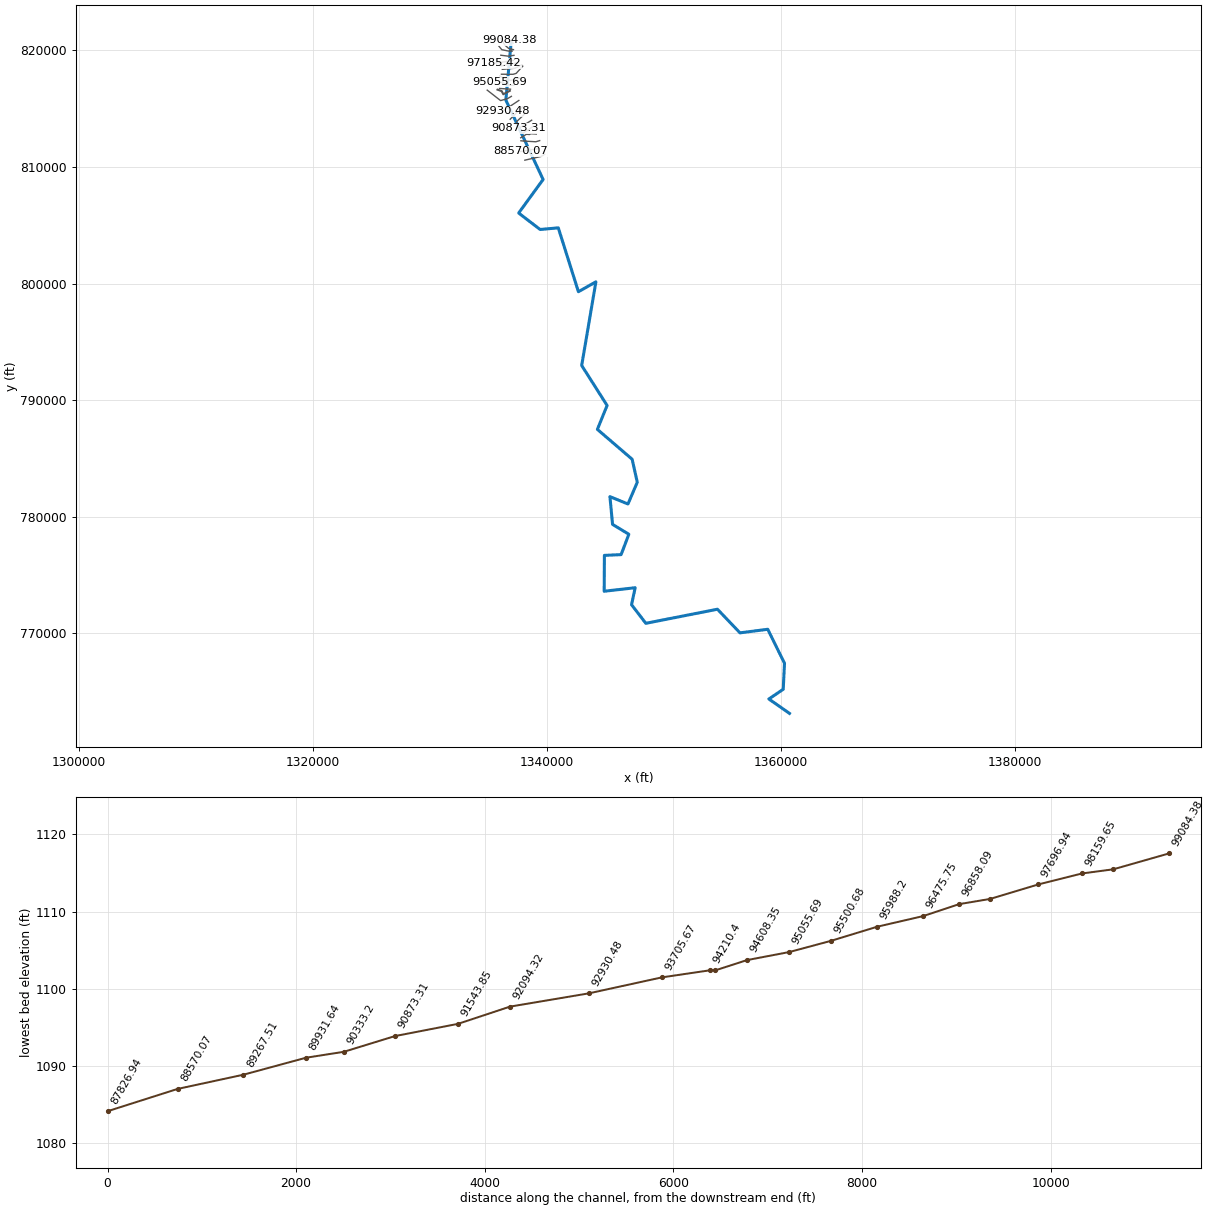
--- LLRiver.prj (project) ---

Proj Title=LLRiver
Current Plan=p01
Default Exp/Contr=0.3,0.1
English Units
Geom File=g01
Flow File=f01
Plan File=p01
Y Axis Title=Elevation
X Axis Title(PF)=Main Channel Distance
X Axis Title(XS)=Station
BEGIN DESCRIPTION:
END DESCRIPTION:
DSS Export Rating Curves= 0
DSS Export Rating Curve Sorted= 0
DSS Export Volume Flow Curves= 0
DXF OffsetX= 0
DXF OffsetY= 0
DXF ScaleX= 1
DXF ScaleY= 10

--- LLRiver.p01 (plan) ---

Plan Title=Approximate Study - 100 YR
Program Version=3.12
Short Identifier=100 Yr
Geom File=g01
Flow File=f01
Subcritical Flow
K Sum by GR= 0
Std Step Tol= 0.01
Critical Tol= 0.01
Num of Std Step Trials= 20
Max Error Tol= 0.3
Flow Tol Ratio= 0.001
Split Flow NTrial= 30
Split Flow Tol= 0.02
Split Flow Ratio= 0.02
Log Output Level= 0
Friction Slope Method= 1
Unsteady Friction Slope Method= 2
Unsteady Bridges Friction Slope Method= 1
Calc Critical at every XS
Parabolic Critical Depth
Global Vel Dist= 0 , 0 , 0
Global Log Level= 0
CheckData=True
Encroach Param=-1 ,10,10, 2
Encroach River=LLRiver
Encroach Reach=Main
Encroach Node=99084.38
       1     140  243.46
Encroach Node=98492.18
       1     548   617.3
Encroach Node=98159.65
       1  529.15  591.26
Encroach Node=97696.94
       1  687.67  800.44
Encroach Node=97185.42
       1  512.23  585.33
Encroach Node=96858.09
       1  644.79  915.13
Encroach Node=96475.75
       1 1020.45 1122.86
Encroach Node=95988.2
       1 1121.55 1539.69
Encroach Node=95500.68
       1 1078.73  1309.9
Encroach Node=95055.69
       1  584.97  827.48
Encroach Node=94608.35
       1  413.16   504.6
Encroach Node=94271.8
       1     372     552
Encroach Node=94210.4
       1     392     575
Encroach Node=93705.67
       1  515.63  586.42
Encroach Node=92930.48
       1  821.15 1050.54
Encroach Node=92094.32
       1  690.48  909.01
Encroach Node=91543.85
       1  624.12  762.49
Encroach Node=90873.31
       1     715     900
Encroach Node=90333.2
       1  497.21  645.65
Encroach Node=89931.64
       1     510     585
Encroach Node=89267.51
       1     640   779.5
Encroach Node=88570.07
       1  515.77  707.36
Encroach Node=87826.94
       1  612.53 1173.68
Encroach Node=87088.61
       1  572.36 1148.58
Encroach Node=86498
       1 1560.39 1761.56
Encroach Node=85811.69
       1 1755.08 2304.49
Encroach Node=84888.8
       1  689.59  890.37
Encroach Node=84196.41
       1  588.66 1051.69
Encroach Node=83334.55
       1  586.93  1005.8
Encroach Node=82742.48
       1    1040    1400
Encroach Node=82670.82
       1    1110    1460
Encroach Node=82232.19
       1 1218.35    1700
Encroach Node=81753.66
       1 1188.84 1654.47
Encroach Node=80996.22
       1  749.07    1077
Encroach Node=80481.09
       1  814.19 1020.33
Encroach Node=79685.4
       1 1475.69 1606.84
Encroach Node=79194.89
       1     860 1056.28
Encroach Node=78551.31
       1  399.67  504.24
Encroach Node=78183.5
       1  715.93  981.33
Encroach Node=77219.9
       1     850     937
Encroach Node=76445.27
       1 1076.78 1680.55
Encroach Node=75700.84
       1     740  973.03
Encroach Node=75065.88
       1  876.08  1005.4
Encroach Node=74421.02
       1    1070    1439
Encroach Node=74121.7
       1   454.2     595
Encroach Node=74049.85
       1   494.7   585.6
Encroach Node=73440.36
       1     515     630
Encroach Node=72629.91
       1     510     710
Encroach Node=71794.91
       1     690     888
Encroach Node=71030.09
       1  761.83   859.5
Encroach Node=70551.2
       1  915.04 1012.83
Encroach Node=69759.98
       1  805.54     902
Encroach Node=69119.31
       1  558.53 1197.59
Encroach Node=68458.35
       1   753.8  1660.2
Encroach Node=68039.74
       1 1128.58 2129.95
Encroach Node=67400.32
       1  904.17 1176.92
Encroach Node=66656.75
       1  528.01  680.39
Encroach Node=66042.48
       1  485.55  602.02
Encroach Node=65453.34
       1  413.14     600
Encroach Node=65002.5
       1     472     621
Encroach Node=64851.52
       1   530.7   625.5
Encroach Node=64389.92
       1  822.43 1048.92
Encroach Node=63698.22
       1  406.98  542.38
Encroach Node=63065.05
       1   511.1  643.59
Encroach Node=62753.43
       1  802.15  991.57
Encroach Node=62436.14
       1  783.48 1015.77
Encroach Node=61845.46
       1  477.39  642.48
Encroach Node=61170.81
       1 1269.46    1500
Encroach Node=60755.43
       1  332.98  468.63
Encroach Node=60189.41
       1     260  510.54
Encroach Node=59712.13
       1     520     708
Encroach Node=59221.69
       1     279     530
Encroach Node=58821.36
       1     230     600
Encroach Node=58677.35
       1     215   535.5
Encroach Node=58607.33
       1     230     436
Encroach Node=58409.68
       1  610.74  767.14
Encroach Node=58009.9
       1  773.19  965.33
Encroach Node=57445.01
       1  491.05  625.07
Encroach Node=57062.48
       1  573.34  764.08
Encroach Node=56402.48
       1    1430    1617
Encroach Node=55851.19
       1     484     700
Encroach Node=55458.08
       1     320     560
Encroach Node=55177.21
       1  370.89     640
Encroach Node=54934.79
       1     304  445.12
Encroach Node=54837.49
       1     281     425
Encroach Node=54368.96
       1     555     665
Encroach Node=54212.71
       1     238     380
Encroach Node=54133.48
       1  227.79     390
Encroach Node=53822.24
       1  478.23  632.28
Encroach Node=53296.6
       1  468.07  577.91
Encroach Node=52979.47
       1  697.93  805.19
Encroach Node=52692.6
       1  386.49  502.23
Encroach Node=52314.24
       1  508.58  612.59
Encroach Node=51877.12
       1  283.26   387.3
Encroach Node=51398.48
       1  297.21  408.68
Encroach Node=50825.34
       1  468.56  590.06
Encroach Node=50142.73
       1  563.23  707.28
Encroach Node=49882.96
       1  567.47  696.55
Encroach Node=49393.18
       1  272.01  396.51
Encroach Node=48784.89
       1     300  401.28
Encroach Node=48197.71
       1    1005 1105.98
Encroach Node=47523.66
       1 1350.45 1484.48
Encroach Node=47097.3
       1  348.73  476.64
Encroach Node=46624.41
       1  233.72  338.72
Encroach Node=46103.19
       1  270.75  382.45
Encroach Node=45555.62
       1  239.47     372
Encroach Node=45145.86
       1  408.83     535
Encroach Node=44530.54
       1     317   510.8
Encroach Node=43879.7
       1  360.23  476.93
Encroach Node=43283.79
       1  183.18  297.69
Encroach Node=42785.54
       1  230.62  339.19
Encroach Node=42072.73
       1  376.22     490
Encroach Node=41397.03
       1  227.87  346.21
Encroach Node=40971.53
       1  307.39  418.68
Encroach Node=40389.46
       1  420.62  535.95
Encroach Node=39872.48
       1  331.91   462.3
Encroach Node=39242.98
       1     490  648.02
Encroach Node=38439.94
       1  316.83  438.46
Encroach Node=37936.26
       1  592.28  735.72
Encroach Node=37326.35
       1     701  795.34
Encroach Node=36791.02
       1  242.67  354.29
Encroach Node=36380.56
       1  400.61  513.43
Encroach Node=35945.4
       1    1000 1227.32
Encroach Node=35345.63
       1  375.55     500
Encroach Node=35122.61
       1     180   480.8
Encroach Node=35030.04
       1  231.17   421.1
Encroach Node=34810
       1  166.65  323.16
Encroach Node=34480.51
       1  143.38  303.43
Encroach Node=34052.09
       1  234.29  363.79
Encroach Node=33710.5
       1  308.48     433
Encroach Node=33635.15
       1  294.16  425.15
Encroach Node=33114.68
       1     270  424.18
Encroach Node=32563.21
       1  413.78     523
Encroach Node=31974.6
       1  403.72   536.5
Encroach Node=31338.41
       1   251.4     353
Encroach Node=30869.31
       1  399.59  548.42
Encroach Node=30431.74
       1  349.27  514.91
Encroach Node=30013.16
       1     514  636.51
Encroach Node=29529.03
       1  302.81  428.73
Encroach Node=29115.97
       1  195.95  379.05
Encroach Node=28634.85
       1  347.09  539.64
Encroach Node=28097.57
       1  455.55  587.22
Encroach Node=27683.78
       1  484.42  634.69
Encroach Node=27367.52
       1  950.16  1067.1
Encroach Node=26882.19
       1  980.02 1118.08
Encroach Node=26507.24
       1     190  338.56
Encroach Node=26131.77
       1  221.14  380.51
Encroach Node=25742.39
       1  278.13  572.11
Encroach Node=25387.64
       1 1570.99    1737
Encroach Node=24770.15
       1  815.62    1055
Encroach Node=24177.52
       1  231.13  417.15
Encroach Node=23588.01
       1   417.3  601.68
Encroach Node=23056.59
       1  477.12  687.47
Encroach Node=22396.97
       1   437.1  689.76
Encroach Node=21531.94
       1  360.06  887.46
Encroach Node=20886.65
       1  435.52  879.44
Encroach Node=20198.98
       1  578.51 1203.87
Encroach Node=19603.18
       1  967.12 1200.76
Encroach Node=19014.58
       1  661.91  887.63
Encroach Node=18408.37
       1  421.78  590.27
Encroach Node=17825.83
       1  588.58  777.23
Encroach Node=17467.48
       1   447.6  695.09
Encroach Node=17373.09
       1     533  780.65
Encroach Node=17174.94
       1     760  974.09
Encroach Node=16939.65
       1     710     976
Encroach Node=16852
       1  831.51 1003.87
Encroach Node=16560.48
       1  909.89    1029
Encroach Node=15981.74
       1  965.15    1086
Encroach Node=15507.29
       1  419.88  544.77
Encroach Node=14978.21
       1     349  489.77
Encroach Node=14480.72
       1     300     482
Encroach Node=13948.01
       1     200     370
Encroach Node=13631.96
       1     340     570
Encroach Node=13484.05
       1   257.8   507.5
Encroach Node=13403.52
       1     325     480
Encroach Node=13209.58
       1  334.39  560.78
Encroach Node=12956.46
       1  223.46  336.72
Encroach Node=12386.51
       1   331.4     459
Encroach Node=12035.67
       1     210     351
Encroach Node=11743.97
       1  320.74  443.11
Encroach Node=11207.88
       1   339.4   437.3
Encroach Node=10664.72
       1  414.11  543.62
Encroach Node=10129.35
       1  276.02  400.31
Encroach Node=9677.736
       1  515.21  625.19
Encroach Node=9147.043
       1  376.24  518.68
Encroach Node=8628.687
       1  831.22  986.89
Encroach Node=8089.837
       1  767.29   887.5
Encroach Node=7475.167
       1  468.98  633.64
Encroach Node=6811.548
       1 1644.75    1775
Encroach Node=6084.145
       1    1641 1778.07
Encroach Node=5481.847
       1  402.34  521.92
Encroach Node=4895.775
       1  405.46     527
Encroach Node=4384.168
       1  671.64   785.2
Encroach Node=3782.596
       1     523  636.52
Encroach Node=3165.187
       1  409.88     529
Encroach Node=2536.28
       1  538.77  666.58
Encroach Node=1994.362
       1     330     457
Encroach Node=1465.37
       1  427.31  556.61
Encroach Node=999.68
       1  439.82   576.7
Encroach Node=636.094
       1  511.69     700
Computation Interval=1HOUR
Output Interval=1HOUR
Run HTab= 0
Run UNet= 0
Run PostProcess= 0
UNET Theta= 1
UNET Theta Warmup= 1
UNET ZTol= 0.02
UNET ZSATol= 0.05
UNET MxIter= 20
UNET MaxInSteps= 0
UNET DtIC= 0
UNET DtMin= 0
UNET MaxCRTS= 20
UNET WFStab= 2
UNET SFStab= 1
UNET WFX= 1
UNET SFX= 1
UNET DSS MLevel= 4
UNET DZMax Abort= 100
UNET Convert EG Bridges=-1
UNET Use Existing IB Tables=-1
UNET Froude Reduction=False
UNET Froude Limit= 1
UNET Froude Power= 10
Instantaneous Interval=1HOUR
Write IC File= 0
Echo Input=False
Echo Output=False
Write Detailed= 0
Detailed Automatic Start=False, 10

--- LLRiver.f01 (steady flow) ---

Flow Title=LLRiver
Program Version=3.12
Number of Profiles= 2
Profile Names=P100yr,Encr
River Rch & RM=LLRiver,Main            ,99084.38
    4640    4640
River Rch & RM=LLRiver,Main            ,94608.35
    5140    5140
River Rch & RM=LLRiver,Main            ,86498
    7870    7870
River Rch & RM=LLRiver,Main            ,82232.19
    9750    9750
River Rch & RM=LLRiver,Main            ,68039.74
   12400   12400
River Rch & RM=LLRiver,Main            ,48197.71
   13900   13900
River Rch & RM=LLRiver,Main            ,16560.48
   15700   15700
Boundary for River Rch & Prof#=LLRiver,Main            , 1
Up Type= 0
Dn Type= 3
Dn Slope=0.002945
DSS Import GetInterval= 0
DSS Import GetPeak= 0
DSS Import FillOption= 0

--- LLRiver.g01 (geometry) ---

Geom Title=USGS 10m DEM
Program Version=3.12

River Reach=LLRiver         ,Main
Reach XY= 30
  1336940.446444   820763.029386  1336484.000876   815743.561605
  1339668.251759   808930.058111  1337578.878061   806050.631548
   1339411.62507   804638.191483    1340966.1308   804778.999675
  1342687.130098   799299.060086  1344180.880499   800146.751351
  1342966.129778    792966.99992  1345137.628276   789539.004269
  1344308.130931   787486.248811  1347278.750838   784922.128232
  1347716.879478   782950.440807  1346920.498549   781084.880869
  1345380.128372   781714.560741  1345603.499636   779337.939811
   1346996.13503   778483.998562  1346334.381173   776739.749729
  1344907.129972   776675.630945  1344889.750644   773597.630302
   1347536.49983   773899.059038  1347228.128374   772438.880093
  1348447.630327   770845.310811  1354569.000061   772054.310748
  1356495.131774   770027.749211  1358868.128897   770332.561243
  1360300.381314    767418.99452  1360190.751874   765181.689686
  1358962.381953   764352.560981   1360723.13037   763117.879636

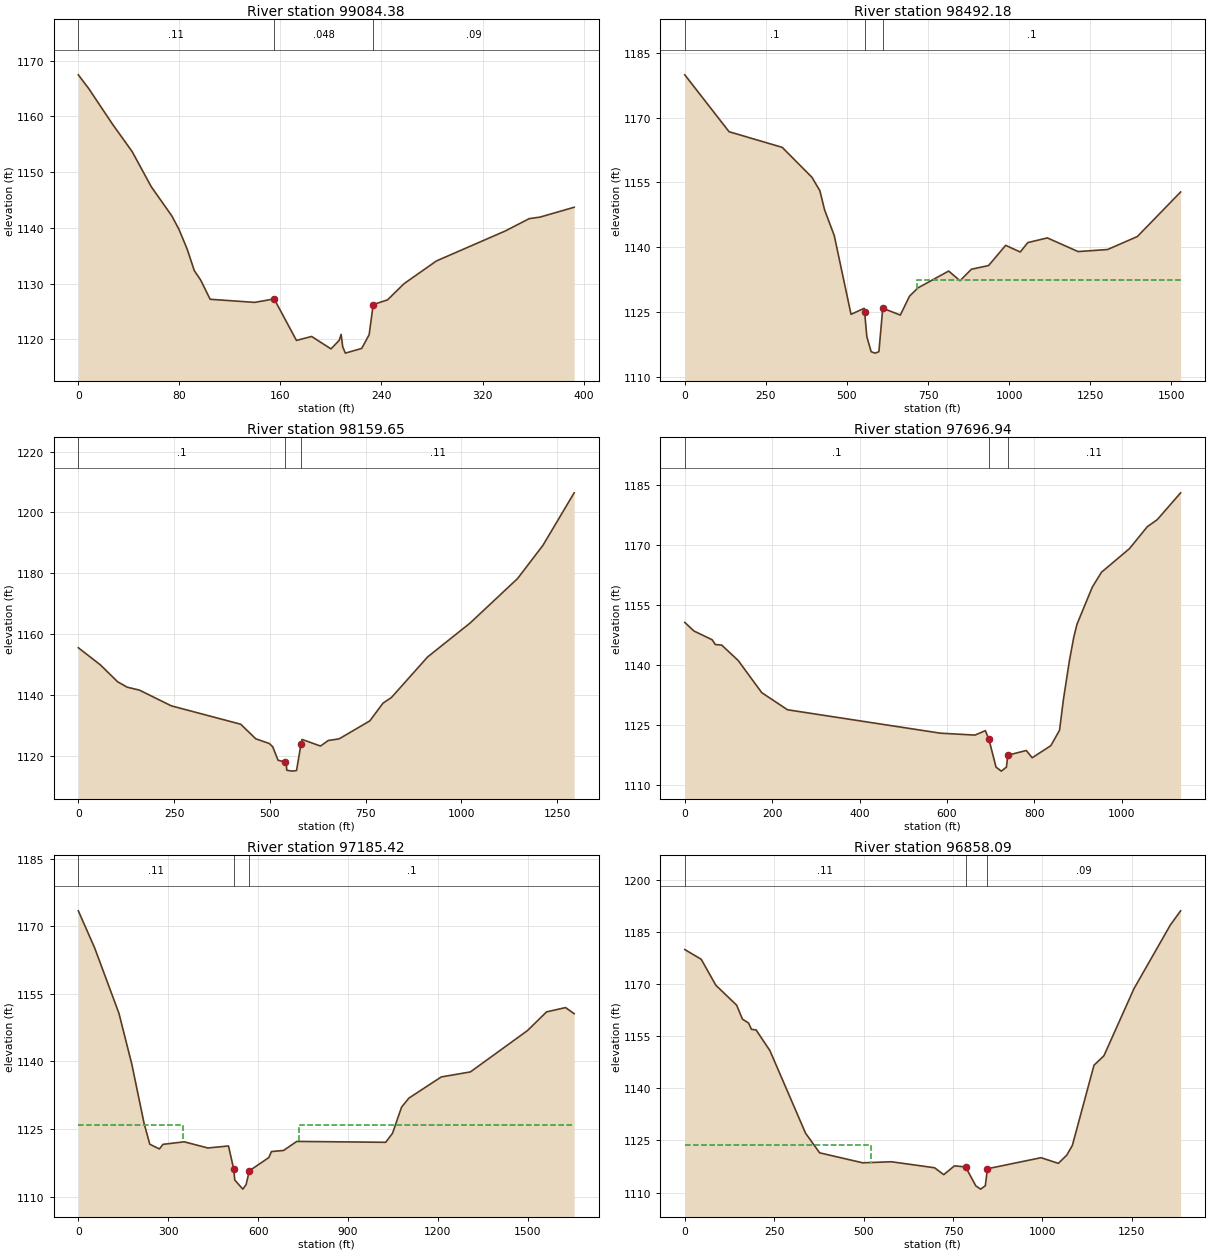
Type RM Length L Ch R = 1 ,99084.38,592.19,592.19,702.48
XS GIS Cut Line= 2
  1337103.556076    820636.10945  1336782.803948   820862.455818
#Sta/Elev= 30
       0 1167.46    8.22    1165   26.95 1158.65    42.6  1153.7   57.73  1147.4
   74.06 1142.15   79.71 1139.73   86.15 1136.22   91.85 1132.34   96.88 1130.65
  104.36 1127.21  139.56 1126.65  155.06 1127.27   172.7 1119.83  184.72 1120.54
  200.04 1118.31  206.53 1119.84  208.06 1120.91  209.33  1118.7  211.39 1117.55
  224.35 1118.39  230.25 1120.85  233.46 1126.26   244.8  1127.1  257.92 1130.01
  283.51 1134.08  338.07 1139.46     357 1141.67  365.47 1141.94  392.57 1143.71
#Mann= 3 , 0 , 0
       0     .11       0  155.06    .048       0  233.46     .09       0
Bank Sta=155.06,233.46
Exp/Cntr=0.3,0.1

Type RM Length L Ch R = 1 ,98492.18,332.53,332.53,248.54
XS GIS Cut Line= 4
  1337133.264108   820071.990921  1336721.805804   820176.157577
  1336401.065964   820457.782537  1336055.290475   821040.141194
#Sta/Elev= 30
       0 1179.91  136.55 1166.74  300.34 1163.12  391.66 1156.22  416.44 1153.09
  430.91 1148.66  460.75  1142.7  512.49 1124.47  553.09 1125.87  554.42 1124.95
  561.19 1119.32  574.56 1115.81  586.46 1115.49  598.35 1115.81  610.29 1125.88
  664.42  1124.3  692.66 1128.66  718.57 1130.58  813.49 1134.49  848.44 1132.25
  883.63 1134.91  936.71 1135.77  989.08 1140.44 1034.11  1138.9  1057.5 1141.08
 1117.71 1142.16  1212.5    1139 1303.37 1139.47 1395.17 1142.48 1528.55 1152.79
#Mann= 3 , 0 , 0
       0      .1       0  554.42    .047       0  610.29      .1       0
#XS Ineff= 2 , 0
                          715.56          1132.5
Permanent Ineff=
       F       F
Bank Sta=554.42,610.29
Exp/Cntr=0.3,0.1

Type RM Length L Ch R = 1 ,98159.65,462.72,462.72,445.71
XS GIS Cut Line= 4
  1337034.305772   819952.199177  1336711.389164   819946.990857
  1336135.047403   820068.106121  1335893.946731   820365.292169
#Sta/Elev= 30
       0 1155.51   57.72 1149.87   102.4 1144.35  127.47 1142.55  159.32 1141.59
  242.84 1136.41  423.92 1130.37  463.29 1125.58  498.62 1124.03  507.56 1122.96
  521.45 1118.54  539.15 1117.93  543.46 1116.65  544.07 1115.37  544.86 1115.22
  559.12 1114.95  569.75 1115.15  581.26 1123.74  584.06 1125.37  632.24  1123.2
  652.46 1125.01  680.87 1125.56  760.92 1131.45  795.59 1137.31  817.51 1139.15
  911.89 1152.48 1022.87 1163.63 1146.89 1178.27 1212.87 1189.14 1294.58 1206.44
#Mann= 3 , 0 , 0
       0      .1       0  539.15    .046       0  581.26     .11       0
Bank Sta=539.15,581.26
Exp/Cntr=0.3,0.1

Type RM Length L Ch R = 1 ,97696.94,511.51,511.51,455.8
XS GIS Cut Line= 3
   1337176.66686   819578.935305  1336662.777964   819512.963081
  1336051.666923   819592.824201
#Sta/Elev= 30
       0 1150.64   20.99 1148.49    62.6 1146.31    69.8 1145.12   84.27 1144.99
  122.22 1141.13  176.07 1133.11  235.01 1128.84  584.64    1123  663.88 1122.52
  687.62 1123.63  695.85 1121.45  712.09 1114.53  724.06 1113.53   735.9 1114.52
  738.99  1117.5  781.34 1118.68  794.87 1116.87  837.45 1119.88  857.34 1123.72
  866.28 1131.42  879.85    1141   889.8 1146.87  897.28 1150.17  932.25 1159.43
   953.4 1163.16 1017.38 1169.05 1058.08 1174.51 1080.96 1176.28 1134.41 1182.97
#Mann= 3 , 0 , 0
       0      .1       0  695.85    .046       0  738.99     .11       0
Bank Sta=695.85,738.99
Exp/Cntr=0.3,0.1

Type RM Length L Ch R = 1 ,97185.42,327.34,327.34,302.07
XS GIS Cut Line= 2
  1337107.222508   819146.501384  1335471.805803   818893.029128
#Sta/Elev= 30
       0 1173.41   54.69 1165.15  135.51 1150.68  178.51 1139.38  219.27 1126.31
  238.49 1121.62  270.57 1120.57  282.68 1121.59  353.47 1122.15  432.45 1120.78
  501.22 1121.23  518.52 1116.14  522.23 1113.67  548.97 1111.65  559.95 1112.65
  570.82 1115.72  635.76 1118.65  644.67 1119.99  684.77 1120.23  729.25 1122.24
 1025.92 1122.04 1048.81 1124.06 1078.83 1129.84  1103.4 1131.85 1211.44 1136.55
 1308.59 1137.66 1499.03 1146.83 1562.73 1150.98 1626.15 1151.94 1654.94 1150.58
#Mann= 3 , 0 , 0
       0     .11       0  518.52    .046       0  570.82      .1       0
#XS Ineff= 2 , 0
          348.71 1125.95  737.27         1125.86
Permanent Ineff=
       F       F
Bank Sta=518.52,570.82
Exp/Cntr=0.3,0.1

Type RM Length L Ch R = 1 ,96858.09,382.34,382.34,404.92
XS GIS Cut Line= 2
  1337461.389165   818940.046472  1336100.277995   818676.157576
#Sta/Elev= 30
       0 1179.97   45.93 1177.17   86.83 1169.69  145.04 1163.94  161.28 1159.93
  178.23 1158.82  186.38 1156.99  199.37 1156.83  238.05 1150.86  337.58 1127.11
  377.07 1121.43  497.51 1118.56  577.93 1118.86  698.43 1117.13  724.06 1115.15
     754 1117.68  785.12 1117.38   813.8 1111.92  827.06 1110.98  840.31 1111.94
  846.29 1116.85  996.13 1120.03  1044.6  1118.4 1067.89 1120.74 1083.78 1123.58
 1144.17 1146.65 1171.96 1149.38 1255.85 1168.67 1357.64 1187.03 1386.46 1191.12
#Mann= 3 , 0 , 0
       0     .11       0  785.12    .046       0  846.29     .09       0
#XS Ineff= 2 , 0
             521  1123.8
Permanent Ineff=
       F       F
Bank Sta=785.12,846.29
Exp/Cntr=0.3,0.1

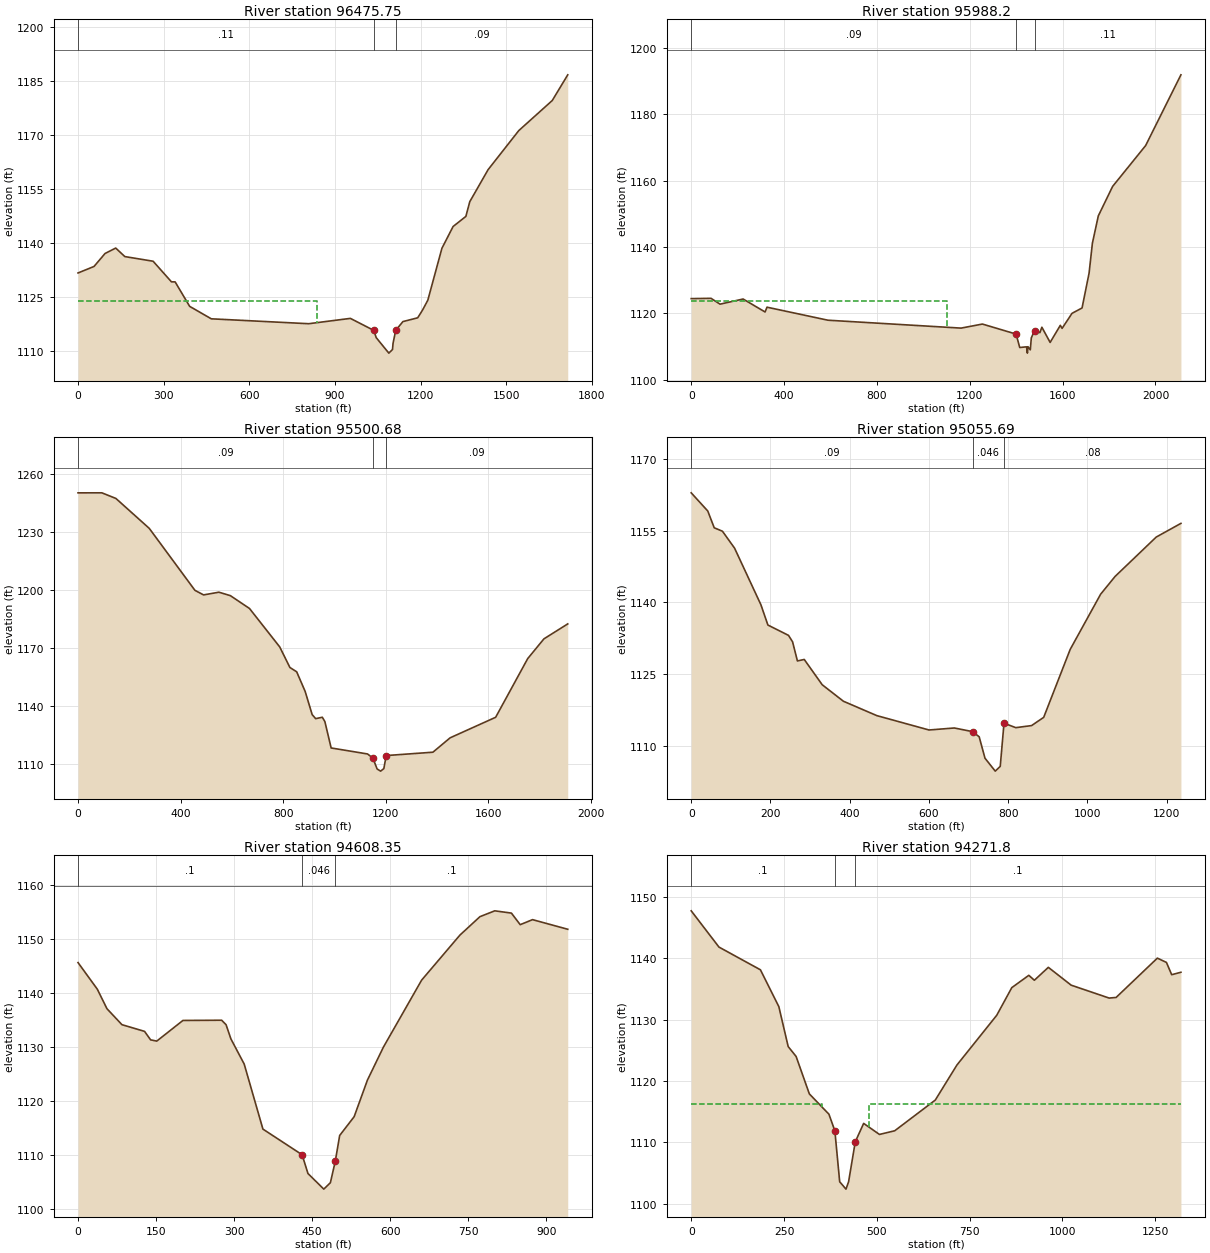
Type RM Length L Ch R = 1 ,96475.75,487.55,487.55,502.21
XS GIS Cut Line= 3
  1337824.357869   818754.818824  1337273.889132   818474.768648
  1336180.139115   818381.018632
#Sta/Elev= 30
       0 1131.67   56.07 1133.48   94.73 1137.08  132.08 1138.58  163.93 1136.22
  262.99 1134.93  327.24 1129.21  340.12  1129.2  390.99 1122.41   466.8 1118.95
  807.95 1117.59  953.98 1119.07 1036.16 1115.73 1044.45 1113.73 1088.66 1109.43
 1101.58 1110.43  1103.4 1112.15 1112.86 1115.76    1138 1118.18 1189.73 1119.23
 1206.44 1121.33 1225.21 1124.11 1274.63 1138.52 1313.75 1144.56  1358.5 1147.36
 1372.24 1151.46 1436.33 1160.33 1543.93 1171.18 1661.18 1179.53 1715.37 1186.65
#Mann= 3 , 0 , 0
       0     .11       0 1036.16    .046       0 1112.86     .09       0
#XS Ineff= 2 , 0
           836.9  1123.9
Permanent Ineff=
       F       F
Bank Sta=1036.16,1112.86
Exp/Cntr=0.3,0.1

Type RM Length L Ch R = 1 ,95988.2 ,487.51,487.51,560.84
XS GIS Cut Line= 4
  1337926.831213   818654.843784  1337367.639149   818033.796487
  1337103.750252   817953.935367  1336105.450731   817960.730375
#Sta/Elev= 30
       0 1124.48   85.46 1124.57  124.19 1122.81  223.61 1124.36  318.35 1120.45
  326.45  1121.9  589.11 1117.97 1162.54 1115.59 1254.52 1116.81 1399.68 1113.79
  1415.3 1109.74  1444.5 1109.95 1448.33 1108.05 1450.74 1109.99  1460.9 1109.04
 1465.22 1112.65 1479.25 1114.85 1502.25 1114.24 1510.69 1115.86  1546.3 1111.28
 1590.18 1116.43 1597.77 1115.51 1640.61 1120.05 1683.77 1121.66 1714.03 1132.15
 1728.35 1141.19 1753.85 1149.42 1815.62 1158.32 1957.65 1170.61 2109.73 1191.94
#Mann= 3 , 0 , 0
       0     .09       0 1399.68    .046       0 1479.25     .11       0
#XS Ineff= 2 , 0
          1102.4  1123.9
Permanent Ineff=
       F       F
Bank Sta=1399.68,1479.25
Exp/Cntr=0.3,0.1

Type RM Length L Ch R = 1 ,95500.68,445,445,437.96
XS GIS Cut Line= 3
  1337811.922541   817660.740359  1336878.055788   817426.157575
  1335992.639083   817762.963079
#Sta/Elev= 30
       0 1250.28   92.93 1250.29  147.78 1247.38  277.92 1231.88  456.05 1199.81
  489.77 1197.45  549.44 1198.85  594.32 1197.06  668.85 1190.42  786.71 1170.54
  826.46 1159.88  852.87 1157.64  885.93  1147.5  913.29 1135.48  926.99 1133.39
  952.82 1134.12  962.88 1131.87  987.32 1118.22 1129.14 1115.12 1150.04 1112.99
 1166.65 1107.34 1180.48 1106.23 1192.78 1107.54 1202.23 1114.29 1384.21 1116.02
 1451.34 1123.47 1628.99  1134.1 1753.94 1164.46 1817.29  1174.7 1910.19 1182.44
#Mann= 3 , 0 , 0
       0     .09       0 1150.04    .046       0 1202.23     .09       0
Bank Sta=1150.04,1202.23
Exp/Cntr=0.3,0.1

Type RM Length L Ch R = 1 ,95055.69,447.34,447.34,388.89
XS GIS Cut Line= 3
   1337166.25022   817006.018694  1336773.889132    817019.90759
  1335982.222443   817311.574279
#Sta/Elev= 30
       0 1162.89   41.84 1159.09    58.1 1155.59   78.88 1154.87  109.52 1151.33
  175.96 1139.52  193.62 1135.28  245.69 1133.12  255.91 1131.77  268.12 1127.78
  285.38 1128.09  330.73 1122.81  384.31 1119.36  468.68 1116.36  600.41 1113.36
  664.42 1113.78  710.24 1113.02  726.98 1111.94  741.62 1107.47  767.56 1104.77
  780.14 1105.76  789.66 1114.78  819.39 1113.85  859.24 1114.28  889.86    1116
   956.8  1130.2 1033.67 1141.73 1070.11 1145.43  1173.9 1153.65 1236.29 1156.51
#Mann= 3 , 0 , 0
       0     .09       0  710.24    .046       0  789.66     .08       0
Bank Sta=710.24,789.66
Exp/Cntr=0.3,0.1

Type RM Length L Ch R = 1 ,94608.35,336.54,336.54,223.48
XS GIS Cut Line= 2
    1336882.5907   816677.665926  1335943.172075   816739.935238
#Sta/Elev= 30
       0 1145.62   37.09  1140.7   55.62 1137.09   84.41 1134.14  127.87  1132.9
  139.58 1131.33  151.35  1131.1   201.7 1134.92  276.16 1134.96  284.61 1134.13
  293.88 1131.52  319.48 1126.85  355.45 1114.83  430.77 1110.09  442.03 1106.62
  472.51 1103.73  485.17 1104.92   494.6  1108.9  503.02 1113.65  530.88 1117.13
  556.37 1123.89  587.05 1129.98  660.61 1142.38  734.27 1150.71   772.7 1154.11
  801.16 1155.19  833.17 1154.77  850.09 1152.63  873.81 1153.56  941.48 1151.78
#Mann= 3 , 0 , 0
       0      .1       0  430.77    .046       0   494.6      .1       0
Bank Sta=430.77,494.6
Exp/Cntr=0.5,0.3

Type RM Length L Ch R = 1 ,94271.8 ,61.41,61.41,61.64
BEGIN DESCRIPTION:
Upstream xs of Bridge 37003-0006
END DESCRIPTION:
XS GIS Cut Line= 4
  1336828.071404    816571.75655  1336276.827884   816281.236358
  1336146.542059   816536.302854  1335760.277099    816673.10503
#Sta/Elev= 30
       0  1147.7  74.801  1141.8 186.499  1138.1   236.1  1132.1   261.3  1125.6
 282.599    1124   318.3  1117.9 371.001  1114.6     387  1111.9     400  1103.6
 417.001  1102.4     424  1103.6     442  1110.1   464.6  1113.1 507.201  1111.3
   548.3  1111.9 657.599  1116.9   715.8  1122.6 823.101  1130.7   863.7  1135.2
 909.501  1137.2   924.5  1136.4 962.099  1138.51023.599  1135.61125.901  1133.5
  1144.7  1133.6  1255.8    1140  1280.3  1139.3  1294.4  1137.3  1319.3  1137.7
#Mann= 3 , 0 , 0
       0      .1       0     387    .046       0     442      .1       0
#XS Ineff= 2 , 0
       0 351.699  1116.2   478.3       0  1116.2
Permanent Ineff=
       F       F
Bank Sta=387,442
Exp/Cntr=0.5,0.3

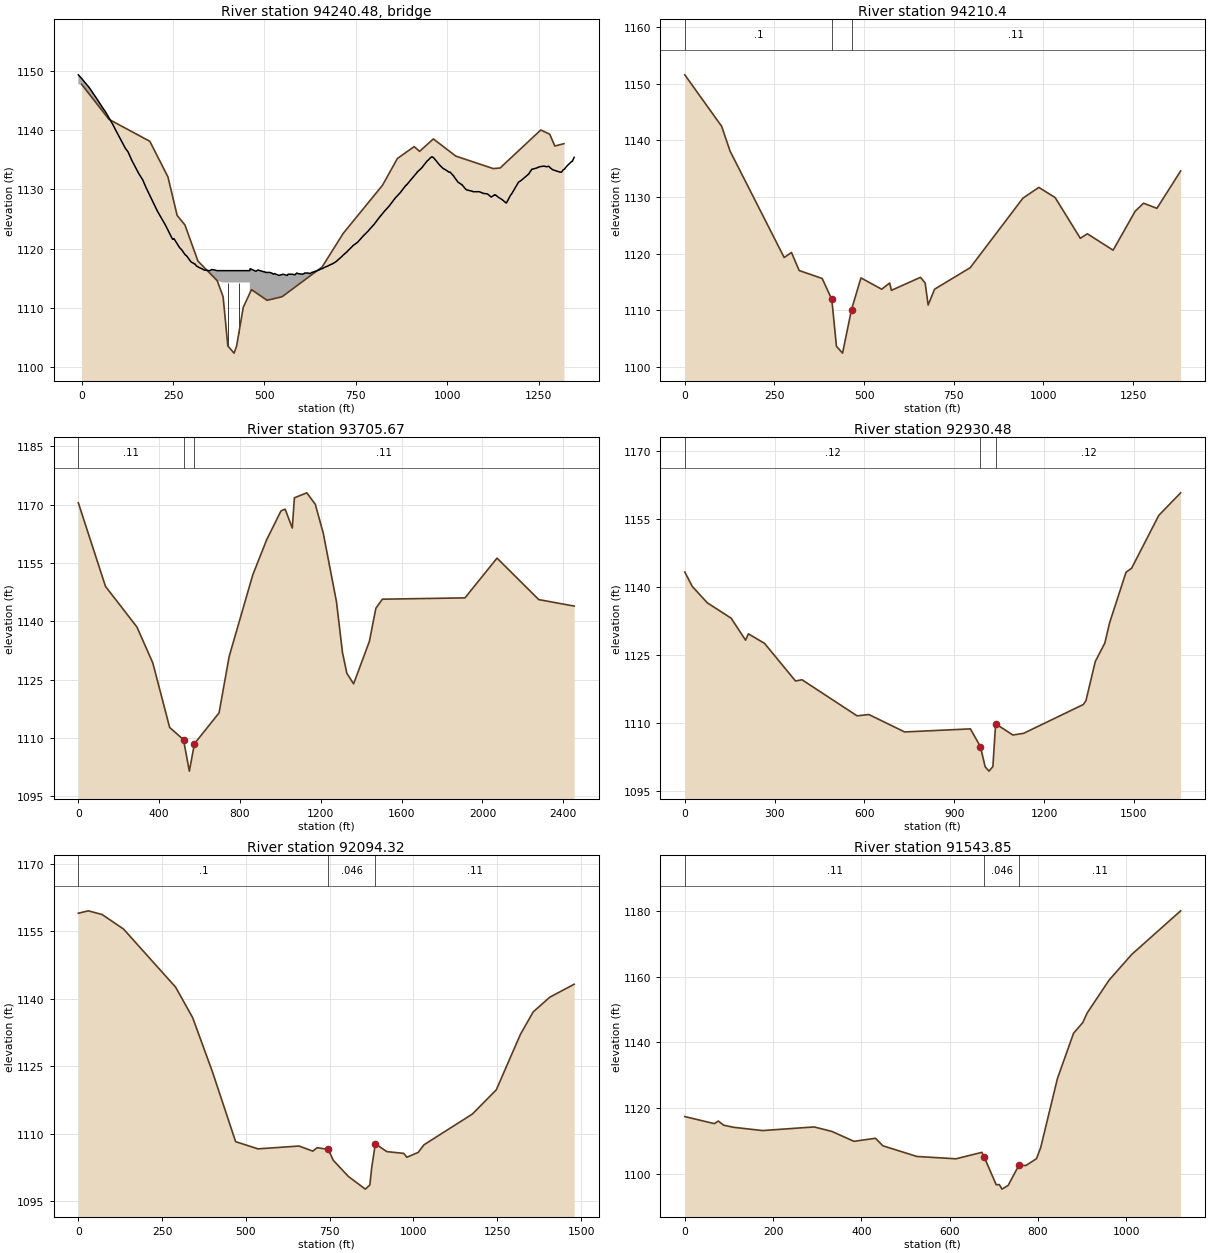
Type RM Length L Ch R = 3 ,94240.48,,,
BEGIN DESCRIPTION:
Bridge : 37003-0006 - SR-1332 / Little River Rd
END DESCRIPTION:
Bridge Culvert--1,0,-1,-1, 0
Deck Dist Width WeirC Skew NumUp NumDn MinLoCord MaxHiCord MaxSubmerge Is_Ogee
18.3,26,2.6,0, 191, 190, , , 0.95, 0, 0,0,,
      -9     1.3     3.8    21.5  42.301  55.801      65  78.999    85.6      93
   105.1   110.6 119.799   127.1   137.2 146.399   155.9 167.101   176.9 187.899
   194.3   207.5 225.501   227.4 228.999   248.6   251.6 252.499 267.699 273.901
 282.899     287 298.799   309.7   310.5   313.9   322.2     330   332.4   335.6
 350.601     356   364.9 370.001 370.001     460     460   460.7 461.299   462.2
   476.7   482.2   483.1 498.599 501.301   502.8   515.3 518.999   519.9   524.8
   527.9 539.701   545.1   546.1     551   562.1 564.901 566.699   575.5   583.2
   588.6 591.899   603.8   608.2 609.899   619.1   625.3     629   629.8   630.4
   644.5   655.4   656.7   669.5   670.8   683.6   684.8   697.9   699.2   712.1
   713.3   726.3   727.5   740.7 741.901 755.399   756.6   769.8     771   784.2
   785.3   799.9   813.6   814.7   828.2 842.801   843.8   857.6   858.6   872.5
   873.4   887.2   888.2 901.901   902.9 916.799   917.7 931.699   932.5   946.6
   947.4 949.299   950.6   953.7 958.299   963.2   979.1     989   995.51004.599
  1008.31010.8011018.401  1018.9  1029.61039.801  1040.5  1041.11042.9011049.501
1053.301  1067.6  1070.8  1077.7  1081.4    1088  1099.5  1101.5  1102.7  1109.6
  1110.8  1120.3  1130.2  1131.9  1133.6  1139.2    1141  1141.9  1149.51161.199
  1162.7  1166.2  1173.1  1175.9  1192.9  1194.9  1202.2  1223.2    1225  1231.5
  1232.6  1233.3  1244.61252.099  1262.2  1266.5  1271.5  1277.4  1282.3  1288.6
  1303.51308.799  1310.31312.599  1317.2  1320.6  1326.9  1338.6  1340.8    1342
  1347.2
  1149.3  1148.6  1148.4  1147.1  1145.2  1143.9  1143.1  1141.6  1140.9    1140
  1138.6    1138  1136.9  1136.3  1134.9  1133.8  1132.7  1131.6  1130.2  1128.8
    1128  1126.3  1124.4  1124.2    1124  1121.6  1121.6  1121.7  1120.2  1119.8
    1119  1118.8  1117.8  1117.4  1117.4  1117.1  1116.8  1116.6  1116.5  1116.4
  1116.3  1116.5  1116.4  1116.3  1116.3  1116.3  1116.3  1116.6  1116.6  1116.6
  1116.2  1116.4  1116.4  1116.1  1116.1    1116    1116  1115.9  1115.9  1115.7
  1115.8  1115.5  1115.6  1115.6  1115.7  1115.5  1115.7  1115.7  1115.7  1115.6
  1115.9  1115.8  1115.7  1115.8  1115.9  1115.9  1115.8    1116    1116    1116
  1116.3  1116.6  1116.6    1117    1117  1117.4  1117.4  1117.9    1118  1118.7
  1118.8  1119.5  1119.6  1120.4  1120.5  1121.1  1121.2  1122.1  1122.2    1123
  1123.1  1124.1  1125.2  1125.3  1126.3  1127.3  1127.4  1128.5  1128.6  1129.5
  1129.6  1130.7  1130.7  1131.7  1131.8  1132.8  1132.9  1133.7  1133.8  1134.9
  1134.9    1135  1135.1  1135.3  1135.5  1135.3  1134.1  1133.5  1133.3  1132.9
  1132.9  1132.7  1132.2  1132.1  1131.2  1130.8  1130.8  1130.7  1130.6  1130.1
  1129.9  1129.7  1129.6  1129.6  1129.6  1129.6  1129.3  1129.3  1129.3  1129.2
  1129.2  1128.7  1129.1    1129    1129  1128.7  1128.6  1128.6  1128.3  1127.7
  1127.8  1128.2    1129  1129.2    1131  1131.2  1131.5  1132.6  1132.8  1133.4
  1133.4  1133.4  1133.6  1133.8  1133.9  1133.9  1133.8  1133.9  1133.6  1133.3
    1133  1132.9  1132.9  1132.9  1133.3  1133.4  1133.9  1134.6  1134.7  1134.7
  1135.4
                                                                                
                                                                                
                                                                                
                                                                                
                                  1114.3  1114.3
                                                                                
                                                                                
                                                                                
                                                                                
                                                                                
                                                                                
                                                                                
                                                                                
                                                                                
                                                                                
                                                                                
                                                                                
                                                                                
                                                                                
        
    13.2    23.6  26.099  43.701    64.6    78.1    87.2   101.2   107.8   115.2
 127.399   132.8     142   149.3   159.4   168.7 178.199   189.4   199.2   210.2
   216.6 229.699 247.699   249.6   251.3   270.9   273.8   274.8   289.9   296.2
   305.1 309.199     321   331.9 332.699 336.101   344.5   352.3   354.7   357.8
 372.799 378.299   387.2     393     393 483.001 483.001   483.6   484.5     499
 504.499   505.3   520.9 523.499     525   537.5   541.3   542.2 546.999   550.2
     562 567.399   568.3   573.3   584.4   587.2     589 597.799   605.5 610.901
   614.2     626   630.4   632.2   641.4   647.5   651.2 652.001 652.701   666.7
 677.601   678.9   691.7     693   705.8   707.1   720.2   721.4   734.4   735.6
   748.6   749.7   762.9   764.1   777.6   778.8   792.1   793.2   806.5 807.599
 822.099 835.901   836.9   850.5 864.999 865.999 879.801   880.8 894.699 895.701
 909.501   910.4   924.2 925.099   939.1 939.999   953.9 954.801   968.8 969.699
   971.6   972.9     976   980.6   985.5  1001.31011.199  1017.8  1026.91030.501
  1033.11040.599  1041.1  1051.8  1062.11062.699  1063.4  1065.2  1071.8  1075.6
  1089.81093.0991099.999  1103.71110.301  1121.71123.801    11251131.799  1133.1
  1142.6  1152.4  1154.1  1155.9  1161.41163.201  1164.2  1171.7  1183.51185.001
1188.499  1195.31198.1991215.0991217.199  1224.51245.4991247.2011253.799  1254.9
  1255.61266.901  1274.4  1284.4  1288.8  1293.8  1299.61304.599  1310.9  1325.8
    1331  1332.5  1334.81339.499  1342.81349.1991360.901  1363.1  1364.3  1369.4
  1149.3  1148.6  1148.4  1147.1  1145.2  1143.9  1143.1  1141.6  1140.9    1140
  1138.6    1138  1136.9  1136.3  1134.9  1133.8  1132.7  1131.6  1130.2  1128.8
    1128  1126.3  1124.4  1124.2    1124  1121.6  1121.6  1121.7  1120.2  1119.8
    1119  1118.8  1117.8  1117.4  1117.4  1117.1  1116.8  1116.6  1116.5  1116.4
  1116.3  1116.5  1116.4  1116.3  1116.3  1116.3  1116.3  1116.6  1116.6  1116.2
  1116.4  1116.4  1116.1  1116.1    1116    1116  1115.9  1115.9  1115.7  1115.8
  1115.5  1115.6  1115.6  1115.7  1115.5  1115.7  1115.7  1115.7  1115.6  1115.9
  1115.8  1115.7  1115.8  1115.9  1115.9  1115.8    1116    1116    1116  1116.3
  1116.6  1116.6    1117    1117  1117.4  1117.4  1117.9    1118  1118.7  1118.8
  1119.5  1119.6  1120.4  1120.5  1121.1  1121.2  1122.1  1122.2    1123  1123.1
  1124.1  1125.2  1125.3  1126.3  1127.3  1127.4  1128.5  1128.6  1129.5  1129.6
  1130.7  1130.7  1131.7  1131.8  1132.8  1132.9  1133.7  1133.8  1134.9  1134.9
    1135  1135.1  1135.3  1135.5  1135.3  1134.1  1133.5  1133.3  1132.9  1132.9
  1132.7  1132.2  1132.1  1131.2  1130.8  1130.8  1130.7  1130.6  1130.1  1129.9
  1129.7  1129.6  1129.6  1129.6  1129.6  1129.3  1129.3  1129.3  1129.2  1129.2
  1128.7  1129.1    1129    1129  1128.7  1128.6  1128.6  1128.3  1127.7  1127.8
  1128.2    1129  1129.2    1131  1131.2  1131.5  1132.6  1132.8  1133.4  1133.4
  1133.4  1133.6  1133.8  1133.9  1133.9  1133.8  1133.9  1133.6  1133.3    1133
  1132.9  1132.9  1132.9  1133.3  1133.4  1133.9  1134.6  1134.7  1134.7  1135.4
                                                                                
                                                                                
                                                                                
                                                                                
                                  1114.3  1114.3
                                                                                
                                                                                
                                                                                
                                                                                
                                                                                
                                                                                
                                                                                
                                                                                
                                                                                
                                                                                
                                                                                
                                                                                
                                                                                
                                                                                
Pier Skew, UpSta & Num, DnSta & Num=  ,400, 2 ,423, 2 , 0 , 0 , 0 ,,
       1       1
  1102.6  1114.8
       1       1
  1102.6  1114.8
Pier Skew, UpSta & Num, DnSta & Num=  ,430, 2 ,452.999, 2 , 0 , 0 , 0 ,,
       1       1
  1104.6  1114.8
       1       1
  1104.6  1114.8
BR Coef=-1 , 1 , 0 ,, 0 ,,,0.8,0,1.2,0,
WSPro=,,,, 1 ,,,, 0 ,,,, 0 ,,,,-1 ,-1 ,-1 , 0 , 0 , 0 , 0 , 0
BC Design=,, 0 ,, 0 ,,,,,,

Type RM Length L Ch R = 1 ,94210.4 ,504.73,504.73,539.96
BEGIN DESCRIPTION:
Down stream xs of Bridge 37003-0006
END DESCRIPTION:
XS GIS Cut Line= 4
  1336856.045804   816518.676998   1336253.25246   816206.654854
  1336103.981419    816487.72455  1335740.246379   816616.547334
#Sta/Elev= 30
       0  1151.6 102.801  1142.5   126.4  1138.1   277.2  1119.3   297.5  1120.2
     319    1117   383.2  1115.6     410  1111.9     423  1103.6     440  1102.4
     465  1110.1 491.301  1115.7   549.1  1113.7 571.501  1114.8   576.1  1113.5
   657.3  1115.8 670.399  1114.8 678.699  1110.9 696.601  1113.7     796  1117.5
 943.099  1129.8   987.4  1131.7    1033  1129.91103.099  1122.7  1122.7  1123.5
  1194.6  1120.6  1256.3  1127.51279.399  1128.9  1316.8    1128  1382.9  1134.6
#Mann= 3 , 0 , 0
       0      .1       0     410    .046       0     465     .11       0
#XS Ineff= 2 , 0
       0 375.899  1114.5  652.01       0    1115
Permanent Ineff=
       F       F
Bank Sta=410,465
Exp/Cntr=0.5,0.3

Type RM Length L Ch R = 1 ,93705.67,775.19,775.19,718.32
XS GIS Cut Line= 4
  1336956.461292   816062.870277  1336653.800556   815881.273861
  1336037.797227   815696.116741  1334890.357354   816595.196934
#Sta/Elev= 30
       0 1170.49  134.48 1148.99  290.17 1138.54  368.37 1129.34  452.02 1112.72
  520.59 1109.57  549.44 1101.49  574.62 1108.54  696.48 1116.47   746.5 1130.97
  863.27 1151.94  932.33 1161.01 1003.12 1168.42 1023.62 1168.85 1058.81    1164
 1069.39 1171.77 1130.77 1173.05 1172.79  1170.1 1212.18 1162.69 1277.74    1145
 1307.26 1132.01 1328.93 1126.65 1362.32 1123.93 1440.44 1134.85 1472.63 1143.38
 1504.77  1145.7 1913.58 1146.04 2072.23 1156.26 2278.87 1145.59 2453.91 1143.93
#Mann= 3 , 0 , 0
       0     .11       0  520.59    .047       0  574.62     .11       0
Bank Sta=520.59,574.62
Exp/Cntr=0.3,0.1

Type RM Length L Ch R = 1 ,92930.48,836.16,836.16,796.38
XS GIS Cut Line= 2
  1337595.884269   815710.023173  1336218.174827   814790.651524
#Sta/Elev= 30
       0 1143.29   24.99  1140.1   75.38 1136.49  154.91 1133.11     203 1128.27
  212.51 1129.67  266.52 1127.56  369.73 1119.28  391.53 1119.55  575.54  1111.6
  614.96 1111.89  734.36 1108.05  954.06 1108.73  987.61 1104.81 1003.21 1100.41
 1015.97 1099.42 1029.14 1100.42  1038.1 1109.64 1040.54 1109.76 1095.76 1107.38
 1131.88 1107.75 1331.13 1114.09 1340.03 1114.94 1371.16 1123.56 1403.12 1127.63
 1418.99 1132.08 1474.02 1143.25 1492.53 1144.11 1583.31 1155.75  1656.3 1160.73
#Mann= 3 , 0 , 0
       0     .12       0  987.61    .047       0 1040.54     .12       0
Bank Sta=987.61,1040.54
Exp/Cntr=0.3,0.1

Type RM Length L Ch R = 1 ,92094.32,550.47,550.47,559
XS GIS Cut Line= 2
  1337887.063661   815157.321733  1336854.455532    814097.75258
#Sta/Elev= 30
       0 1159.03   29.57 1159.57   70.99 1158.75  134.91 1155.52  290.31  1142.6
  341.28 1135.81  400.97 1123.61  469.37 1108.25  536.16 1106.65  658.38 1107.28
  699.86 1106.15  712.49 1106.91  745.75 1106.53  760.67 1104.12  806.07  1100.5
  856.53  1097.7  869.85 1098.63  875.56 1102.56  886.18 1107.76  920.69 1106.04
  970.75 1105.65  980.51 1104.79 1014.04 1105.86 1031.48 1107.56 1175.76 1114.39
 1247.09 1119.77 1319.27 1132.12 1357.51 1137.12 1406.85 1140.37 1479.52 1143.25
#Mann= 3 , 0 , 0
       0      .1       0  745.75    .046       0  886.18     .11       0
Bank Sta=745.75,886.18
Exp/Cntr=0.3,0.1

Type RM Length L Ch R = 1 ,91543.85,670.54,670.54,706.87
XS GIS Cut Line= 2
  1338191.723501   814639.669636  1337374.803821   813868.583683
#Sta/Elev= 30
       0 1117.49   66.79 1115.36   76.09 1116.13   88.15 1114.87  110.53 1114.24
     176 1113.25  293.09 1114.35  333.01    1113  383.29 1109.98  431.99 1110.91
   448.7 1108.63  525.89 1105.38  614.34 1104.68  673.05 1106.63   678.6 1105.14
  705.49  1096.8  712.68 1096.84  718.66 1095.47  732.54 1096.59  757.33 1102.79
  772.54 1102.62  796.74  1104.7  806.26 1108.04  844.22 1129.03  880.73 1142.79
  901.67 1146.03  911.64 1148.95  961.11  1158.9 1012.42  1166.7 1123.36 1179.96
#Mann= 3 , 0 , 0
       0     .11       0   678.6    .046       0  757.33     .11       0
Bank Sta=678.6,757.33
Exp/Cntr=0.3,0.1

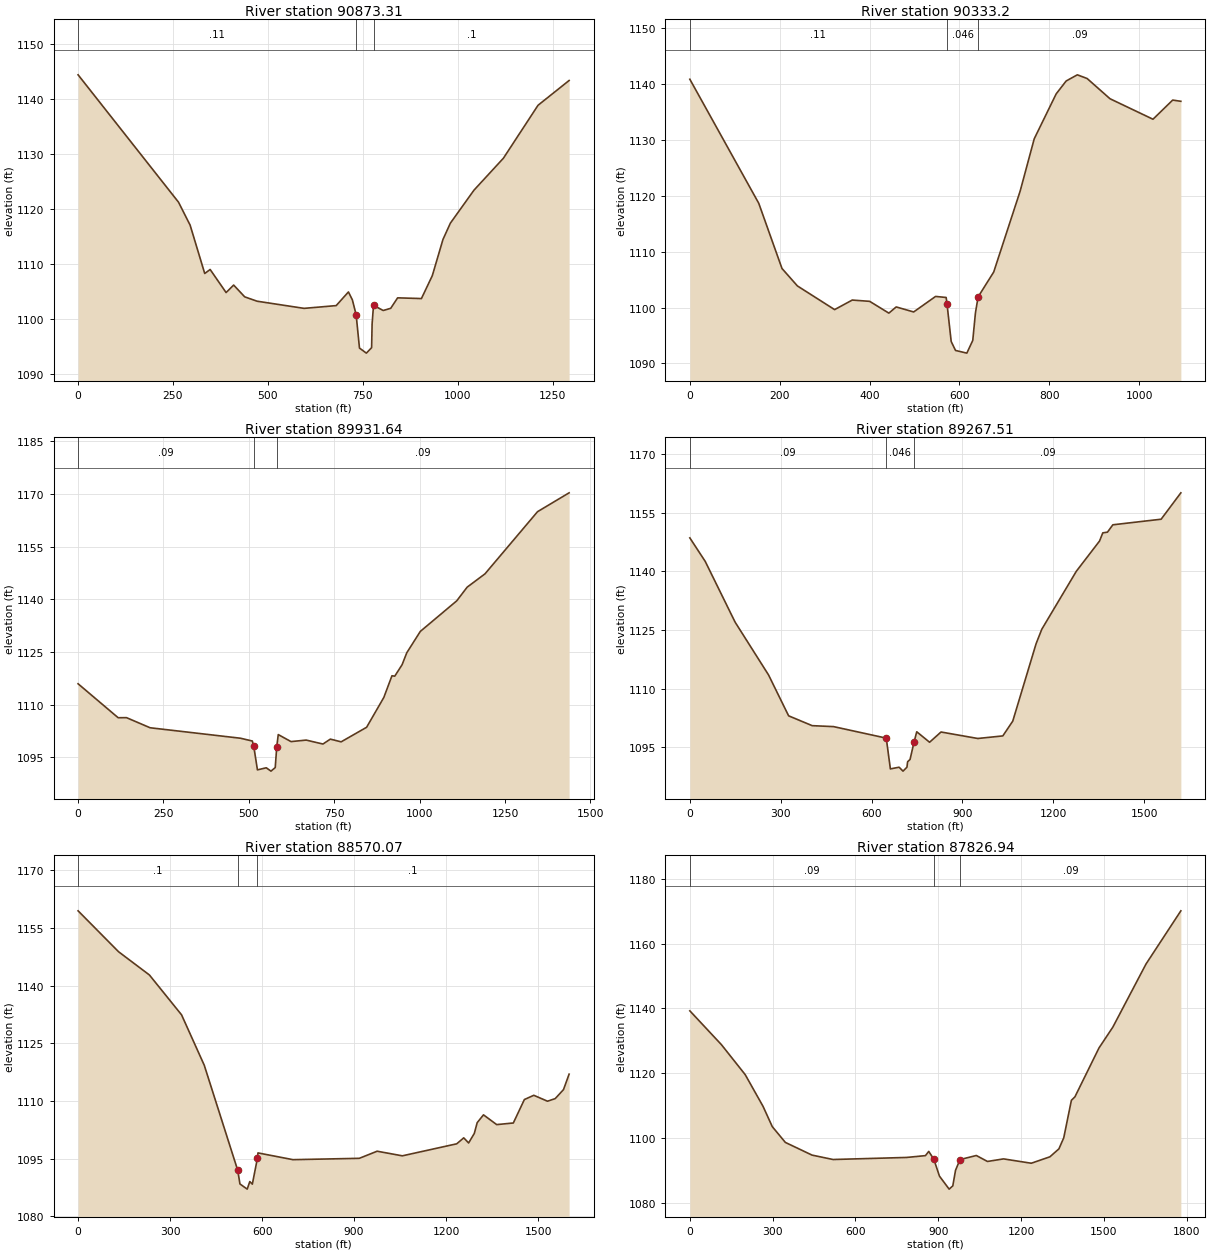
Type RM Length L Ch R = 1 ,90873.31,540.12,540.12,537.62
XS GIS Cut Line= 2
  1338690.806638   814015.885955  1337597.056621   813324.913795
#Sta/Elev= 30
       0 1144.42  264.62 1121.29   295.2 1117.12  333.67 1108.34  347.91 1109.07
  389.99 1104.88   409.9 1106.24  438.98  1104.1  471.49 1103.31  595.42 1102.01
  680.05 1102.51  712.29 1104.99  722.65 1103.56  732.63 1100.84  741.38  1094.8
  759.53 1093.88  773.35 1094.87  774.67 1099.19  778.41 1102.56  803.88 1101.62
  823.76 1102.02  841.88 1103.92  904.63 1103.79   933.3 1107.95  961.36 1114.52
  980.87 1117.48 1043.03 1123.47 1120.55 1129.27 1211.86 1138.89 1293.73 1143.39
#Mann= 3 , 0 , 0
       0     .11       0  732.63    .046       0  778.41      .1       0
Bank Sta=732.63,778.41
Exp/Cntr=0.3,0.1

Type RM Length L Ch R = 1 ,90333.2 ,401.55,401.55,482.17
XS GIS Cut Line= 3
  1338829.483886   813494.899075  1338381.592558   813182.941315
  1337916.503917   812895.060354
#Sta/Elev= 30
       0 1140.88  153.39 1118.67  205.09    1107  239.35 1103.88  322.19 1099.64
  361.47 1101.35  400.25 1101.12  442.97 1099.01  459.24 1100.12  498.12 1099.22
  546.93    1102  570.44 1101.81  572.32 1100.69  581.66 1093.93  591.31 1092.33
   616.5 1091.85  629.69 1094.13  635.65 1099.08  641.59 1101.92  676.29 1106.37
  735.15 1120.86  766.47 1130.22  815.31 1138.26  837.55 1140.57  862.39 1141.67
   884.2 1141.01  935.07 1137.39 1030.75 1133.72 1074.64 1137.15  1092.8 1136.93
#Mann= 3 , 0 , 0
       0     .11       0  572.32    .046       0  641.59     .09       0
Bank Sta=572.32,641.59
Exp/Cntr=0.3,0.1

Type RM Length L Ch R = 1 ,89931.64,664.14,664.14,719.04
XS GIS Cut Line= 6
  1339089.526382   812827.887234  1338709.375598   812852.152194
   1338606.92363   812846.759938  1338501.775598   812787.445634
  1338245.645549   812809.014402  1337754.954477   812507.050754
#Sta/Elev= 30
       0 1115.96  117.31 1106.29  141.77 1106.31   210.9 1103.43  475.43 1100.45
  510.09 1099.65  514.32 1098.15  524.98 1091.44  550.96 1092.03  564.63 1091.08
  577.14 1092.09  581.55 1097.96  585.99 1101.49  623.29 1099.49  667.76 1099.92
  716.79  1098.8  738.58  1100.2  770.01 1099.42  844.63 1103.57  895.06 1112.07
  918.81 1118.24  927.02 1118.13  948.49 1121.39  962.27  1124.8  1001.8 1130.87
 1108.51 1139.59    1139 1143.48 1191.25 1147.28 1345.01 1164.98 1437.44 1170.35
#Mann= 3 , 0 , 0
       0     .09       0  514.32    .047       0  581.55     .09       0
Bank Sta=514.32,581.55
Exp/Cntr=0.3,0.1

Type RM Length L Ch R = 1 ,89267.51,697.43,697.43,654.05
XS GIS Cut Line= 4
  1339374.834542   812265.885954   1339046.71115    812165.33581
  1338028.235885   812224.421378  1337771.864557   812249.346434
#Sta/Elev= 30
       0 1148.55   50.86 1142.53  149.26 1127.02  259.89 1113.48  326.08 1103.03
  403.97 1100.51  474.33 1100.27  648.43 1097.32  662.02 1089.45  690.83 1089.88
  703.67 1088.88  716.71 1089.88  718.96 1091.29  726.92 1091.86  740.13 1096.29
  749.03 1098.95  791.44 1096.27  829.19 1098.89  950.63 1097.23 1033.22 1097.89
 1065.99 1101.67 1143.04 1121.48 1161.96 1125.19 1275.86 1140.01 1352.52 1147.75
 1363.25 1149.84 1378.66 1150.02 1396.42  1151.9 1555.82 1153.33 1620.95 1160.08
#Mann= 3 , 0 , 0
       0     .09       0  648.43    .046       0  740.13     .09       0
Bank Sta=648.43,740.13
Exp/Cntr=0.3,0.1

Type RM Length L Ch R = 1 ,88570.07,743.13,743.13,731.39
XS GIS Cut Line= 2
  1339345.143406   811585.829761  1337763.723373   811335.330433
#Sta/Elev= 30
       0  1159.5  131.83 1148.86  232.68 1142.79  337.39 1132.42  411.41  1119.3
  520.57 1091.93  527.76 1088.39  551.41 1087.04  559.97 1089.01  568.22 1088.34
  584.62 1095.02  586.54 1096.47  700.71 1094.71  917.03 1095.06  975.11 1096.91
 1057.43 1095.71 1234.68 1098.84 1257.59 1100.39 1273.45 1099.06    1292 1101.54
 1301.36 1104.34 1321.93 1106.38 1364.97 1103.84 1419.26 1104.26 1455.29 1110.37
 1486.03 1111.47 1530.69 1109.93 1555.84 1110.61 1582.81 1112.95 1601.14 1116.98
#Mann= 3 , 0 , 0
       0      .1       0  520.57    .046       0  584.62      .1       0
Bank Sta=520.57,584.62
Exp/Cntr=0.3,0.1

Type RM Length L Ch R = 1 ,87826.94,738.33,738.33,701.38
XS GIS Cut Line= 3
  1339798.445551   811088.802689  1339503.306735   810908.247169
  1338107.473389   810585.330432
#Sta/Elev= 30
       0 1139.24  114.47 1128.78  200.59 1119.52  265.04 1109.75  298.64 1103.46
  345.99 1098.58  442.73 1094.66  518.83  1093.3  785.46 1093.94  853.48  1094.5
   865.4 1095.81  883.76  1093.4  904.19 1088.17  939.28 1084.15  952.54 1085.15
  962.42 1089.96  978.58 1093.28 1037.73 1094.54 1078.12  1092.7 1136.33 1093.49
 1236.84 1092.15 1304.19 1094.13 1336.87 1096.58 1354.47 1100.01 1382.17  1111.6
 1394.85 1112.65 1482.12 1127.77 1532.11 1134.18 1652.47 1153.71 1778.69 1170.14
#Mann= 3 , 0 , 0
       0     .09       0  883.76    .046       0  978.58     .09       0
Bank Sta=883.76,978.58
Exp/Cntr=0.3,0.1