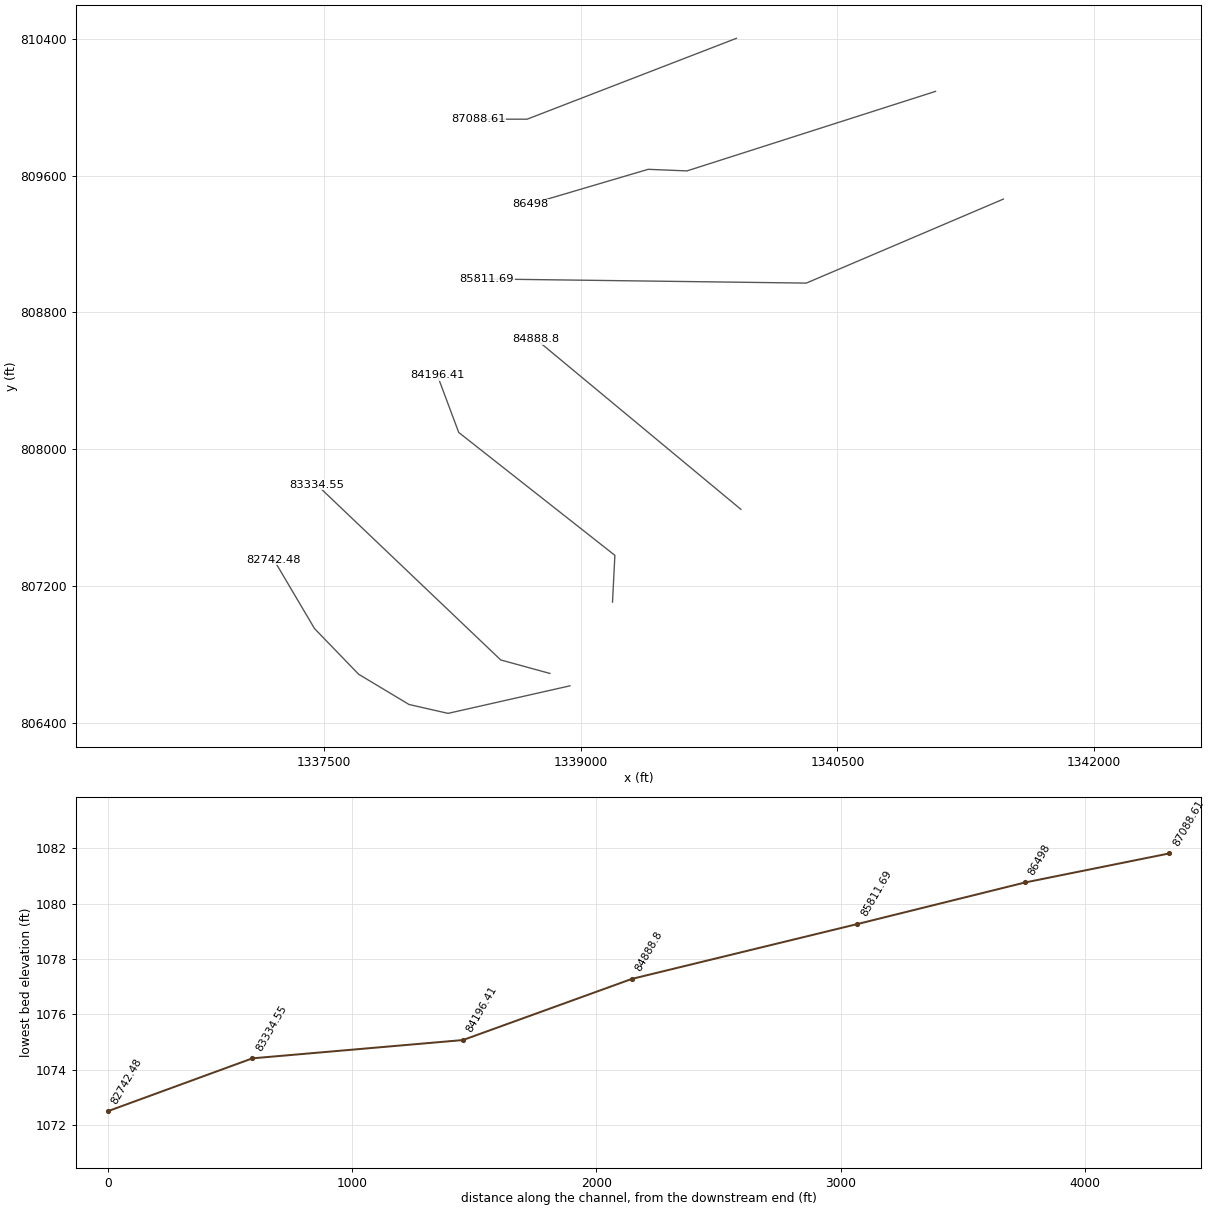
HEC-RAS study LLRiver.prj: LLRiver

--- LLRiver.g01 (geometry) --- (continued)

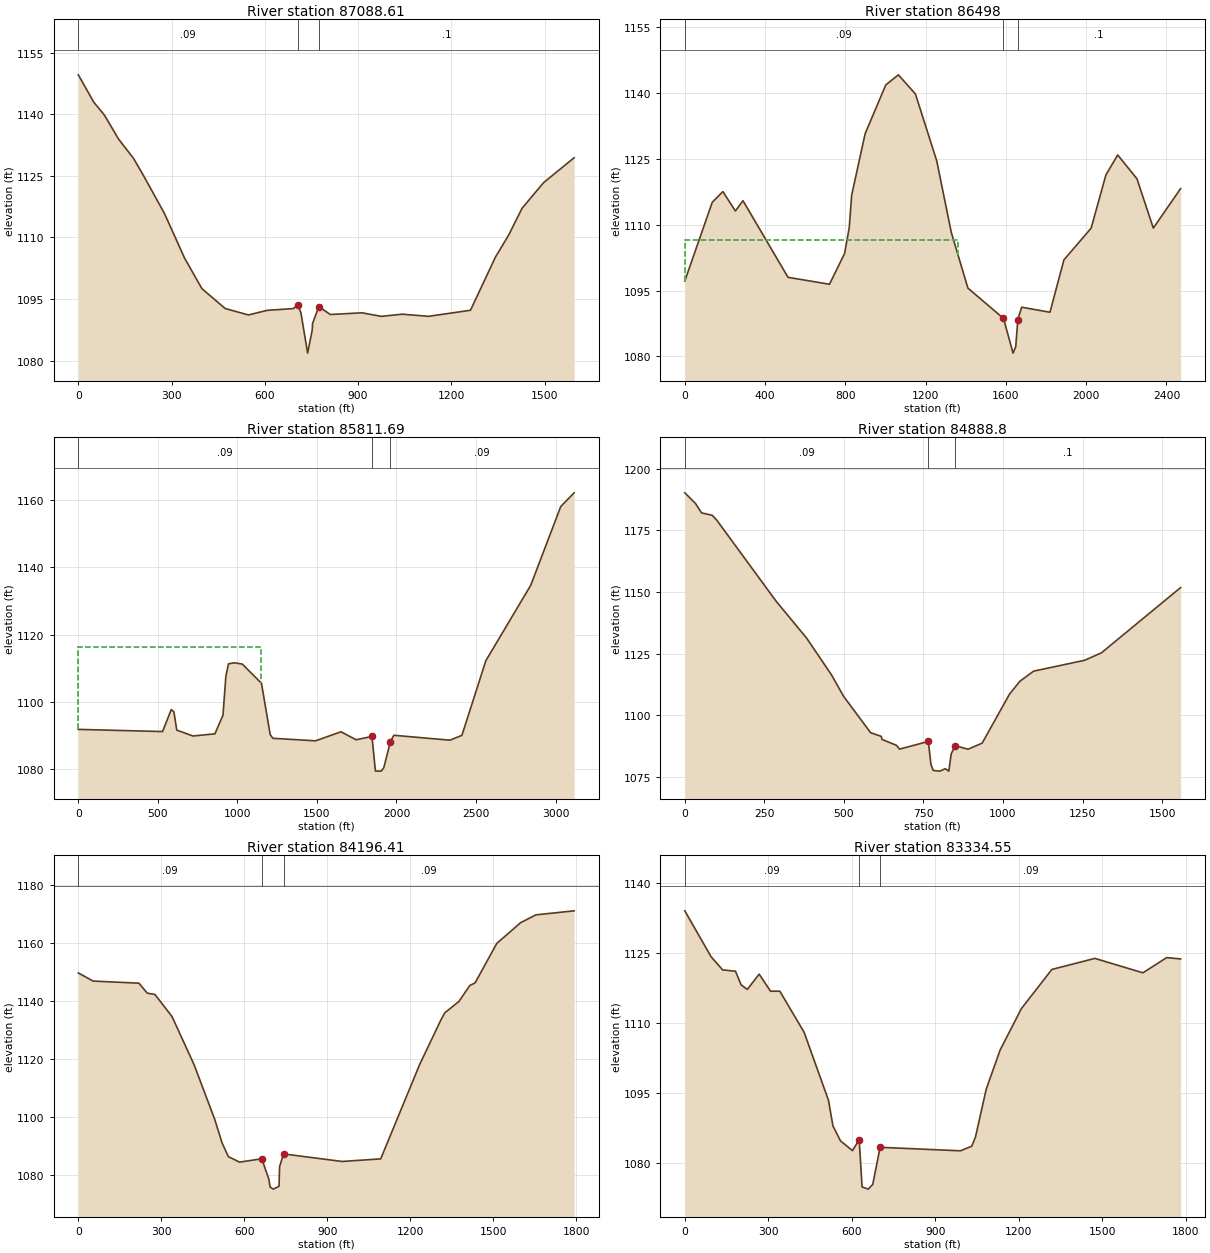
Type RM Length L Ch R = 1 ,87088.61,590.61,590.61,641.83
XS GIS Cut Line= 3
  1339909.556719   810401.302656   1338687.33451   809929.080448
  1338402.612334   809929.080448
#Sta/Elev= 30
       0 1149.63   49.69 1142.96   83.99 1139.81  129.38 1133.98  177.65 1129.26
  207.76 1125.33  276.68  1115.9  341.84 1104.97  397.67 1097.51  472.45 1092.68
  547.31 1091.11  607.23 1092.23  692.31 1092.67  705.18 1093.58  715.98 1091.69
  737.61 1081.81  752.27 1087.38  753.58 1089.04  773.58 1093.16  810.44 1091.22
  912.37 1091.64  974.74 1090.77 1041.61  1091.3 1126.79 1090.78 1261.56 1092.26
  1341.9 1105.23 1383.86 1110.51 1427.36  1117.1 1496.54 1123.35    1595 1129.43
#Mann= 3 , 0 , 0
       0     .09       0  705.18    .046       0  773.58      .1       0
Bank Sta=705.18,773.58
Exp/Cntr=0.3,0.1

Type RM Length L Ch R = 1 ,86498   ,686.31,686.31,704.42
XS GIS Cut Line= 4
   1341072.97944   810091.517056  1339621.362287   809626.997119
  1339394.510446   809636.256383  1338704.695662   809432.552703
#Sta/Elev= 30
       0 1097.17  136.87 1115.09   189.7 1117.51  252.19  1113.1  289.73 1115.45
  514.32 1098.01  720.89 1096.43   796.2 1103.43  819.48 1109.36  831.37 1116.69
  898.71 1130.71 1001.42 1141.78 1064.14 1144.08 1149.16 1139.72 1255.19 1124.52
 1328.01 1108.19 1410.68 1095.55  1587.9 1088.66 1635.59 1080.76 1648.82 1082.21
 1659.43 1088.41 1678.28 1091.21 1819.45 1090.06 1888.92 1101.97  2024.6 1109.19
 2098.31 1121.31 2156.92 1125.85  2252.9 1120.43 2334.34 1109.21 2470.43  1118.2
#Mann= 3 , 0 , 0
       0     .09       0  1587.9    .046       0 1659.43      .1       0
#XS Ineff= 2 , 0
         1362.89 1106.53
Permanent Ineff=
       F       F
Bank Sta=1587.9,1659.43
Exp/Cntr=0.3,0.1

Type RM Length L Ch R = 1 ,85811.69,922.88,922.88,1062.41
XS GIS Cut Line= 3
   1341469.17208   809462.404863  1340318.188143   808971.725951
   1338452.34699   808995.823615
#Sta/Elev= 30
       0 1091.71  529.52 1091.06  584.17 1097.61  601.03 1096.93  618.78  1091.5
  720.63 1089.74  858.61 1090.38  909.38 1095.93  927.59 1107.55     944 1111.26
  979.63 1111.56 1030.39  1111.2 1151.46 1105.46 1206.35 1090.14  1222.9 1089.05
 1491.99  1088.3 1651.15    1091 1746.47 1088.61 1846.05 1089.61 1867.71 1079.28
 1904.05 1079.26 1920.31 1080.27  1962.3 1088.07 1983.67 1089.95  2335.8 1088.49
  2411.6 1089.93 2561.88 1112.18 2844.52 1134.71 3032.97 1158.18 3117.21 1162.26
#Mann= 3 , 0 , 0
       0     .09       0 1846.05    .046       0  1962.3     .09       0
#XS Ineff= 2 , 0
         1149.45 1116.35
Permanent Ineff=
       F       F
Bank Sta=1846.05,1962.3
Exp/Cntr=0.3,0.1

Type RM Length L Ch R = 1 ,84888.8 ,692.39,692.39,688
XS GIS Cut Line= 2
  1339936.177135   807650.145278  1338737.103086   808645.515646
#Sta/Elev= 30
       0 1190.28   33.58 1185.98   52.44 1182.15   86.54 1181.14  100.63 1179.16
  286.61 1146.35  383.08 1131.26  460.66 1116.45  499.83 1107.52  584.06 1092.88
  617.28 1091.41  620.22 1090.13  665.41 1087.76  675.05 1086.21  765.43 1089.34
  773.63 1079.99  780.78 1077.56  802.15 1077.28  818.71 1078.28   829.8 1077.28
  837.33 1084.29  849.86 1087.64  890.22 1086.17  934.62 1088.64 1020.56 1108.54
 1053.53 1113.81 1096.43 1117.88 1256.78 1122.29 1309.37  1125.3 1558.38 1151.82
#Mann= 3 , 0 , 0
       0     .09       0  765.43    .046       0  849.86      .1       0
Bank Sta=765.43,849.86
Exp/Cntr=0.3,0.1

Type RM Length L Ch R = 1 ,84196.41,861.86,861.86,880.77
XS GIS Cut Line= 4
  1339186.177134   807108.478589  1339200.065902   807381.626749
  1338288.028909   808099.219326  1338162.689901   808434.598526
#Sta/Elev= 30
       0 1149.78   53.67 1146.96  219.01 1146.24  248.92 1142.81  277.06 1142.32
  338.62 1134.71  418.42 1118.06  492.79 1099.23  519.51 1091.06  542.02 1086.31
  582.85  1084.4  663.06 1085.56  688.64 1078.49  693.19 1075.76  704.73 1075.07
  725.39 1076.08  727.42 1082.84  741.72 1087.24  953.11 1084.63 1092.84 1085.52
 1233.58 1118.12  1310.7 1133.59  1324.6 1136.01 1375.44 1139.91 1414.87 1145.43
    1434 1146.34  1512.3 1159.97 1598.65 1167.15 1653.53 1169.84 1792.03 1171.24
#Mann= 3 , 0 , 0
       0     .09       0  663.06    .046       0  741.72     .09       0
Bank Sta=663.06,741.72
Exp/Cntr=0.3,0.1

Type RM Length L Ch R = 1 ,83334.55,592.07,592.07,539.06
XS GIS Cut Line= 3
  1338820.436334   806691.811965  1338533.399278   806770.515709
  1337459.325165    807793.66387
#Sta/Elev= 30
       0 1134.03   94.65 1124.18     136 1121.38  182.08 1121.09  202.31 1118.17
  224.62  1117.2  267.17 1120.47  308.05 1116.81  341.39 1116.81  428.43 1108.04
  516.17 1093.43  532.19 1087.95  559.38 1084.74  602.25 1082.66   626.5 1084.98
  636.77 1074.89  658.72 1074.41  675.04 1075.41  701.56 1083.37  990.11 1082.62
 1030.91 1083.61  1044.3 1085.61 1082.84 1095.85  1132.9 1104.24 1209.39 1113.11
 1318.45 1121.47 1472.99 1123.84 1645.65 1120.75 1730.97 1124.01 1781.03 1123.72
#Mann= 3 , 0 , 0
       0     .09       0   626.5    .047       0  701.56     .09       0
Bank Sta=626.5,701.56
Exp/Cntr=0.5,0.3

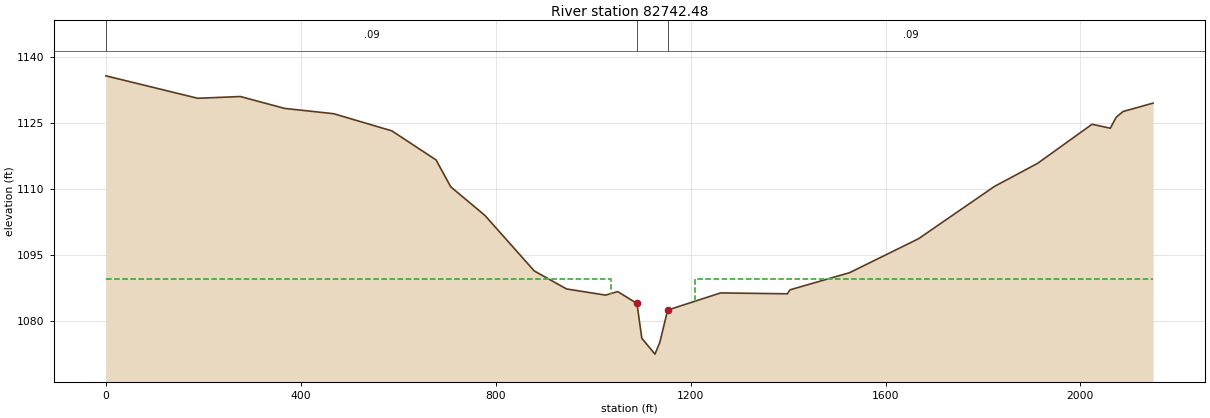
Type RM Length L Ch R = 1 ,82742.48,71.66,71.66,75.24
BEGIN DESCRIPTION:
Upstream xs of Bridge 37003-0016
END DESCRIPTION:
XS GIS Cut Line= 6
   1338937.45419   806619.408125  1338225.540973   806458.547068
  1337998.075885   806510.304124  1337703.484013   806687.059197
  1337445.523053   806954.070781  1337207.402092   807357.156349
#Sta/Elev= 30
       0  1135.7   188.5  1130.6     276    1131   366.7  1128.3   467.3  1127.1
   586.9  1123.2   677.6  1116.6   707.7  1110.5   777.9    1104   879.1  1091.4
   945.4  1087.3  1025.5  1085.9  1050.5  1086.7  1089.9    1084  1099.9  1076.1
  1126.9  1072.5  1136.9  1075.2  1152.9  1082.5  1261.5  1086.4  1398.7  1086.2
  1403.9  1087.1  1526.4    1091  1667.7  1098.7  1823.8  1110.6  1911.8  1115.8
  2023.9  1124.7  2061.3  1123.8  2073.5  1126.3  2087.6  1127.6  2149.1  1129.5
#Mann= 3 , 0 , 0
       0     .09       0  1089.9    .047       0  1152.9     .09       0
#XS Ineff= 2 , 0
       0  1036.6  1089.5  1209.2       0  1089.5
Permanent Ineff=
       F       F
Bank Sta=1089.9,1152.9
Exp/Cntr=0.5,0.3