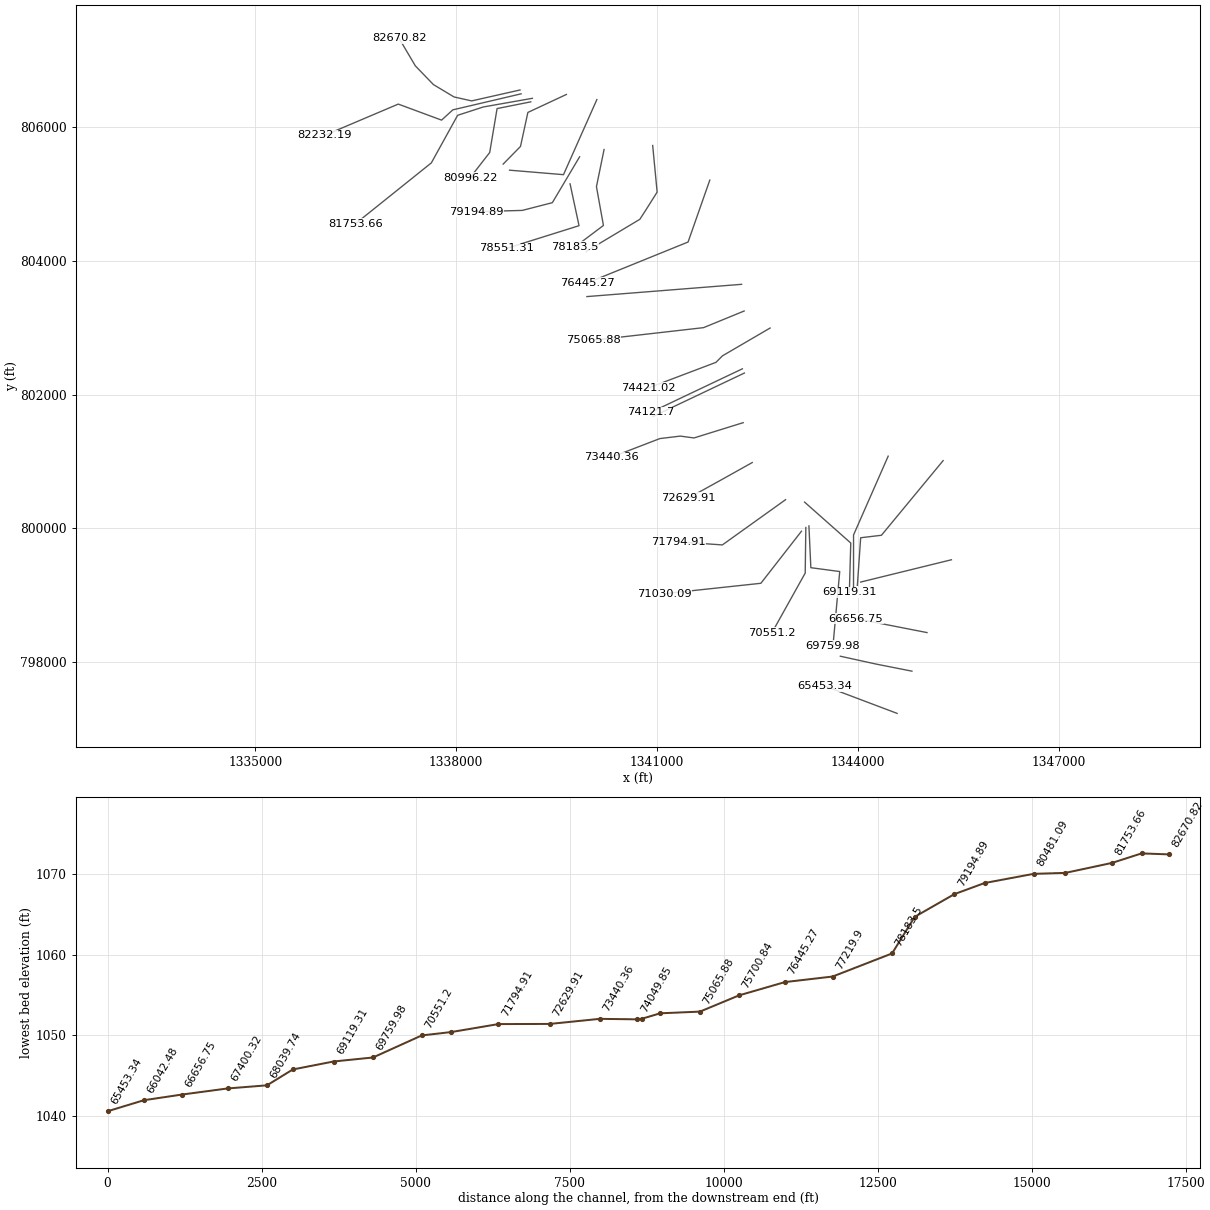
HEC-RAS study LLRiver.prj: LLRiver

--- LLRiver.g01 (geometry) --- (continued)

Type RM Length L Ch R = 3 ,82706.65,,,
BEGIN DESCRIPTION:
Bridge : 37003-0016 - SR-1313 / Three Forks Ch Rd
END DESCRIPTION:
Bridge Culvert--1,0,-1,-1, 0
Deck Dist Width WeirC Skew NumUp NumDn MinLoCord MaxHiCord MaxSubmerge Is_Ogee
19.3,33,2.6,0, 60, 60, , , 0.95, 0, 0,0,,
   -34.6      -2     7.8    19.6    38.1      41    54.8    67.7   106.2     117
   169.5   250.3   327.1   372.3   441.8   512.2   592.3   640.2   657.2   668.5
   674.9   707.2   788.1   794.3   808.7   815.7   824.4   857.4   901.5   933.1
   990.7  1021.2  1055.9  1055.9  1189.9  1189.9  1206.1  1215.8    1279  1312.2
  1362.7  1424.5  1451.9  1469.5  1570.5  1584.4  1623.9  1650.6  1676.3    1687
  1758.4  1773.8  1805.8  1822.2  1885.3  1916.3    1927  1971.6  2071.5  2159.7
  1134.5  1134.6  1134.1  1134.9  1134.4    1134  1134.4  1133.7  1133.8  1133.1
  1132.5  1130.5  1127.5  1126.2  1123.1  1119.2  1114.4    1111  1110.4  1109.2
  1109.2  1107.1  1100.8  1100.9  1099.6  1099.6    1099  1095.9  1092.9  1091.6
  1090.6  1091.1    1091    1091    1091    1091  1091.1  1090.5  1090.2  1090.5
  1089.8    1090  1090.7  1090.7  1094.8  1095.8  1096.6  1098.6  1099.6  1101.4
  1105.6  1107.1  1108.9  1110.4  1114.5  1117.1  1117.4  1120.5  1126.2  1130.2
                                                                                
                                                                                
                                                                                
                          1089.2  1089.2
                                                                                
                                                                                
      35    67.6    77.4    89.2   107.7   110.6   124.4   137.3   175.8   186.5
     239   319.9   396.6   441.9   511.4   581.8   661.9   709.8   726.8   738.1
   744.5   776.8   857.7   863.8   878.3   885.3     894     927   971.1  1002.7
  1060.3  1090.8  1125.5  1125.5  1259.5  1259.5  1275.7  1285.3  1348.6  1381.8
  1432.3  1494.1  1521.5  1539.1  1640.1    1654  1693.5  1720.2  1745.8  1756.6
    1828  1843.4  1875.3  1891.8  1954.9  1985.9  1996.6  2041.2  2141.1  2229.3
  1134.5  1134.6  1134.1  1134.9  1134.4    1134  1134.4  1133.7  1133.8  1133.1
  1132.5  1130.5  1127.5  1126.2  1123.1  1119.2  1114.4    1111  1110.4  1109.2
  1109.2  1107.1  1100.8  1100.9  1099.6  1099.6    1099  1095.9  1092.9  1091.6
  1090.6  1091.1    1091    1091    1091    1091  1091.1  1090.5  1090.2  1090.5
  1089.8    1090  1090.7  1090.7  1094.8  1095.8  1096.6  1098.6  1099.6  1101.4
  1105.6  1107.1  1108.9  1110.4  1114.5  1117.1  1117.4  1120.5  1126.2  1130.2
                                                                                
                                                                                
                                                                                
                          1089.2  1089.2
                                                                                
                                                                                
Pier Skew, UpSta & Num, DnSta & Num=  ,1099.94, 2 ,1169.53, 2 , 0 , 0 , 0 ,,
       3       3
  1075.1  1089.7
       3       3
  1075.1  1089.7
Pier Skew, UpSta & Num, DnSta & Num=  ,1144.94, 2 ,1214.53, 2 , 0 , 0 , 0 ,,
       3       3
  1077.8  1089.7
       3       3
  1077.8  1089.7
BR Coef=-1 , 1 , 0 ,, 0 ,,,0.8,0,1.2,0,
WSPro=,,,, 1 ,,,, 0 ,,,, 0 ,,,,-1 ,-1 ,-1 , 0 , 0 , 0 , 0 , 0
BC Design=,, 0 ,, 0 ,,,,,,

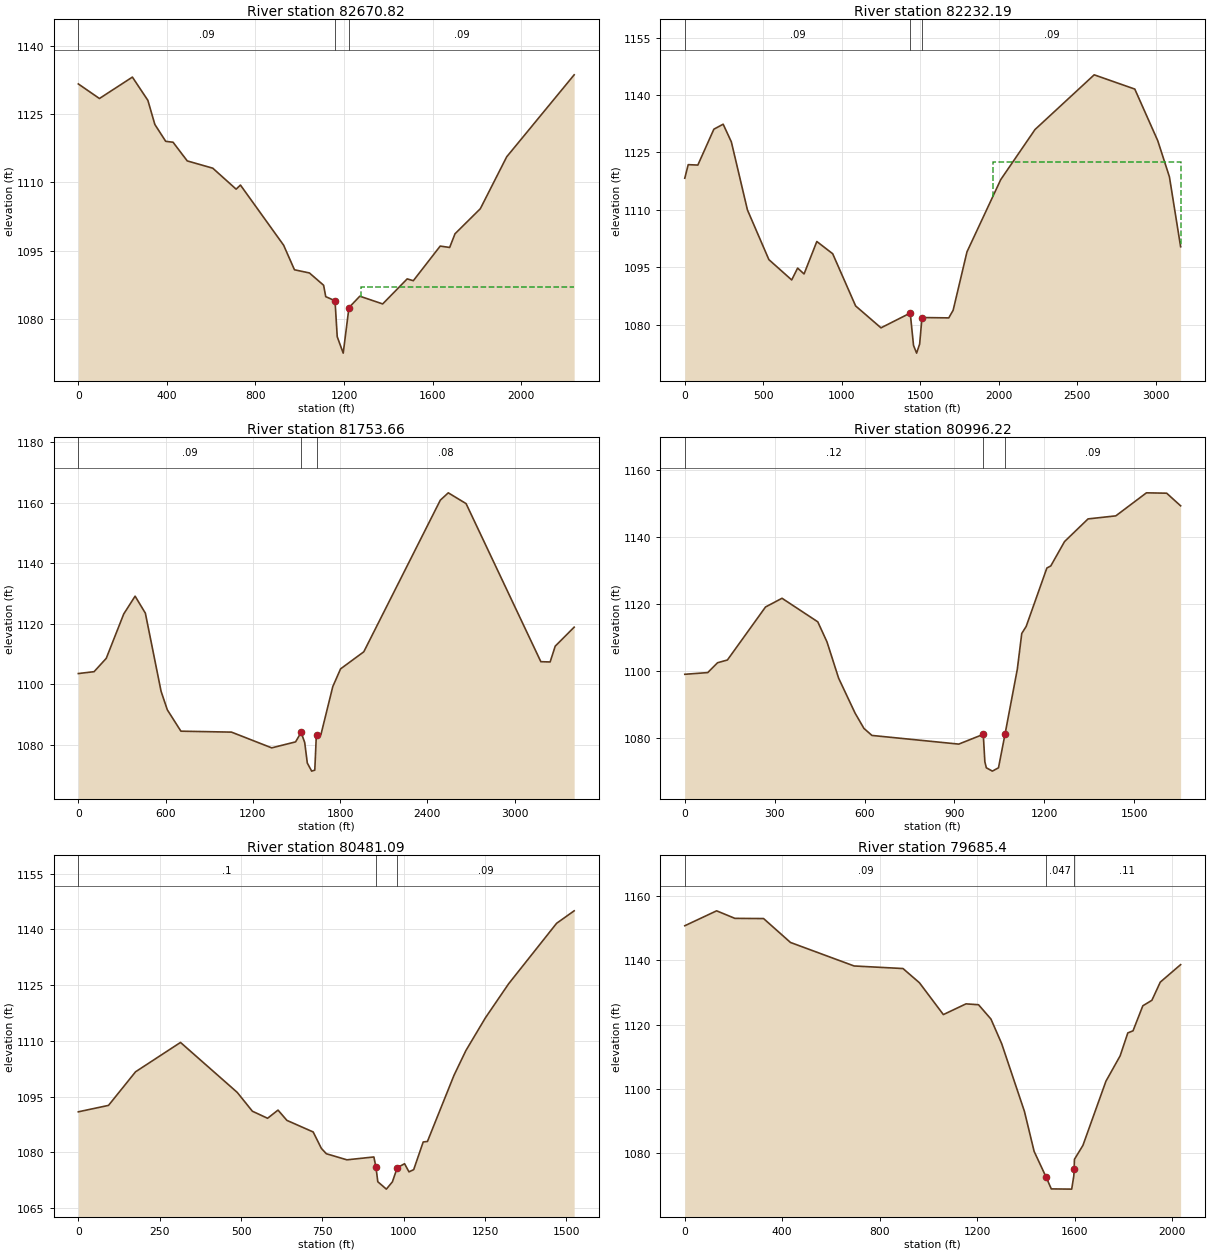
Type RM Length L Ch R = 1 ,82670.82,438.63,438.63,402.38
BEGIN DESCRIPTION:
Down stream xs of Bridge 37003-0016
END DESCRIPTION:
XS GIS Cut Line= 6
  1338953.418478   806551.252861  1338230.146541   806388.039804
  1337966.870893   806447.393788  1337659.610861   806631.749885
  1337389.794157   806911.034621  1337146.433644   807322.763901
#Sta/Elev= 30
       0  1131.6    95.3  1128.4   244.2  1133.1   314.1    1128   345.7  1122.7
   394.7    1119   427.9  1118.8     492  1114.7   607.4  1113.1   712.8  1108.5
   732.3  1109.4   927.3  1096.2   976.3  1090.8  1043.9  1090.1    1108  1087.4
  1117.5  1084.9  1159.5    1084  1169.5  1076.1  1196.5  1072.5  1222.5  1082.5
  1271.5    1085  1374.8  1083.3  1485.5  1088.8  1513.2  1088.4  1634.6    1096
  1677.4  1095.7  1701.5  1098.7  1815.8  1104.2    1935  1115.6  2239.7  1133.6
#Mann= 3 , 0 , 0
       0     .09       0  1159.5    .047       0  1222.5     .09       0
#XS Ineff= 2 , 0
       0  1106.2    1087  1278.9       0    1087
Permanent Ineff=
       F       F
Bank Sta=1159.5,1222.5
Exp/Cntr=0.5,0.3

Type RM Length L Ch R = 1 ,82232.19,478.53,478.53,191.86
XS GIS Cut Line= 5
  1338969.999086   806493.838332  1337949.074029   806254.184572
  1337781.316461    806100.80614  1337134.427756   806340.292604
  1336036.540779   805874.627452
#Sta/Elev= 30
       0 1118.28   21.73 1121.82   83.11 1121.71  185.25 1131.08  244.43 1132.38
  296.51 1127.77  398.96 1110.01  535.61 1097.03  680.95 1091.72  718.74 1094.82
  759.64 1093.29  841.07 1101.76  942.13 1098.56 1088.16 1084.94 1249.68 1079.22
 1436.01 1083.08 1456.94 1074.64 1476.62 1072.62 1495.95    1075 1510.95 1081.91
 1681.49 1081.82 1709.37 1083.82 1797.49 1099.06 2012.38 1117.91 2230.87 1130.99
 2607.75 1145.27 2866.41 1141.55 3012.92 1128.05 3087.02 1118.64 3158.34 1100.39
#Mann= 3 , 0 , 0
       0     .09       0 1436.01    .047       0 1510.95     .09       0
#XS Ineff= 2 , 0
                         1961.37         1122.42
Permanent Ineff=
       F       F
Bank Sta=1436.01,1510.95
Exp/Cntr=0.3,0.1

Type RM Length L Ch R = 1 ,81753.66,757.45,757.45,699.85
XS GIS Cut Line= 5
  1339137.756782   806426.735228  1338404.416238   806297.322236
  1338020.970221   806172.702204  1337628.421357    805462.10278
  1336497.213932   804555.405435
#Sta/Elev= 30
       0 1103.61  108.39 1104.23  192.05 1108.63  312.19 1123.25  390.45 1129.12
  461.06  1123.5  568.93 1097.77  611.97 1091.65  705.28 1084.61 1053.03  1084.3
 1329.74 1079.11 1493.77 1081.08 1531.93 1084.21  1556.6 1080.87 1574.53 1074.11
 1604.39 1071.44 1625.95 1071.77 1636.06 1082.69 1644.47 1083.19  1668.1 1083.46
 1749.66  1099.3 1803.18 1105.15 1962.88 1110.78 2489.11 1160.77 2543.91 1163.19
 2666.33 1159.63 3180.32 1107.52 3244.18 1107.43  3279.3 1112.65 3409.41  1118.9
#Mann= 3 , 0 , 0
       0     .09       0 1531.93    .047       0 1644.47     .08       0
Bank Sta=1531.93,1644.47
Exp/Cntr=0.3,0.1

Type RM Length L Ch R = 1 ,80996.22,515.12,515.12,512.91
XS GIS Cut Line= 4
  1339113.791342   806374.011388   1338610.51851   806273.356796
  1338500.277742   805616.705532  1338208.003565   805241.342459
#Sta/Elev= 30
       0 1099.12   76.56 1099.63  109.28 1102.57  142.21 1103.39   269.4 1119.22
  324.45 1121.83  443.85 1114.79  474.63 1108.79  513.24    1098  568.46  1087.5
  597.98 1082.95   624.6 1080.86   914.3 1078.27  996.16 1081.19 1001.44 1072.99
 1006.37  1071.2 1026.56  1070.2 1046.95  1071.2 1068.72 1081.22 1109.77 1100.63
 1124.63 1111.31  1139.4 1113.43 1208.47 1130.87 1221.46 1131.48 1267.37 1138.76
 1345.87 1145.53 1438.53 1146.44 1540.74 1153.32 1608.17 1153.21 1654.81 1149.44
#Mann= 3 , 0 , 0
       0     .12       0  996.16    .048       0 1068.72     .09       0
Bank Sta=996.16,1068.72
Exp/Cntr=0.3,0.1

Type RM Length L Ch R = 1 ,80481.09,795.7,795.7,1083.33
XS GIS Cut Line= 4
  1339645.822703   806484.252156  1339070.653678   806215.839996
   1338960.41291   805707.773948  1338701.586926   805444.154747
#Sta/Elev= 30
       0  1090.9    92.8 1092.63  175.94 1101.68  314.08 1109.58  488.42 1096.13
  535.01 1091.06  581.72 1089.16   613.8 1091.36  641.13 1088.59  721.86 1085.47
  746.95 1081.06  762.31 1079.61  825.61 1077.97  908.43 1078.74   914.6 1076.11
  920.52 1072.07   946.8 1070.08  965.38 1072.04  980.27 1075.85 1002.77 1076.92
 1016.33 1074.73 1030.83 1075.33 1059.99 1082.77 1073.08 1082.92  1154.6 1100.71
 1191.39 1107.41 1251.41 1116.23  1322.6 1125.37 1470.08 1141.66 1524.04 1145.02
#Mann= 3 , 0 , 0
       0      .1       0   914.6    .047       0  980.27     .09       0
Bank Sta=914.6,980.27
Exp/Cntr=0.3,0.1

Type RM Length L Ch R = 1 ,79685.4 ,490.51,490.51,360.93
XS GIS Cut Line= 3
  1340101.164783   806407.562876  1339602.685039   805285.983355
   1338797.44843   805353.086459
#Sta/Elev= 30
       0 1150.67  130.59  1155.3  205.74 1152.96  323.39  1152.9   433.9 1145.48
  694.98 1138.19  895.74 1137.39  963.34 1132.97 1061.45  1123.1 1154.34 1126.43
  1205.8 1126.16 1256.81 1121.71 1300.83 1114.08 1394.22 1093.07    1434 1080.66
 1482.99 1072.71  1504.5 1069.01 1588.25 1068.94 1596.84    1073 1598.25 1075.19
 1599.62 1078.21 1634.25  1082.5 1728.83 1102.44 1787.05 1110.29 1818.63 1117.42
 1840.06 1118.07  1880.2 1125.83 1917.49 1127.54  1951.9 1133.18 2035.39  1138.6
#Mann= 3 , 0 , 0
       0     .09       0 1482.99    .047       0 1598.25     .11       0
Bank Sta=1482.99,1598.25
Exp/Cntr=0.3,0.1

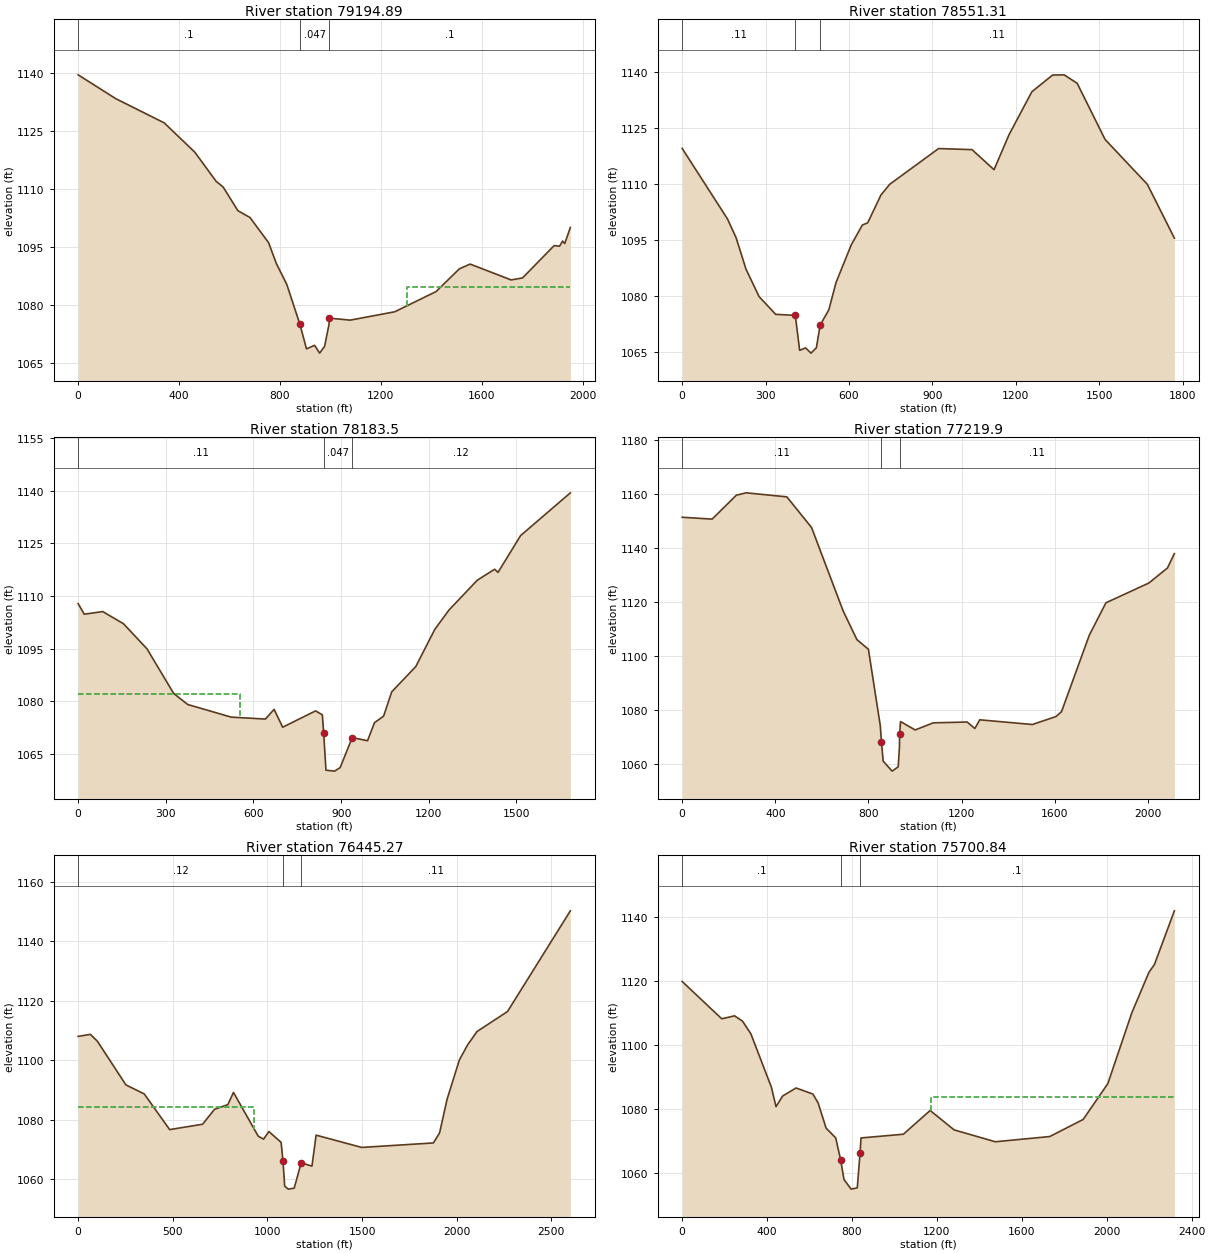
Type RM Length L Ch R = 1 ,79194.89,643.58,643.58,392.17
XS GIS Cut Line= 4
  1339843.346543    805552.79462  1339436.177134   804867.737851
  1338987.103086   804751.997179  1338297.288173   804733.478651
#Sta/Elev= 30
       0  1139.6  149.65 1133.41  340.92 1127.17  462.47 1119.57   546.8 1112.04
  574.68 1110.56  633.05 1104.43  681.16 1102.66  754.75 1096.16   786.1 1090.67
  826.99 1085.33  879.12 1074.98  904.96 1068.66  937.24 1069.58  957.06 1067.56
  976.89 1069.34  994.32 1075.02   996.1 1076.62 1078.05  1076.1 1254.77 1078.26
 1418.42 1083.49 1510.75 1089.37 1553.45 1090.61 1716.06 1086.51 1761.27 1087.03
 1886.48 1095.39 1907.91 1095.23  1920.1 1096.57 1928.56 1095.93 1950.74 1100.07
#Mann= 3 , 0 , 0
       0      .1       0  879.12    .047       0   996.1      .1       0
#XS Ineff= 2 , 0
                         1303.59         1084.62
Permanent Ineff=
       F       F
Bank Sta=879.12,996.1
Exp/Cntr=0.3,0.1

Type RM Length L Ch R = 1 ,78551.31,367.81,367.81,374.21
XS GIS Cut Line= 3
  1339700.917999   805149.247227  1339834.889199   804523.884411
  1338756.142062   804185.480826
#Sta/Elev= 30
       0 1119.63  163.01 1100.71  194.02 1095.67   229.6 1087.24  276.46 1079.91
  336.22 1075.14  406.96 1074.86  422.45 1065.49  443.97 1066.14  463.29 1064.74
  482.62 1066.17  496.22 1072.24  527.67 1076.39  553.18 1083.65  608.12 1093.78
  647.99 1099.09  667.22 1099.68  714.82 1107.14  746.36 1110.01  922.11 1119.59
 1042.39  1119.3 1121.57 1113.92 1175.91 1123.37 1257.74 1134.83 1332.17  1139.3
 1373.55 1139.36  1420.5  1137.1 1520.95 1122.03 1672.88 1110.01 1770.13 1095.59
#Mann= 3 , 0 , 0
       0     .11       0  406.96    .047       0  496.22     .11       0
Bank Sta=406.96,496.22
Exp/Cntr=0.3,0.1

Type RM Length L Ch R = 1 ,78183.5 ,963.6,963.6,1056.48
XS GIS Cut Line= 4
  1340208.913135   805661.989884  1340094.970351   805106.518651
  1340199.417839   804527.309307  1339776.879983   804209.218938
#Sta/Elev= 30
       0 1107.83   20.97 1104.83   84.26 1105.57  155.32  1102.1  235.74 1094.96
  326.88 1082.29  375.11 1079.14  523.69 1075.55  640.64    1075  670.66 1077.75
  699.98 1072.68   812.5 1077.32  835.79  1076.2  840.22 1071.05  848.11 1060.46
  877.56 1060.19  896.65 1061.19  938.09 1069.73  990.33 1068.84 1014.11 1073.96
 1045.32 1075.82 1073.21 1082.75 1155.59 1089.94 1220.67 1100.52 1269.29 1106.03
 1366.03  1114.5 1425.53 1117.62 1436.93 1116.72 1514.23 1127.19 1684.47 1139.35
#Mann= 3 , 0 , 0
       0     .11       0  840.22    .047       0  938.09     .12       0
#XS Ineff= 2 , 0
          554.61 1081.99
Permanent Ineff=
       F       F
Bank Sta=840.22,938.09
Exp/Cntr=0.3,0.1

Type RM Length L Ch R = 1 ,77219.9 ,774.63,774.63,827.27
XS GIS Cut Line= 5
   1340935.15992   805721.744124  1341001.765232   805025.809147
  1340840.346224   804769.437819  1340743.436912   804619.336699
  1339942.993391   804140.029306
#Sta/Elev= 30
       0 1151.48  128.59 1150.79  232.79 1159.67  275.03 1160.54  449.57 1159.04
  555.72 1147.66  691.05 1116.77  750.35  1106.1  799.77 1102.52  850.94  1074.1
  855.63 1068.23  863.24 1061.03  901.61 1057.32  927.76 1058.91  933.08 1066.43
  934.04 1071.13   937.6 1075.71 1000.47 1072.59 1078.42 1075.23 1224.03 1075.53
 1256.78 1073.13    1278 1076.35 1503.75 1074.61 1605.14 1077.56  1629.1 1079.38
 1748.18  1107.7 1819.82 1119.75 2004.23 1127.09 2084.06 1132.67 2113.71    1138
#Mann= 3 , 0 , 0
       0     .11       0  855.63    .047       0  934.04     .11       0
Bank Sta=855.63,934.04
Exp/Cntr=0.3,0.1

Type RM Length L Ch R = 1 ,76445.27,744.44,744.44,876.89
XS GIS Cut Line= 3
  1341788.327281   805204.501115    1341463.9548   804279.774842
  1339962.165615    803670.71705
#Sta/Elev= 30
       0 1107.99   64.82 1108.68   101.9 1106.34  252.43 1091.67  349.21 1088.64
  483.45 1076.65  657.53 1078.45  720.53 1083.47  791.08 1085.05  820.68 1089.15
  951.25 1074.45  979.97 1073.44 1007.69    1076 1072.38 1072.36  1082.1 1066.19
 1091.37 1057.63 1110.45 1056.63  1141.6 1056.97  1178.3  1065.5 1235.31 1064.36
 1257.27 1074.78  1498.3 1070.65 1877.08 1072.16 1909.75 1075.55 1949.21 1086.84
 2014.17 1100.05 2057.65 1105.12 2107.76 1109.64 2268.66 1116.35 2600.56 1150.21
#Mann= 3 , 0 , 0
       0     .12       0  1082.1    .047       0  1178.3     .11       0
#XS Ineff= 2 , 0
          930.36 1084.32
Permanent Ineff=
       F       F
Bank Sta=1082.1,1178.3
Exp/Cntr=0.3,0.1

Type RM Length L Ch R = 1 ,75700.84,634.96,634.96,638.87
XS GIS Cut Line= 2
  1342263.723377   803647.830522  1339952.579567   803464.614778
#Sta/Elev= 30
       0 1119.77  186.42 1108.13  246.62 1109.05  284.02 1107.41  323.71 1103.43
  420.56 1086.72  441.91 1080.71  473.41 1084.04  536.34 1086.54  615.68 1084.65
  640.31 1081.89     678    1074  723.13 1070.98  746.11 1064.21  762.29 1057.97
  795.78 1054.98  824.82 1055.38  837.87 1066.27   842.4 1070.95 1041.83 1072.11
 1168.07 1079.52 1280.71 1073.47 1475.17 1069.76  1731.4 1071.39 1888.81 1076.72
 2005.02 1087.91 2117.86 1109.98 2198.44 1122.62 2224.66 1125.09 2318.39 1141.82
#Mann= 3 , 0 , 0
       0      .1       0  746.11    .047       0  837.87      .1       0
#XS Ineff= 2 , 0
                         1172.47         1083.83
Permanent Ineff=
       F       F
Bank Sta=746.11,837.87
Exp/Cntr=0.3,0.1

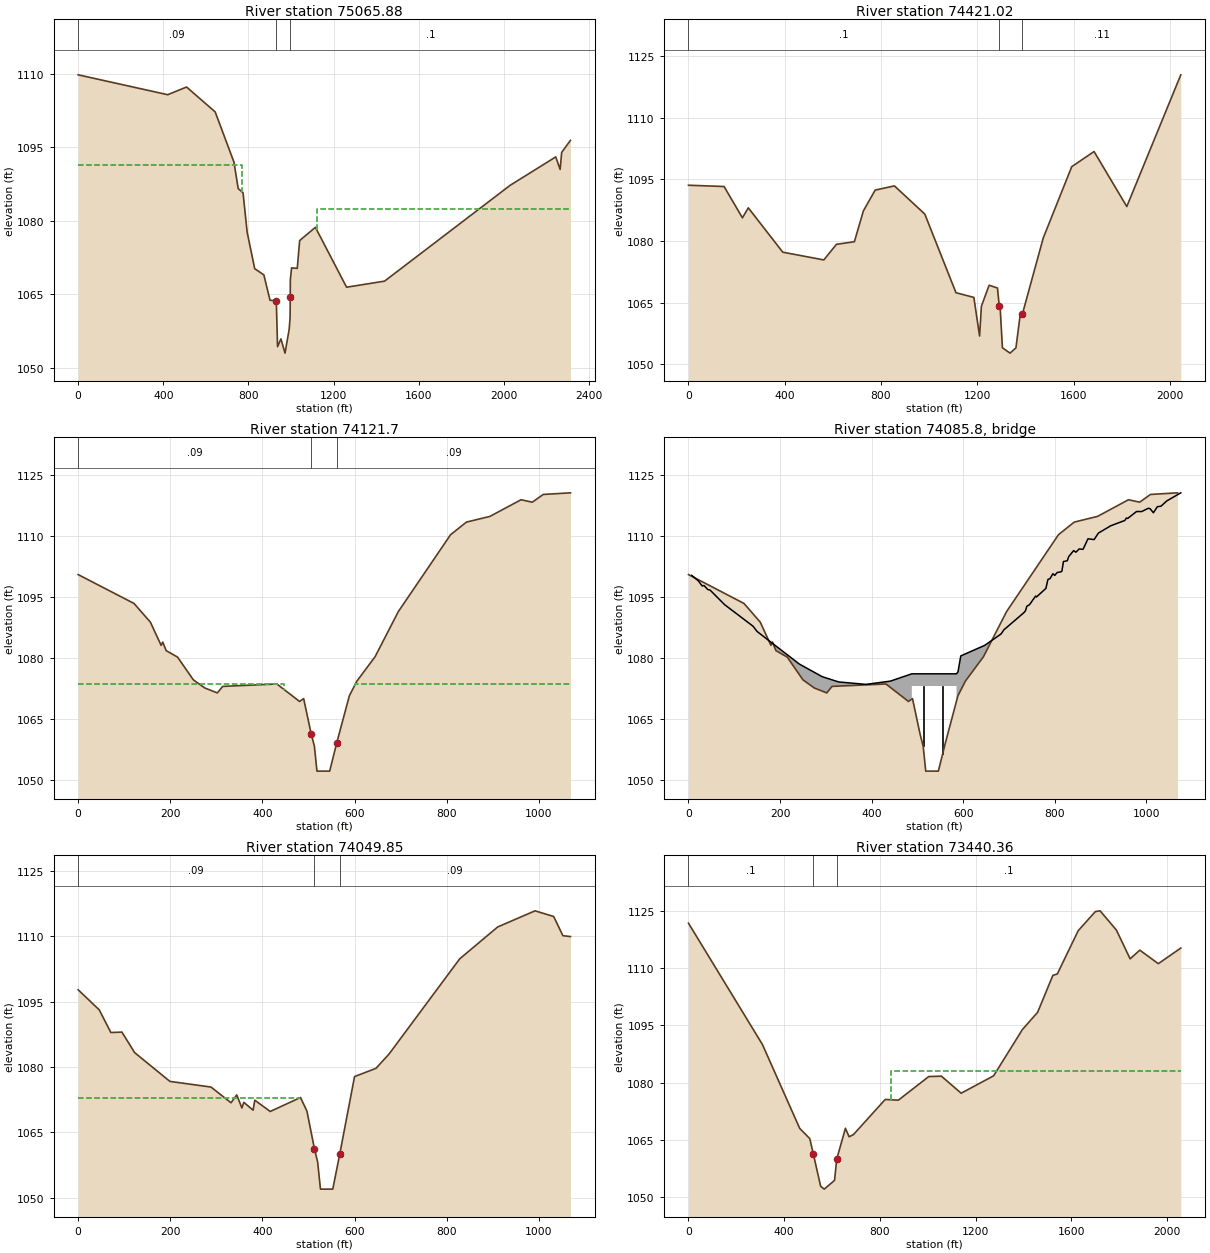
Type RM Length L Ch R = 1 ,75065.88,644.86,644.86,594.52
XS GIS Cut Line= 3
  1342301.186417   803248.926329  1341695.291633   803000.695033
  1340048.441071   802812.756473
#Sta/Elev= 30
       0 1109.79  420.62 1105.73  509.28  1107.3  643.55 1102.22  731.71 1091.98
  751.71 1086.56  774.42 1085.71  793.75 1077.67  829.27  1070.2  872.19 1068.94
  901.21 1063.76  930.65 1063.62  936.61 1054.28   952.5 1055.87  971.62 1052.96
  991.12 1057.82   995.4 1060.14  996.31  1064.5  996.58 1067.92 1002.45 1070.37
 1029.13 1070.27 1040.45 1075.95 1114.33 1078.65 1260.74 1066.42 1439.19 1067.66
  2028.8 1087.22 2243.32 1093.03 2263.78 1090.48 2271.08 1093.95 2312.31 1096.41
#Mann= 3 , 0 , 0
       0     .09       0  930.65    .047       0  996.31      .1       0
#XS Ineff= 2 , 0
          769.86 1091.46 1120.78         1082.46
Permanent Ineff=
       F       F
Bank Sta=930.65,996.31
Exp/Cntr=0.3,0.1

Type RM Length L Ch R = 1 ,74421.02,299.32,299.32,282.82
XS GIS Cut Line= 4
  1342689.425522   802994.893305  1341977.699057   802579.398777
  1341880.476913   802482.176505  1340866.587888   802097.917304
#Sta/Elev= 30
       0 1093.55  147.82 1093.24  224.15 1085.63  248.52 1088.06  391.78 1077.28
  562.43  1075.4  614.82 1079.19  689.39 1079.82  726.76  1087.3  775.76 1092.37
  855.84 1093.39  982.02 1086.54 1111.57 1067.43 1185.89 1066.29 1209.71 1056.91
 1217.23 1064.15 1249.32 1069.25 1284.13 1068.57 1291.22  1064.3 1295.33 1063.69
  1304.6 1054.05 1336.11 1052.75 1360.78 1054.03 1377.44 1061.62 1387.43 1062.21
 1474.17 1080.71 1592.67 1098.06  1685.4 1101.74  1821.5 1088.37 2045.89 1120.38
#Mann= 3 , 0 , 0
       0      .1       0 1291.22    .047       0 1387.43     .11       0
Bank Sta=1291.22,1387.43
Exp/Cntr=0.5,0.3

Type RM Length L Ch R = 1 ,74121.7 ,71.85,71.85,71.1
BEGIN DESCRIPTION:
Upstream xs of Bridge 37003-0025
END DESCRIPTION:
XS GIS Cut Line= 2
  1342275.177201   802385.606009  1340910.593776   801737.168504
#Sta/Elev= 30
       0  1100.4 121.198  1093.3 156.766  1088.7 180.029    1083 183.565  1083.8
  190.99  1081.7 215.738  1080.1 250.104  1074.5 275.065  1072.5 302.076  1071.3
 313.531  1072.9 431.264  1073.5 480.479  1069.2 489.318  1069.9 505.581  1061.3
 512.652  1058.2  518.21 1052.07  545.81 1052.07  561.25 1059.06 588.525  1070.6
 604.859  1074.2 644.316  1080.2 694.803  1091.3 808.152  1110.2 842.518  1113.3
 893.429  1114.7 961.099  1118.8 985.495  1118.21009.183  1120.11068.297  1120.5
#Mann= 3 , 0 , 0
       0     .09       0 505.581    .047       0  561.25     .09       0
#XS Ineff= 2 , 0
       0  447.23  1073.4 599.909       0  1073.4
Permanent Ineff=
       F       F
Bank Sta=505.581,561.25
Skew Angle= 45
Exp/Cntr=0.5,0.3

Type RM Length L Ch R = 3 ,74085.8 ,,,
BEGIN DESCRIPTION:
Bridge : 37003-0025 - SR-1318 / Z Walts
END DESCRIPTION:
Bridge Culvert--1,0,-1,-1, 0
Deck Dist Width WeirC Skew NumUp NumDn MinLoCord MaxHiCord MaxSubmerge Is_Ogee
20.4,31,2.6,45, 60, 60, , , 0.95, 0, 0,0,,
   7.071  21.072  29.911  34.012  42.285  47.023  78.913 140.997 149.907 242.113
 291.894 327.885 387.636 441.022 487.904 487.904 585.484 585.484 588.737 594.747
 647.144 682.782 688.793  732.28 736.098 738.997 744.937  758.16  760.21 780.717
 785.101 789.626  795.99 800.021 805.182 814.375 815.718 819.042 827.456 830.426
 841.386 846.124 853.336 861.822  872.64 886.005 895.409  922.35 952.968 956.574
 959.332 978.636  990.021004.3041008.1931015.4761024.2441031.9521044.6091075.368
  1100.2  1098.9  1097.6  1097.7  1096.7  1096.6    1093  1087.7  1086.4  1078.4
  1075.3    1074  1073.4  1074.2    1076    1076    1076    1076  1076.5  1080.4
    1083  1085.8  1086.8    1091  1091.5  1092.6    1093  1095.1  1094.9    1097
  1099.2  1099.4  1100.6  1100.2  1100.9  1101.1  1101.3  1103.6  1103.8  1104.8
  1106.3  1105.9  1106.7  1106.6  1109.2    1109  1110.6  1112.4  1113.7  1114.3
  1114.2  1115.9  1115.9  1116.7  1116.6  1115.6  1117.1  1117.2  1118.5  1120.5
                                                                                
                                            1073    1073
                                                                                
                                                                                
                                                                                
                                                                                
  14.142  28.143  36.982  41.083  49.356  54.094  85.984 148.068 156.978 249.184
 298.965 334.956 394.707 448.094 494.975 494.975 592.555 592.555 595.808 601.819
 654.215 689.853 695.864 739.351 743.169 746.068 752.008 765.231 767.282 787.788
 792.172 796.697 803.061 807.092 812.254 821.446 822.789 826.113 834.527 837.497
 848.457 853.195 860.408 868.893 879.711 893.076  902.48 929.421 960.039 963.645
 966.403 985.707 997.0911011.3751015.2641022.5471031.3151039.023 1051.681082.439
  1100.2  1098.9  1097.6  1097.7  1096.7  1096.6    1093  1087.7  1086.4  1078.4
  1075.3    1074  1073.4  1074.2    1076    1076    1076    1076  1076.5  1080.4
    1083  1085.8  1086.8    1091  1091.5  1092.6    1093  1095.1  1094.9    1097
  1099.2  1099.4  1100.6  1100.2  1100.9  1101.1  1101.3  1103.6  1103.8  1104.8
  1106.3  1105.9  1106.7  1106.6  1109.2    1109  1110.6  1112.4  1113.7  1114.3
  1114.2  1115.9  1115.9  1116.7  1116.6  1115.6  1117.1  1117.2  1118.5  1120.5
                                                                                
                                            1073    1073
                                                                                
                                                                                
                                                                                
                                                                                
Pier Skew, UpSta & Num, DnSta & Num=  ,512.652, 2 ,519.723, 2 , 0 , 0 , 0 ,,
       3       3
  1057.2  1073.5
       3       3
  1057.2  1073.5
Pier Skew, UpSta & Num, DnSta & Num=  ,555.079, 2 ,562.15, 2 , 0 , 0 , 0 ,,
       3       3
  1054.9  1073.5
       3       3
  1054.9  1073.5
BR Coef=-1 , 1 , 0 ,, 0 ,,,0.8,0,1.2,0,
WSPro=,,,, 1 ,,,, 0 ,,,, 0 ,,,,-1 ,-1 ,-1 , 0 , 0 , 0 , 0 , 0
BC Design=,, 0 ,, 0 ,,,,,,

Type RM Length L Ch R = 1 ,74049.85,609.5,609.5,635.33
BEGIN DESCRIPTION:
Down stream xs of Bridge 37003-0025
END DESCRIPTION:
XS GIS Cut Line= 2
  1342305.220977   802322.381305   1340940.63768     801673.9438
#Sta/Elev= 30
       0  1097.7   45.75  1093.1  70.994  1087.9  94.964    1088 122.542  1083.3
 199.051  1076.7 288.287  1075.4 331.704  1071.8 344.149  1073.6  355.25  1070.6
 359.493  1071.9 379.716  1070.1 383.252  1072.4 416.769  1069.8  482.53    1073
 496.389  1069.9 512.652  1061.3 519.723  1058.2  525.81    1052  552.52    1052
   567.9 1060.15 599.768  1077.8 646.437  1079.7 674.863    1083 828.022  1104.8
 910.329  1112.1 991.505  1115.81031.881  1114.51051.892  1110.11068.297  1109.9
#Mann= 3 , 0 , 0
       0     .09       0 512.652    .047       0   567.9     .09       0
#XS Ineff= 2 , 0
       0  480.55    1073  606.98       0    1073
Permanent Ineff=
       F       F
Bank Sta=512.652,567.9
Skew Angle= 45
Exp/Cntr=0.5,0.3

Type RM Length L Ch R = 1 ,73440.36,810.44,810.44,767.95
XS GIS Cut Line= 5
  1342286.807153   801580.936184  1341551.773168   801352.546936
  1341348.069488   801380.324728  1341042.513904   801343.287672
  1340320.291695   801065.509879
#Sta/Elev= 30
       0 1121.81  308.87    1090  464.68 1067.99  506.79 1065.31  521.22 1061.38
  552.11 1052.82  567.12 1052.06  610.19 1054.36  619.44 1059.94  655.65 1068.02
  671.04 1065.79  688.88 1066.35  821.89 1075.58  876.72 1075.39 1003.88 1081.59
  1056.6 1081.69 1139.27 1077.22 1274.77 1081.78 1395.21 1093.93 1458.78 1098.45
 1522.48 1108.14 1540.85 1108.49 1628.26 1119.85 1699.93 1124.87 1719.76 1125.06
 1787.85 1120.01 1845.22 1112.47 1885.52 1114.75 1962.93  1111.2 2056.88 1115.29
#Mann= 3 , 0 , 0
       0      .1       0  521.22    .047       0  619.44      .1       0
#XS Ineff= 2 , 0
                          846.03         1083.05
Permanent Ineff=
       F       F
Bank Sta=521.22,619.44
Exp/Cntr=0.3,0.1

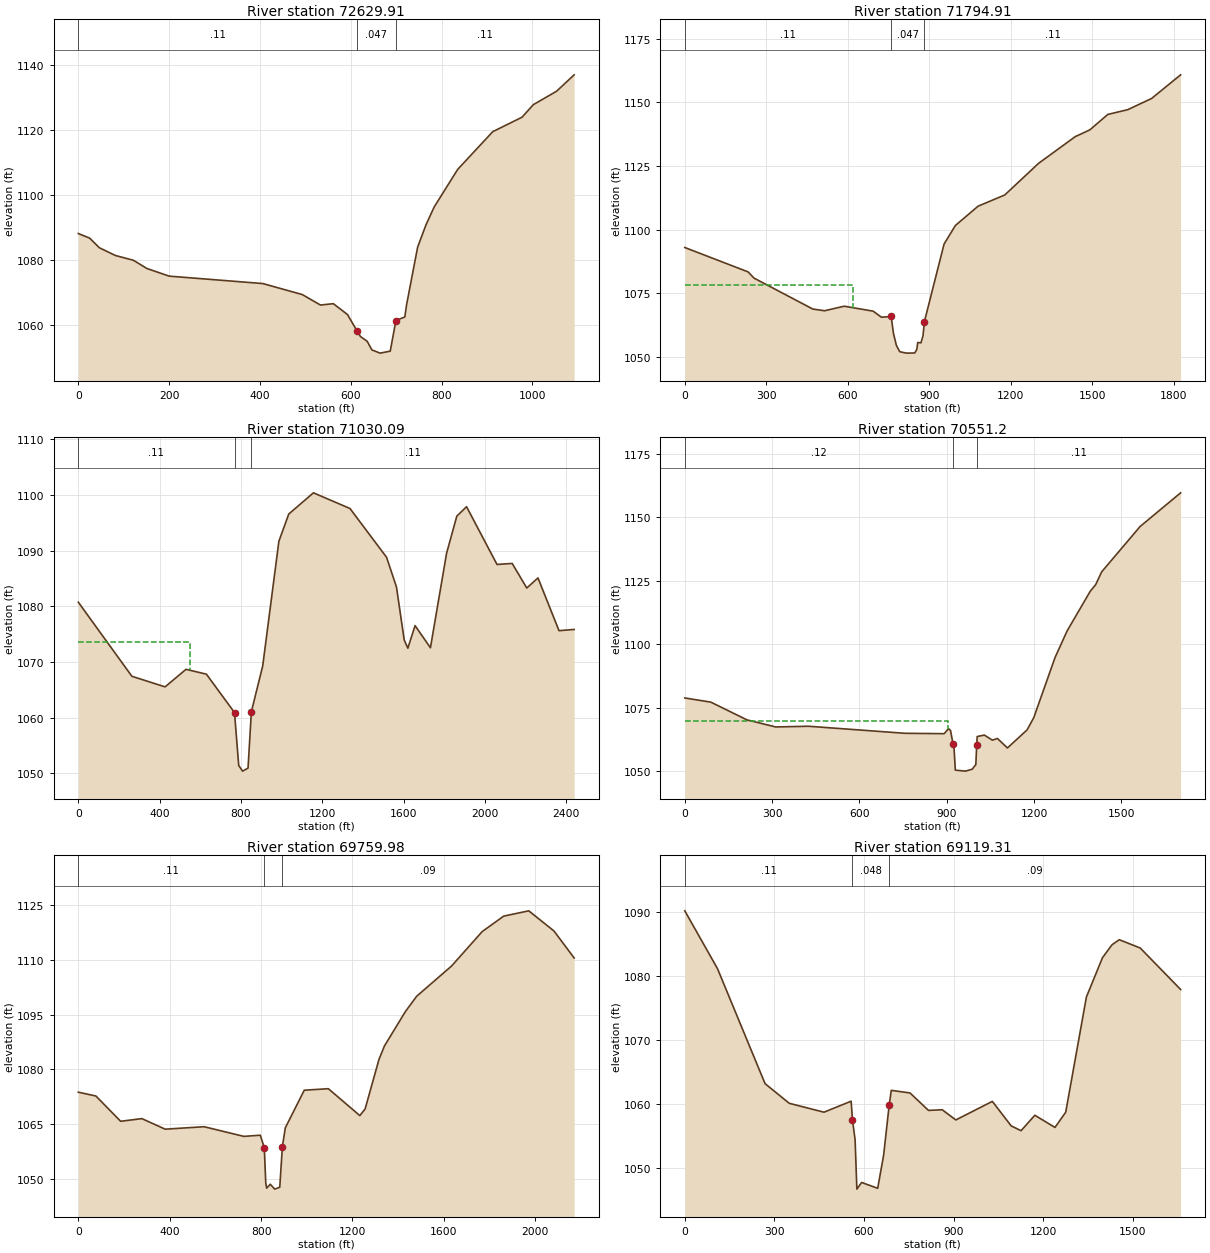
Type RM Length L Ch R = 1 ,72629.91,835,835,798.47
XS GIS Cut Line= 3
  1342423.128945   800985.554807  1341946.525809   800719.163511
  1341468.807792   800454.762359
#Sta/Elev= 30
       0 1088.15   25.01 1086.74   46.18  1083.8    81.4 1081.42  121.37 1079.94
  151.06 1077.41  200.02 1075.07  406.34 1072.79  493.26 1069.41  533.22  1066.2
  561.66 1066.61  592.88 1063.27  613.28 1058.37  621.37 1056.53  636.16 1055.07
  646.44 1052.43  664.52 1051.43  686.93 1052.04  699.43 1061.44  719.13 1062.54
  722.79 1066.18  747.31 1083.99  765.62  1090.8  783.62 1096.28  835.53 1107.85
  912.75 1119.43  977.16 1123.86 1002.08 1127.72 1053.33 1131.85    1092 1136.88
#Mann= 3 , 0 , 0
       0     .11       0  613.28    .047       0  699.43     .11       0
Bank Sta=613.28,699.43
Exp/Cntr=0.3,0.1

Type RM Length L Ch R = 1 ,71794.91,764.83,764.83,720.04
XS GIS Cut Line= 3
  1342920.509042   800430.543735  1341976.064625   799754.617846
  1341314.027632   799800.914166
#Sta/Elev= 30
       0 1092.96  233.01 1083.36  254.69 1080.93  471.18 1068.75   514.6 1068.08
  586.88 1069.87  693.26 1067.92  723.84 1065.53  759.61 1065.82  768.17 1059.12
  778.79 1054.47  791.13 1051.97  815.71 1051.41  846.36 1051.47  854.02 1052.88
  857.43 1055.59  869.17 1055.46  876.86 1058.25  881.92 1063.78  954.33 1094.31
  996.11 1101.63 1079.54 1109.21 1177.77 1113.62 1302.38 1126.08 1437.08 1136.56
 1490.76 1139.22 1557.02  1145.3 1630.74 1147.18 1718.28 1151.58 1825.05 1160.88
#Mann= 3 , 0 , 0
       0     .11       0  759.61    .047       0  881.92     .11       0
#XS Ineff= 2 , 0
          620.24  1078.3
Permanent Ineff=
       F       F
Bank Sta=759.61,881.92
Exp/Cntr=0.3,0.1

Type RM Length L Ch R = 1 ,71030.09,478.89,478.89,447.97
XS GIS Cut Line= 3
  1343157.927794   799959.191798  1342551.446257   799181.414006
  1341107.710704   799026.227062
#Sta/Elev= 30
       0 1080.75  263.35 1067.45  426.63 1065.55  529.62  1068.7  629.85 1067.83
  767.99 1060.94  788.79 1051.43  807.71 1050.42  834.55 1050.96  851.01  1061.1
  906.71  1069.3  986.29  1091.7 1034.81 1096.58 1156.21 1100.39 1336.11 1097.57
  1515.9 1088.81 1564.36  1083.5 1602.68 1073.97 1620.52 1072.49 1655.93 1076.55
 1731.57 1072.57 1810.95 1089.54 1861.21  1096.2 1909.19  1097.9 2058.94 1087.53
 2133.64 1087.71 2205.27  1083.3 2260.55 1085.11 2363.83 1075.64 2438.34 1075.86
#Mann= 3 , 0 , 0
       0     .11       0  767.99    .048       0  851.01     .11       0
#XS Ineff= 2 , 0
          549.51 1073.64
Permanent Ineff=
       F       F
Bank Sta=767.99,851.01
Exp/Cntr=0.3,0.1

Type RM Length L Ch R = 1 ,70551.2 ,791.22,791.22,381.71
XS GIS Cut Line= 3
  1343223.069426   800014.583926  1343213.810162   799334.028406
  1342715.655154   798440.863477
#Sta/Elev= 30
       0 1078.84   89.41 1077.19  213.81 1070.19  312.43 1067.41  424.85 1067.69
  756.02 1064.91  891.07 1064.76  905.95 1066.74  912.74 1066.07  921.62 1060.68
  925.04 1058.91  929.32 1050.39  964.27    1050  987.34 1050.76  999.72 1052.58
 1002.83 1060.19 1004.39 1063.63 1028.99 1064.21 1056.65 1062.21 1073.94 1062.87
 1108.33 1059.13 1175.73 1066.23 1198.72 1071.05 1272.06 1094.83 1313.75 1105.33
 1393.02 1120.92 1411.73 1123.54 1431.86 1128.51 1564.17 1146.42 1703.31 1159.69
#Mann= 3 , 0 , 0
       0     .12       0  921.62    .048       0 1002.83     .11       0
#XS Ineff= 2 , 0
          905.48 1069.94
Permanent Ineff=
       F       F
Bank Sta=921.62,1002.83
Exp/Cntr=0.3,0.1

Type RM Length L Ch R = 1 ,69759.98,640.66,640.66,759.6
XS GIS Cut Line= 4
  1343269.387506   800037.565942  1343298.146034   799414.466166
  1343729.522802   799356.949238   1343628.86821   798249.748853
#Sta/Elev= 30
       0 1073.78   76.95 1072.73  185.26 1065.82  278.09 1066.55  380.33 1063.66
  550.66 1064.33  724.76 1061.69  796.76 1062.01  814.11 1058.56  820.63 1048.96
  824.56 1047.53  840.16  1048.6  859.85 1047.26  881.88 1047.78  893.26 1058.86
  906.09 1064.02  989.23 1074.32 1094.63 1074.73 1232.38 1067.38 1255.55 1069.19
 1316.02  1082.7 1340.06 1086.41 1432.08 1095.85 1481.38 1100.03 1634.16  1108.3
 1768.05 1117.71 1862.31 1121.94 1972.05 1123.39 2081.96  1117.9 2170.72  1110.5
#Mann= 3 , 0 , 0
       0     .11       0  814.11    .048       0  893.26     .09       0
Bank Sta=814.11,893.26
Exp/Cntr=0.3,0.1

Type RM Length L Ch R = 1 ,69119.31,660.96,660.96,932.87
XS GIS Cut Line= 3
  1343204.550898   800394.213623  1343894.365683   799783.102454
  1343873.315059   799045.399414
#Sta/Elev= 30
       0 1090.24   109.5  1081.2  268.66 1063.24   349.6 1060.17  465.92 1058.78
  556.77  1060.5  561.25 1057.57  570.02 1054.48  575.95 1046.76  591.82  1047.8
  645.68 1046.89  665.53 1052.07  683.97 1059.83  691.09 1062.19  753.75 1061.79
  815.67 1059.06  861.69 1059.16  907.25 1057.57 1029.39 1060.47  1092.5 1056.64
 1125.43 1055.89 1171.64  1058.3 1239.08  1056.4 1274.99 1058.78 1344.14 1076.76
 1398.03 1082.92 1430.07 1084.94 1454.23 1085.73 1524.43 1084.43 1659.58 1077.95
#Mann= 3 , 0 , 0
       0     .11       0  561.25    .048       0  683.97     .09       0
Bank Sta=561.25,683.97
Exp/Cntr=0.3,0.1

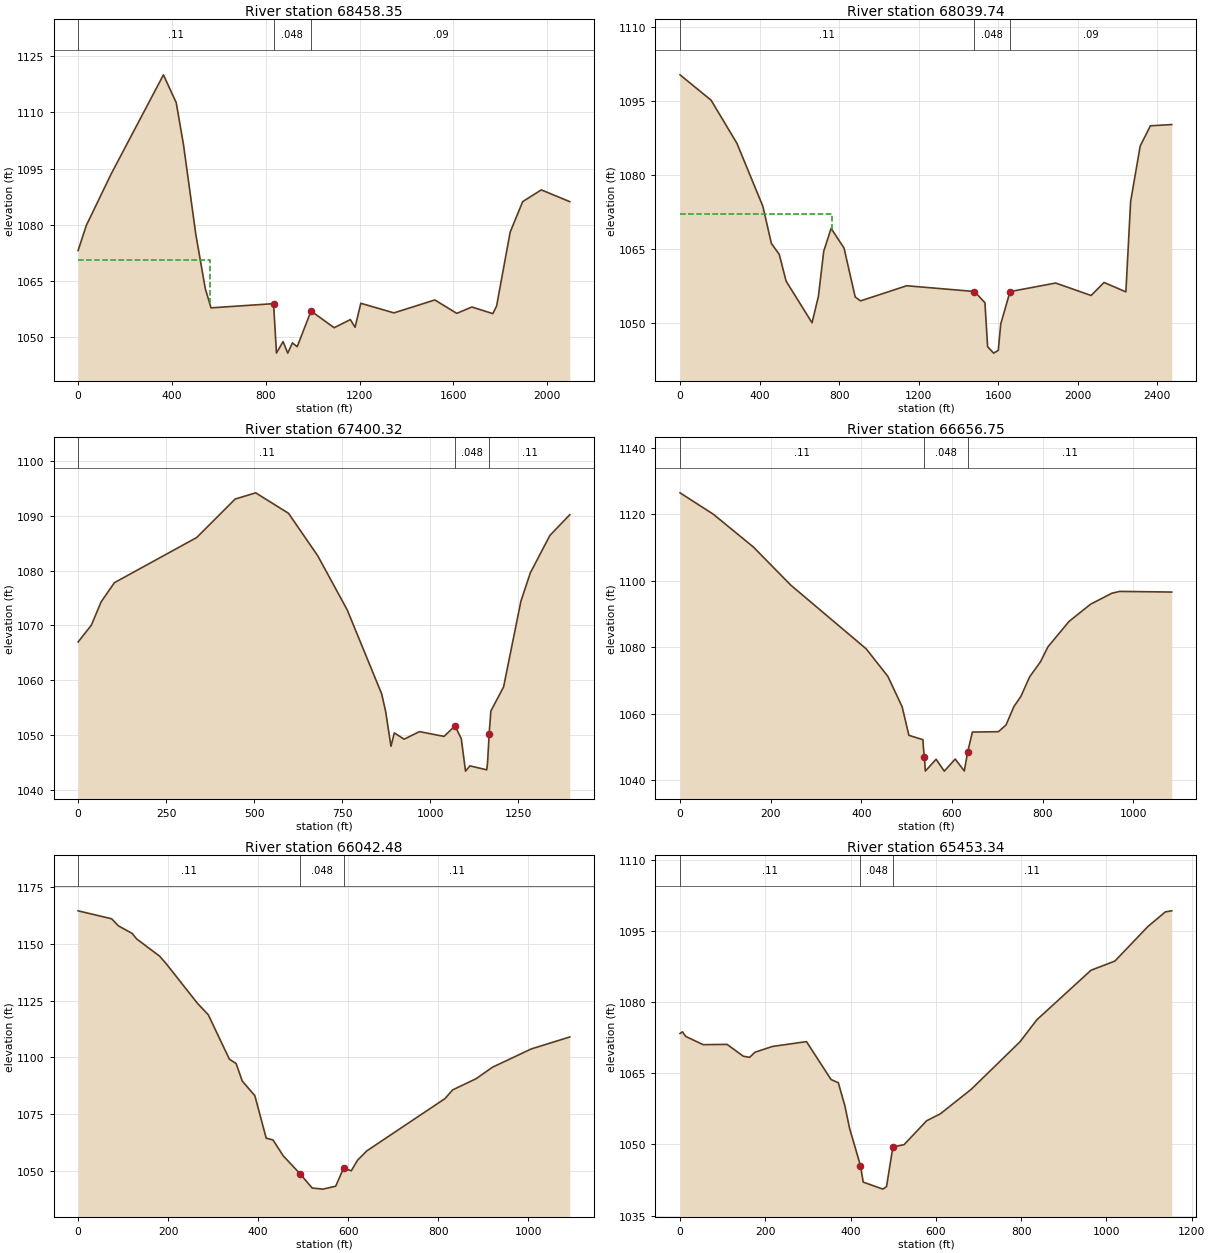
Type RM Length L Ch R = 1 ,68458.35,418.61,418.61,552.01
XS GIS Cut Line= 3
  1344453.283187   801080.538871  1343936.032371   799903.472886
  1343935.625075   799093.330166
#Sta/Elev= 30
       0 1073.16   34.76 1079.82     141  1093.6  363.67 1120.03  418.19 1112.61
  448.92 1101.48  501.81 1077.41  542.05 1062.98  566.51 1057.85  833.14 1058.97
  845.38  1045.8  873.67 1048.84  893.56 1045.77  913.39  1048.5  933.78 1047.49
  992.87    1057  1091.4 1052.55 1160.29 1054.72 1180.52 1052.66 1204.98 1059.07
 1346.27 1056.51 1520.49 1059.96    1614 1056.38  1678.4 1058.08 1767.76 1056.31
 1783.76 1058.34 1841.69 1078.07 1894.92 1086.19 1974.24 1089.33 2095.85 1086.19
#Mann= 3 , 0 , 0
       0     .11       0  833.14    .048       0  992.87     .09       0
#XS Ineff= 2 , 0
          560.39 1070.53
Permanent Ineff=
       F       F
Bank Sta=833.14,992.87
Exp/Cntr=0.3,0.1

Type RM Length L Ch R = 1 ,68039.74,639.42,639.42,688.35
XS GIS Cut Line= 4
  1345274.621044   801014.072183  1344352.699123   799898.843254
  1344042.513907   799861.806198  1343993.142003   799150.847094
#Sta/Elev= 30
       0 1100.34  156.08 1095.19  285.96 1086.43  416.43 1073.63  459.17 1066.09
  498.83 1063.86  533.39 1058.42  663.76 1049.96  695.67 1055.33  722.39 1064.49
  759.55 1069.14  824.53 1065.15  880.56 1055.22  907.32 1054.41  1139.6 1057.49
 1480.42 1056.32 1532.99 1054.04 1546.43 1045.11 1576.74  1043.8 1599.98 1044.36
 1612.39 1049.73 1659.12  1056.3 1888.74 1058.04 2066.68 1055.51 2131.65 1058.15
 2241.63 1056.25 2265.49 1074.62 2313.66 1085.89 2364.75 1089.98 2472.01 1090.24
#Mann= 3 , 0 , 0
       0     .11       0 1480.42    .048       0 1659.12     .09       0
#XS Ineff= 2 , 0
          763.38    1072
Permanent Ineff=
       F       F
Bank Sta=1480.42,1659.12
Exp/Cntr=0.3,0.1

Type RM Length L Ch R = 1 ,67400.32,743.57,743.57,834.06
XS GIS Cut Line= 2
  1345398.059124   799532.815478  1344042.513907   799199.769078
#Sta/Elev= 30
       0 1066.99   37.46 1070.04   65.48 1074.33  103.06 1077.81  336.62 1086.05
  445.67 1093.07  504.11 1094.21  597.34 1090.47  680.36 1082.71  764.01 1072.83
  861.73 1057.52  873.13 1054.28  888.15 1047.95   897.7 1050.39  925.43 1049.24
  968.92 1050.62 1038.83 1049.75 1069.92 1051.66 1087.69 1049.36  1099.8 1043.41
 1112.28 1044.37 1159.97 1043.65 1162.39 1044.95 1166.92 1050.26 1171.81 1054.39
 1207.89 1058.79 1257.02 1074.42 1283.79  1079.6 1339.31 1086.43 1395.86 1090.22
#Mann= 3 , 0 , 0
       0     .11       0 1069.92    .048       0 1166.92     .11       0
Bank Sta=1069.92,1166.92
Exp/Cntr=0.3,0.1

Type RM Length L Ch R = 1 ,66656.75,614.27,614.27,614.56
XS GIS Cut Line= 2
  1345033.254644   798445.139445  1343968.439795   798653.472885
#Sta/Elev= 30
       0 1126.49   73.23 1120.07  161.77 1110.18  244.53 1098.67  410.82 1079.49
  458.66 1071.19  490.18 1062.02  505.04 1053.44  536.01 1052.12   537.1 1049.67
  539.28 1046.98  541.35 1042.66  565.04 1046.23  583.15 1042.65  607.26 1046.29
  627.31  1042.7   634.6 1048.34   645.2 1054.42  702.62 1054.53   719.4 1056.57
  736.71 1062.08  752.32  1065.2   771.4 1071.04  795.48  1075.6     812 1080.13
  858.45 1087.75  905.79 1092.92  953.07 1096.25  970.37 1096.79    1085  1096.6
#Mann= 3 , 0 , 0
       0     .11       0  539.28    .048       0   634.6     .11       0
Bank Sta=539.28,634.6
Exp/Cntr=0.3,0.1

Type RM Length L Ch R = 1 ,66042.48,589.15,589.15,622.5
XS GIS Cut Line= 3
  1344808.211315   797868.686068  1344272.016243   797974.636917
  1343738.858866   798091.727477
#Sta/Elev= 30
       0 1164.65   74.32 1161.15   89.84 1157.98  120.03  1154.7  130.15 1152.24
  180.99 1144.68  195.62 1141.36  264.91 1123.93  289.11 1118.85   336.1 1099.24
  351.08 1097.32  364.68 1089.61  392.63 1083.17  417.89 1064.41  432.98 1063.64
  455.67 1056.65   492.6 1048.82  519.98 1042.45  543.73 1041.95  572.27 1043.23
  589.64 1051.11  606.94 1050.05  620.75 1054.68  641.41 1058.81  815.11 1081.86
  831.93 1085.68  884.16 1090.63  920.49 1095.68 1006.76 1103.76 1092.43 1109.04
#Mann= 3 , 0 , 0
       0     .11       0   492.6    .048       0  589.64     .11       0
Bank Sta=492.6,589.64
Exp/Cntr=0.3,0.1

Type RM Length L Ch R = 1 ,65453.34,450.84,450.84,386.72
XS GIS Cut Line= 2
  1344586.495347   797237.963508  1343507.791602   797645.370996
#Sta/Elev= 30
       0  1073.4    5.42 1073.75   13.68 1072.76   54.37 1071.04  110.35  1071.1
  148.25 1068.61  163.35 1068.37  175.49 1069.44  217.03 1070.67  296.52 1071.68
  354.21 1063.69  371.25 1063.01  386.74 1058.09  397.61  1053.4  423.14 1045.54
  429.58 1042.06  475.76 1040.58   484.2  1041.1  499.22 1049.46  525.33 1049.95
  578.25 1054.99  610.33 1056.45  682.92 1061.63  797.42 1071.66  836.81 1076.29
  963.64 1086.72 1019.89 1088.67  1097.1 1095.94 1138.26 1099.04 1153.08 1099.26
#Mann= 3 , 0 , 0
       0     .11       0  423.14    .048       0  499.22     .11       0
Bank Sta=423.14,499.22
Exp/Cntr=0.5,0.3