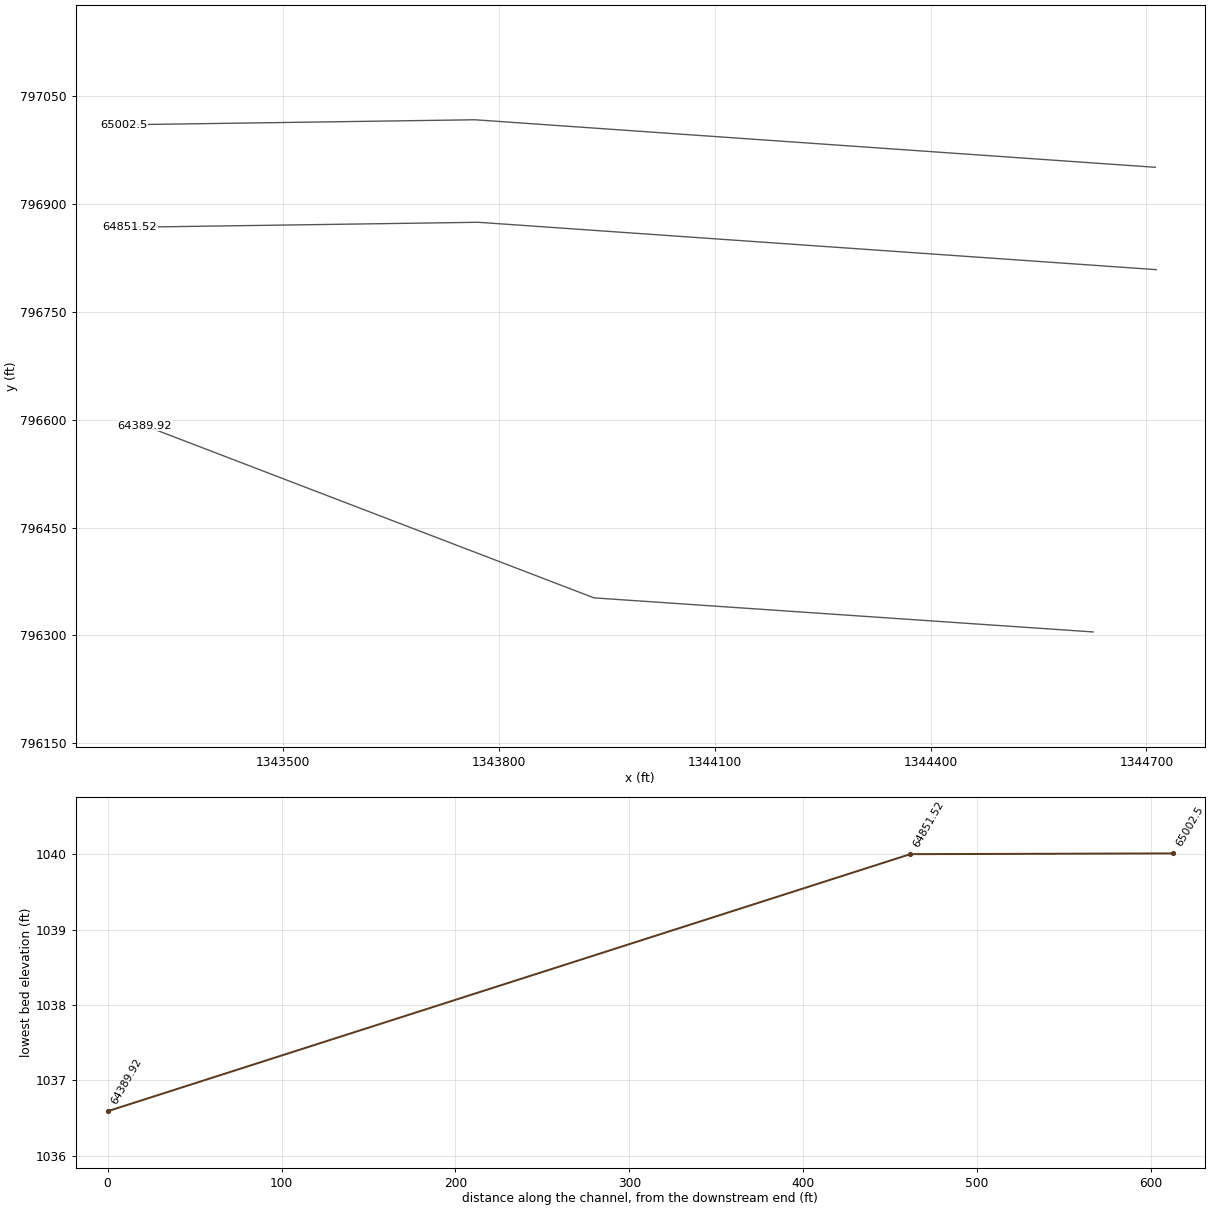
HEC-RAS study LLRiver.prj: LLRiver

--- LLRiver.g01 (geometry) --- (continued)

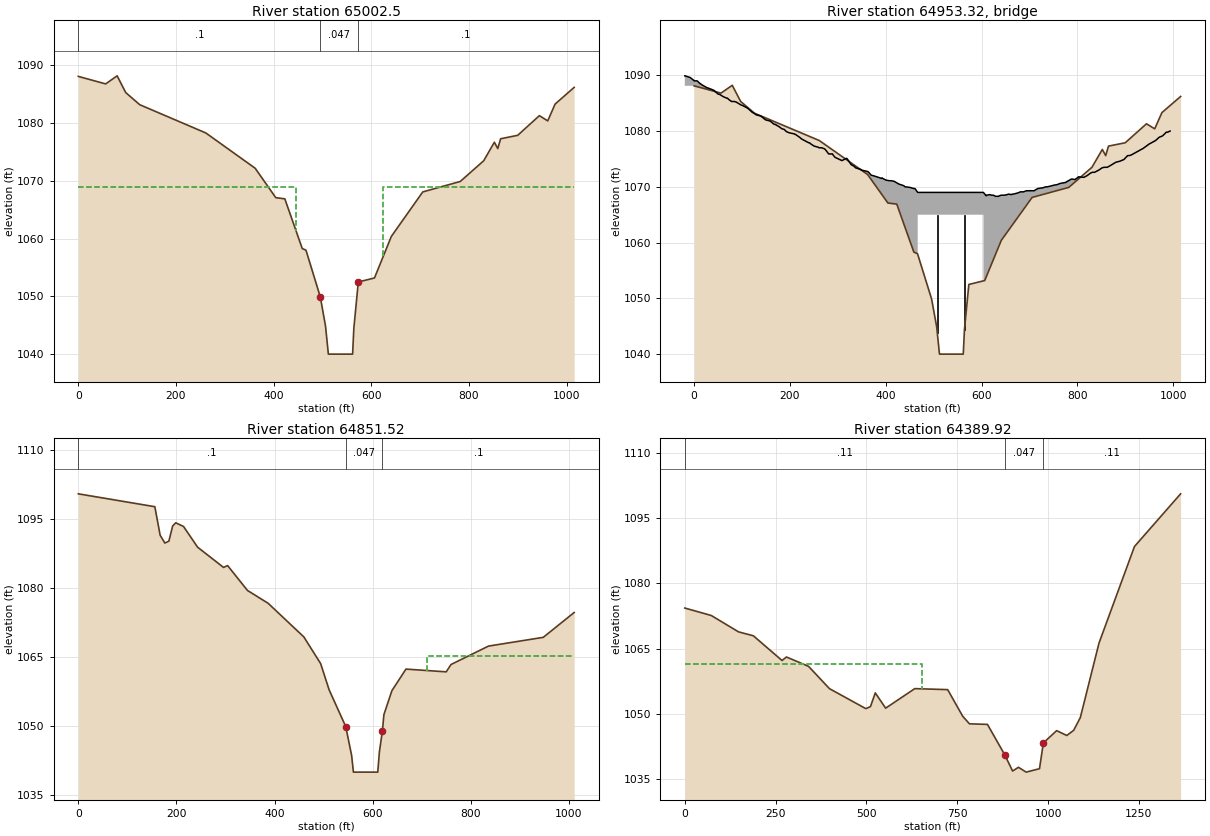
Type RM Length L Ch R = 1 ,65002.5 ,150.98,150.98,153.85
BEGIN DESCRIPTION:
Upstream xs of Bridge 37003-0035
END DESCRIPTION:
XS GIS Cut Line= 3
  1344712.546547   796950.898804  1343766.424819   797016.988148
  1343278.632306     797010.0197
#Sta/Elev= 30
       0  1088.1  55.932  1086.8  79.479  1088.2  97.086  1085.3 125.794  1083.2
 261.276  1078.3  362.18  1072.2 404.465  1067.1 422.991  1066.9 458.629  1058.3
 466.337    1058 495.682  1049.9 506.288  1044.9  512.18 1040.01   561.8 1040.01
 564.271  1044.4 573.464  1052.5 606.627  1053.2 641.204  1060.4 705.551  1068.1
 782.201  1069.9 830.426  1073.5 852.134  1076.7 859.205  1075.6 865.004  1077.3
 900.006  1077.9 944.341  1081.3 961.524  1080.4 976.514  1083.31015.617  1086.2
#Mann= 3 , 0 , 0
       0      .1       0 495.682    .047       0 573.464      .1       0
#XS Ineff= 2 , 0
       0 446.043  1068.9 624.517       0  1068.9
Permanent Ineff=
       F       F
Bank Sta=495.682,573.464
Skew Angle= 45
Exp/Cntr=0.5,0.3

Type RM Length L Ch R = 3 ,64953.32,,,
BEGIN DESCRIPTION:
Bridge : 37003-0035 - US-64
END DESCRIPTION:
Bridge Culvert--1,0,-1,-1, 0
Deck Dist Width WeirC Skew NumUp NumDn MinLoCord MaxHiCord MaxSubmerge Is_Ogee
29.2,40,2.6,45, 182, 181, , , 0.95, 0, 0,0,,
 -19.587 -18.385 -16.263 -15.415  -8.344  -1.061   -.566   -.071   6.223  12.304
  13.081   15.91  23.829  26.022  32.668  41.224  46.386  50.346  52.679  60.033
  67.529  69.509  71.559  77.923  83.863  87.681  97.227  100.48 111.581 112.713
  114.41 120.632 124.734 129.683 138.946 140.361 141.563   149.2 154.149 158.321
 164.332 167.231 169.211 178.615 183.211 187.878 192.545 195.303 198.061 202.798
  208.95 210.364 211.496 221.395  223.87 230.305 239.073  240.77 243.315 250.457
 259.084 260.569 266.579 272.236  273.65 280.792 288.429 288.782 289.277 293.874
 303.349 308.581  317.42  318.41 319.683 327.532 333.613  337.29  348.25 349.099
 359.917 363.382 369.463 377.666 391.666 392.656 393.717 400.717 407.152 408.708
 410.475 417.334 423.203 427.375  437.77 439.962 441.305 450.356 458.205 460.892
  466.69  466.69 603.869 603.869 609.667 610.799 616.809 621.547 624.517 629.254
 632.366 634.416 640.851 647.003 653.367 656.549 662.135 664.327 666.377 675.641
 681.085 686.742 687.449 693.884 698.339  708.38 710.077  711.42 717.643 725.209
 727.118 733.765 737.159 742.321 750.665 751.301 757.806 763.675 776.191 777.323
 787.788 789.131 794.788 799.738 802.566 812.041 813.526 820.244 826.537 828.163
 831.133 835.659 838.134  844.78 851.569  855.67 862.317 868.681 880.207 889.116
 897.248 902.975 905.026 908.562 912.238  914.36 921.148 927.017 931.613 937.624
 944.129 950.352 954.806 962.867 963.292  971.07 977.222 978.777 981.111 985.707
 988.606 993.626
  1089.9  1089.9  1089.8  1089.8  1089.6  1089.1  1089.1    1089    1089  1088.5
  1088.5  1088.3  1087.9  1087.8  1087.6  1087.3  1086.9  1086.6  1086.6  1086.2
  1085.9  1085.9  1085.7  1085.3  1085.3  1085.2  1084.7  1084.6  1084.1    1084
  1083.9  1083.4  1083.2  1082.9  1082.7  1082.6  1082.5    1082  1081.9  1081.8
  1081.4  1081.2  1081.2  1080.7  1080.4  1080.3  1079.9  1079.8  1079.7  1079.6
  1079.5  1079.4  1079.4  1078.8  1078.6  1078.3  1077.9  1077.9  1077.7  1077.3
  1077.1    1077    1077  1076.8  1076.7  1075.9  1075.9  1075.9  1075.8  1075.3
  1074.9  1074.7  1075.1  1075.1    1075    1074  1073.7  1073.4  1073.1    1073
  1072.8  1072.7  1072.1  1071.9  1071.5  1071.6  1071.5  1071.2  1071.1  1071.1
  1071.1    1071  1070.7  1070.5  1070.2    1070    1070  1069.9  1069.7  1069.7
    1069    1069    1069    1069  1068.4  1068.5  1068.6  1068.5  1068.5  1068.3
  1068.3  1068.3  1068.5  1068.5  1068.6  1068.7  1068.6  1068.7  1068.7  1068.9
  1069.1  1069.1  1069.1  1069.3  1069.3  1069.3  1069.3  1069.4  1069.7  1069.8
  1069.8    1070    1070  1070.1  1070.3  1070.3  1070.4  1070.6  1070.8  1070.9
  1071.4  1071.4  1071.3  1071.6  1071.8  1071.7  1071.7    1072  1072.4  1072.5
  1072.6  1072.6  1072.7    1073  1073.4  1073.5  1073.5  1073.8  1074.4  1074.6
  1074.9  1075.4  1075.6  1075.6  1075.7  1075.8  1076.1  1076.4  1076.6  1076.9
  1077.3  1077.7  1077.9  1078.3  1078.3  1078.9  1079.1  1079.2  1079.4  1079.8
  1079.8    1080
                                                                                
                                                                                
                                                                                
                                                                                
                                                                                
                                                                                
                                                                                
                                                                                
                                                                                
                                                                                
            1065    1065
                                                                                
                                                                                
                                                                                
                                                                                
                                                                                
                                                                                
                                                                                
                
  24.961  26.092  28.214  29.133  36.133  43.416  43.911  44.477   50.77  56.781
  57.629  60.387  68.307  70.499  77.216  85.701  90.863  94.823  97.227 104.581
 112.076 114.056 116.107   122.4 128.411 132.158 141.775 145.028 156.058  157.19
 158.887  165.18 169.281  174.16 183.494 184.908  186.04 193.747 198.626 202.798
 208.879 211.778 213.758 223.092 227.759 232.355 237.022  239.78 242.538 247.346
 253.427 254.841 255.973 265.872 268.347 274.782 283.621 285.247 287.792 294.934
 303.561 305.117 311.127 316.713 318.127 325.269 332.906  333.33 333.754 338.351
 347.826 353.129 361.968 362.958  364.16 372.009 378.161 381.767 392.727 393.576
 404.465  407.93  413.94 422.143 436.214 437.204 438.265 445.194 451.629 453.185
 454.953 461.811 467.751 471.852 482.318  484.51 485.853 494.904 502.682 516.188
 516.188 653.367 653.367 654.215 655.276 661.357 666.024 669.064 673.731 676.913
 678.893 685.399  691.55 697.844 701.096 706.612 708.804 710.854 720.188 725.633
 731.219 731.997 738.361 742.886 752.857 754.624 755.897  762.19 769.686 771.595
 778.312 781.636 786.868 795.142 795.849 802.354 808.223 820.739  821.87 832.265
 833.679 839.336 844.215 847.043 856.589 858.003 864.721 871.085  872.64 875.681
 880.207 882.611 889.328 896.116 900.218 906.794 913.228 924.683 933.664 941.725
 947.523 949.574 953.039 956.715 958.837 965.696 971.494 976.161 982.171 988.677
 994.899 999.3541007.4151007.7691015.6171021.6991023.2541025.6581030.1841033.154
1038.174
  1089.9  1089.9  1089.8  1089.8  1089.6  1089.1  1089.1    1089    1089  1088.5
  1088.5  1088.3  1087.9  1087.8  1087.6  1087.3  1086.9  1086.6  1086.6  1086.2
  1085.9  1085.9  1085.7  1085.3  1085.3  1085.2  1084.7  1084.6  1084.1    1084
  1083.9  1083.4  1083.2  1082.9  1082.7  1082.6  1082.5    1082  1081.9  1081.8
  1081.4  1081.2  1081.2  1080.7  1080.4  1080.3  1079.9  1079.8  1079.7  1079.6
  1079.5  1079.4  1079.4  1078.8  1078.6  1078.3  1077.9  1077.9  1077.7  1077.3
  1077.1    1077    1077  1076.8  1076.7  1075.9  1075.9  1075.9  1075.8  1075.3
  1074.9  1074.7  1075.1  1075.1    1075    1074  1073.7  1073.4  1073.1    1073
  1072.8  1072.7  1072.1  1071.9  1071.5  1071.6  1071.5  1071.2  1071.1  1071.1
  1071.1    1071  1070.7  1070.5  1070.2    1070    1070  1069.9  1069.7    1069
    1069    1069    1069  1068.4  1068.5  1068.6  1068.5  1068.5  1068.3  1068.3
  1068.3  1068.5  1068.5  1068.6  1068.7  1068.6  1068.7  1068.7  1068.9  1069.1
  1069.1  1069.1  1069.3  1069.3  1069.3  1069.3  1069.4  1069.7  1069.8  1069.8
    1070    1070  1070.1  1070.3  1070.3  1070.4  1070.6  1070.8  1070.9  1071.4
  1071.4  1071.3  1071.6  1071.8  1071.7  1071.7    1072  1072.4  1072.5  1072.6
  1072.6  1072.7    1073  1073.4  1073.5  1073.5  1073.8  1074.4  1074.6  1074.9
  1075.4  1075.6  1075.6  1075.7  1075.8  1076.1  1076.4  1076.6  1076.9  1077.3
  1077.7  1077.9  1078.3  1078.3  1078.9  1079.1  1079.2  1079.4  1079.8  1079.8
    1080
                                                                                
                                                                                
                                                                                
                                                                                
                                                                                
                                                                                
                                                                                
                                                                                
                                                                                
                                                                                
    1065    1065
                                                                                
                                                                                
                                                                                
                                                                                
                                                                                
                                                                                
                                                                                
        
Pier Skew, UpSta & Num, DnSta & Num=  ,507.724, 2 ,557.2, 2 , 0 , 0 , 0 ,,
       2       2
  1042.6  1065.5
       2       2
  1042.6  1065.5
Pier Skew, UpSta & Num, DnSta & Num=  ,564.292, 2 ,613.769, 2 , 0 , 0 , 0 ,,
       2       2
  1043.4  1065.5
       2       2
  1043.4  1065.5
BR Coef=-1 , 1 , 0 ,, 0 ,,,0.8,0,1.2,0,
WSPro=,,,, 1 ,,,, 0 ,,,, 0 ,,,,-1 ,-1 ,-1 , 0 , 0 , 0 , 0 , 0
BC Design=,, 0 ,, 0 ,,,,,,

Type RM Length L Ch R = 1 ,64851.52,461.59,461.59,523.84
BEGIN DESCRIPTION:
Down stream xs of Bridge 37003-0035
END DESCRIPTION:
XS GIS Cut Line= 3
  1344713.916403   796808.593267  1343771.149299   796874.448244
  1343286.719474   796867.527924
#Sta/Elev= 30
       0  1100.5 155.988  1097.7 166.806  1091.5 176.352  1089.8 184.555  1090.2
 192.262  1093.5 198.556  1094.2 214.465  1093.4 243.174  1088.9 296.066  1084.5
 304.339  1084.9 344.785  1079.5     387  1076.7  459.69  1069.4 493.985  1063.6
 511.238  1057.9 545.179  1049.9   557.2  1043.6  560.79    1040  610.44    1040
 613.769  1044.4  619.93 1048.99 622.961  1052.5 639.225  1057.7 667.933  1062.4
 749.957  1061.8 759.857  1063.4 836.224  1067.4 947.806  1069.31010.809  1074.7
#Mann= 3 , 0 , 0
       0      .1       0 545.179    .047       0  619.93      .1       0
#XS Ineff= 2 , 0
       0 458.347  1065.2 711.208       0  1065.2
Permanent Ineff=
       F       F
Bank Sta=545.179,619.93
Skew Angle= 45
Exp/Cntr=0.5,0.3

Type RM Length L Ch R = 1 ,64389.92,691.7,691.7,640.38
XS GIS Cut Line= 3
  1344625.827827   796304.856307  1343931.981427   796352.233715
   1343306.98149   796591.817075
#Sta/Elev= 30
       0  1074.3    72.8 1072.59  147.82 1068.83  188.79 1067.92  267.72 1062.24
   279.7 1063.05  340.71  1060.9  398.11 1055.78  498.31 1051.18  511.11 1051.65
  524.27  1054.8  552.89 1051.29  633.06 1055.78  723.61 1055.55  764.99 1049.43
  783.58 1047.69  833.11 1047.56  880.61 1040.58  902.32 1036.84  918.47  1037.7
   939.8 1036.59  976.36 1037.38  986.98  1043.3 1023.51 1046.12 1051.66 1045.01
 1070.41  1046.2 1088.69 1049.12 1140.25 1066.27 1237.75 1088.44 1364.81 1100.55
#Mann= 3 , 0 , 0
       0     .11       0  880.61    .047       0  986.98     .11       0
#XS Ineff= 2 , 0
          653.54 1061.41
Permanent Ineff=
       F       F
Bank Sta=880.61,986.98
Exp/Cntr=0.3,0.1