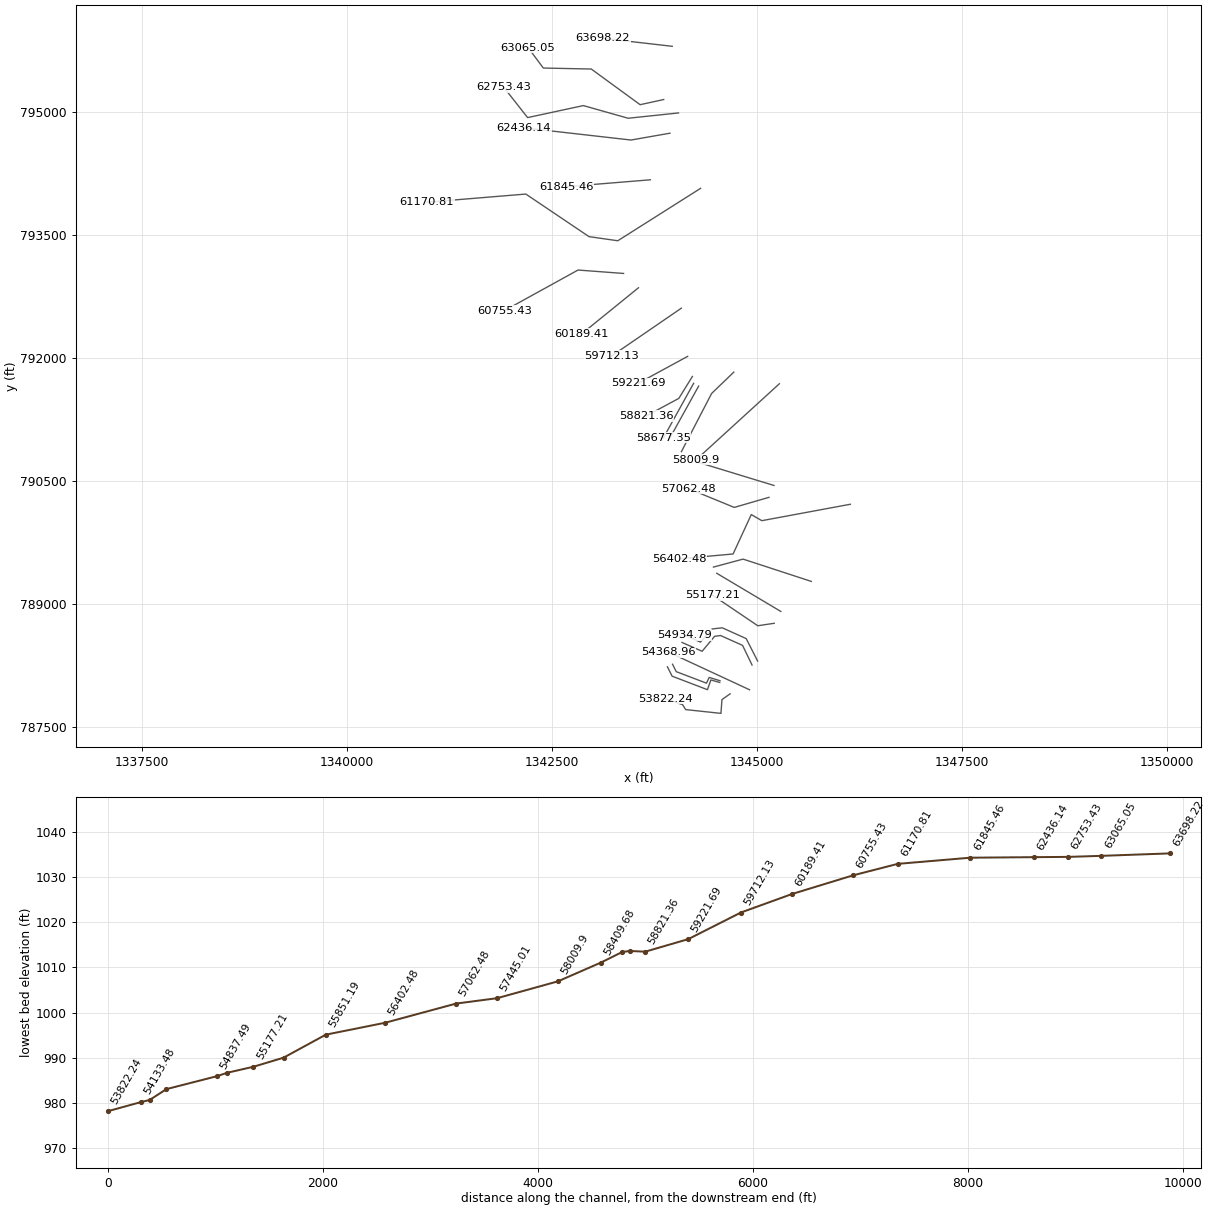
HEC-RAS study LLRiver.prj: LLRiver

--- LLRiver.g01 (geometry) --- (continued)

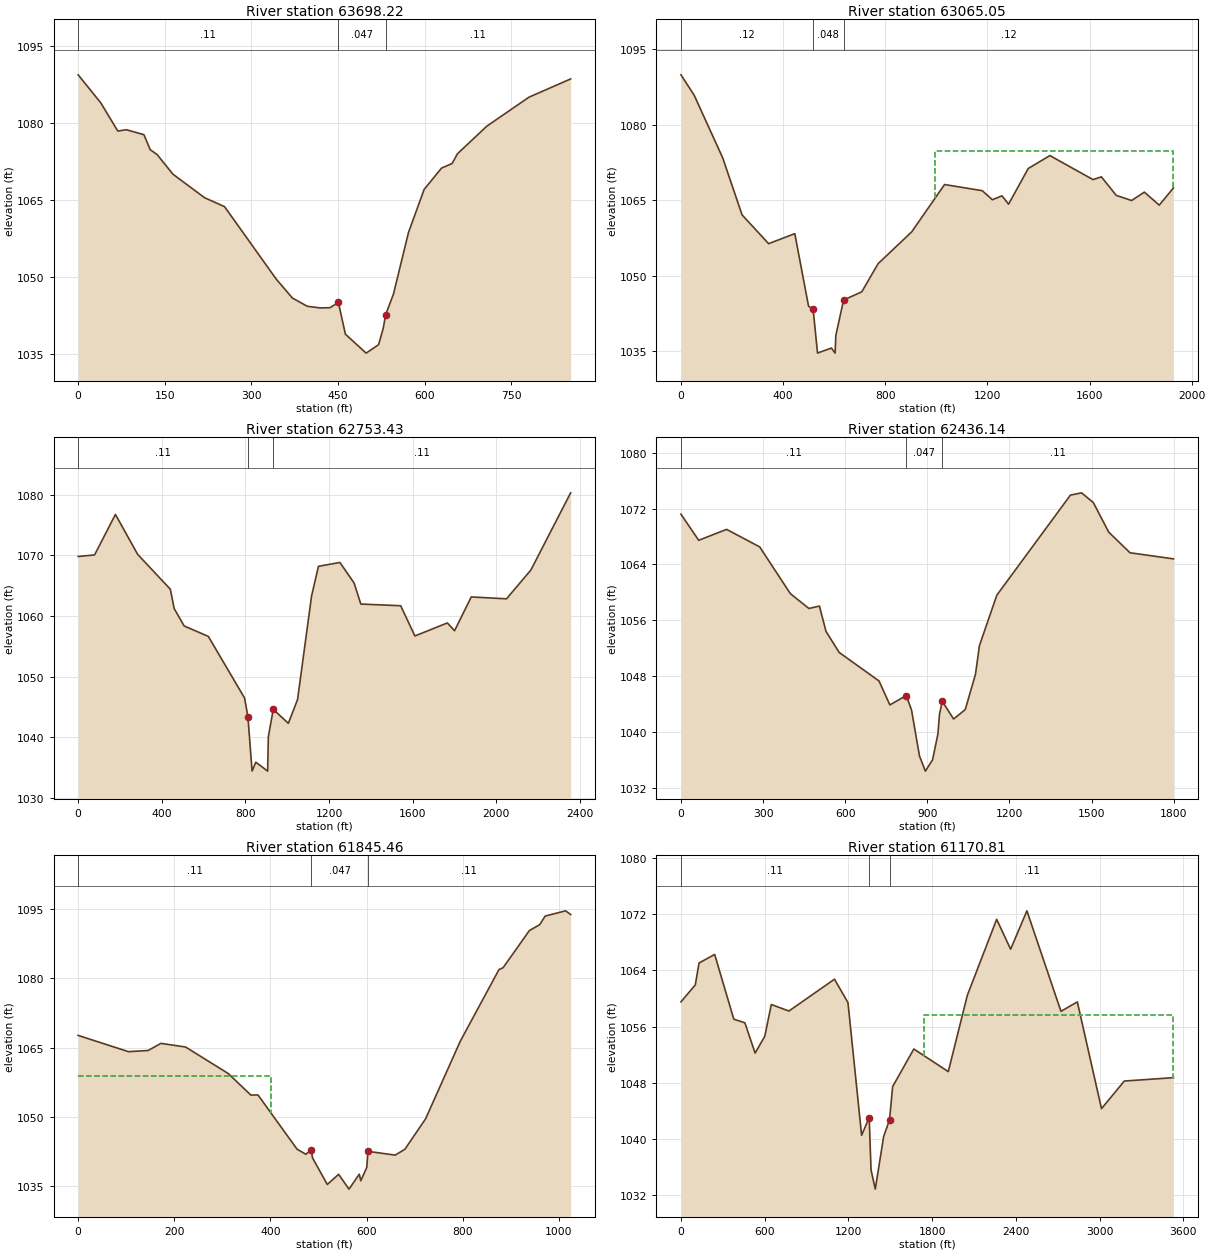
Type RM Length L Ch R = 1 ,63698.22,633.17,633.17,736.74
XS GIS Cut Line= 2
  1343966.703731   795799.884915  1343119.481458   795897.107059
#Sta/Elev= 30
       0 1089.35   39.08 1083.91   68.66  1078.4   83.32 1078.67  113.91  1077.7
  124.73 1074.78  136.72 1073.83  164.02 1070.02  218.91 1065.43  253.48 1063.69
  343.12 1049.57  371.03  1045.9  396.68  1044.3  418.93 1043.98  436.24 1044.02
  450.54 1045.05  462.77 1038.87  498.63 1035.18  520.21 1036.82   528.2 1039.99
  532.38 1042.63  546.02 1046.69  572.02 1058.67  599.08 1067.04  629.18 1071.19
  647.61  1072.1  656.76 1073.98  707.81 1079.37  780.82 1085.01  852.78 1088.55
#Mann= 3 , 0 , 0
       0     .11       0  450.54    .047       0  532.38     .11       0
Bank Sta=450.54,532.38
Exp/Cntr=0.3,0.1

Type RM Length L Ch R = 1 ,63065.05,311.62,311.62,239.08
XS GIS Cut Line= 5
  1343862.537075   795150.579314  1343574.796274   795087.667314
   1342978.95717   795522.638834  1342394.035825   795534.701938
  1342208.105201   795784.126323
#Sta/Elev= 30
       0 1089.89   51.66 1085.86  163.66 1073.39   239.3 1062.09  343.25 1056.37
  445.81 1058.36  499.76 1043.94  517.61 1043.34  534.79 1034.65  589.14 1035.65
  603.63 1034.64  606.48 1038.14  636.82 1045.18  708.02 1046.81  772.07  1052.4
  903.61 1058.72 1032.25 1068.11 1179.87 1066.89 1219.39 1065.09 1257.03 1065.87
  1282.9 1064.21    1360  1071.3 1444.72 1073.86 1613.47 1069.09 1646.32 1069.64
 1704.42 1065.96 1764.65 1064.94 1814.55  1066.6 1872.95 1064.02  1928.4 1067.43
#Mann= 3 , 0 , 0
       0     .12       0  517.61    .048       0  636.82     .12       0
#XS Ineff= 2 , 0
                          994.56         1074.73
Permanent Ineff=
       F       F
Bank Sta=517.61,636.82
Exp/Cntr=0.3,0.1

Type RM Length L Ch R = 1 ,62753.43,317.29,317.29,285.06
XS GIS Cut Line= 5
  1344043.049075   794987.012722  1343428.337266   794922.306162
   1342882.37605    795076.73317  1342202.324721   794930.312178
  1341909.005297    795303.43013
#Sta/Elev= 30
       0 1069.79   78.39 1070.04   178.3 1076.72  284.55 1070.14  440.88 1064.39
  459.25 1061.21  506.87 1058.34  622.75 1056.61  796.12 1046.45  812.15 1043.32
  831.88 1034.42  849.93 1035.88   906.3 1034.41  909.75 1040.07  933.21 1044.59
 1005.37 1042.29 1049.42 1046.21 1116.51 1063.28 1149.36 1068.17 1252.03  1068.8
 1320.02 1065.41 1351.99 1061.95  1542.8 1061.67 1610.74 1056.69 1765.94 1058.83
  1800.5 1057.55 1880.34 1063.12 2048.92 1062.81 2165.78 1067.57 2355.73 1080.28
#Mann= 3 , 0 , 0
       0     .11       0  812.15    .047       0  933.21     .11       0
Bank Sta=812.15,933.21
Exp/Cntr=0.3,0.1

Type RM Length L Ch R = 1 ,62436.14,590.68,590.68,551.64
XS GIS Cut Line= 3
  1343938.803315   794739.903986   1343463.10885   794656.570609
  1342155.249393    794805.31109
#Sta/Elev= 30
       0 1071.21   64.95 1067.46  166.81 1069.03  287.82 1066.51  399.65 1059.81
  467.61 1057.68  505.95 1058.03  529.99 1054.39  577.94 1051.38  723.75 1047.28
  763.26 1043.85   823.1 1045.19  842.28 1043.15  871.51 1036.52   892.9 1034.35
  919.35 1035.98  938.87 1039.69  944.26 1042.41  954.54 1044.37  996.13 1041.83
 1038.73 1043.18 1076.04 1048.24 1090.58 1052.36 1154.05 1059.59 1422.92 1073.94
 1463.52 1074.27 1506.62 1072.87  1562.9 1068.63  1640.8 1065.67 1799.23  1064.8
#Mann= 3 , 0 , 0
       0     .11       0   823.1    .047       0  954.54     .11       0
Bank Sta=823.1,954.54
Exp/Cntr=0.3,0.1

Type RM Length L Ch R = 1 ,61845.46,674.64,674.64,719.42
XS GIS Cut Line= 2
  1343699.342578   794171.412721  1342678.509298   794088.079345
#Sta/Elev= 30
       0 1067.63  104.62  1064.1  145.43 1064.35   172.2  1065.9  223.41 1065.11
  312.26 1059.34  359.09 1054.67  374.04 1054.69  455.11 1042.93  473.37 1041.81
  484.85 1042.73  487.39 1041.03  518.12 1035.24  541.77 1037.45  563.23 1034.23
  584.69 1037.48  587.76 1036.04  600.22 1038.95  602.66 1042.44  659.31 1041.62
  679.56  1042.9  722.53  1049.5  794.83 1066.39  875.14 1081.93  883.65 1082.33
  938.53 1090.42  959.79 1091.68  971.26 1093.56 1013.84  1094.7 1024.23  1093.9
#Mann= 3 , 0 , 0
       0     .11       0  484.85    .047       0  602.66     .11       0
#XS Ineff= 2 , 0
          400.87 1058.82
Permanent Ineff=
       F       F
Bank Sta=484.85,602.66
Exp/Cntr=0.3,0.1

Type RM Length L Ch R = 1 ,61170.81,415.38,415.38,401.56
XS GIS Cut Line= 5
  1344312.407539   794067.242225  1343302.134386   793427.824368
  1342951.350642   793478.237168  1342180.509681   793997.538545
  1340973.427952   793897.838577
#Sta/Elev= 30
       0 1059.52  102.85 1061.93  129.74 1065.05   241.8 1066.26  378.83 1057.05
  458.24 1056.54  531.75 1052.22  600.88 1054.63  647.65 1059.14  773.75 1058.21
 1100.33 1062.74 1197.06 1059.41 1294.86 1040.53 1349.09 1043.05 1362.35 1035.61
 1392.82 1032.87 1452.62 1040.34 1495.08 1042.74 1517.22 1047.46  1669.1 1052.81
 1916.12 1049.59 2053.08 1060.48 2262.77 1071.26 2362.81 1067.01 2479.45 1072.47
 2723.59 1058.17 2840.92 1059.51 3014.04 1044.32 3177.67 1048.25 3529.57 1048.73
#Mann= 3 , 0 , 0
       0     .11       0 1349.09    .047       0 1495.08     .11       0
#XS Ineff= 2 , 0
                         1745.38          1057.7
Permanent Ineff=
       F       F
Bank Sta=1349.09,1495.08
Exp/Cntr=0.3,0.1

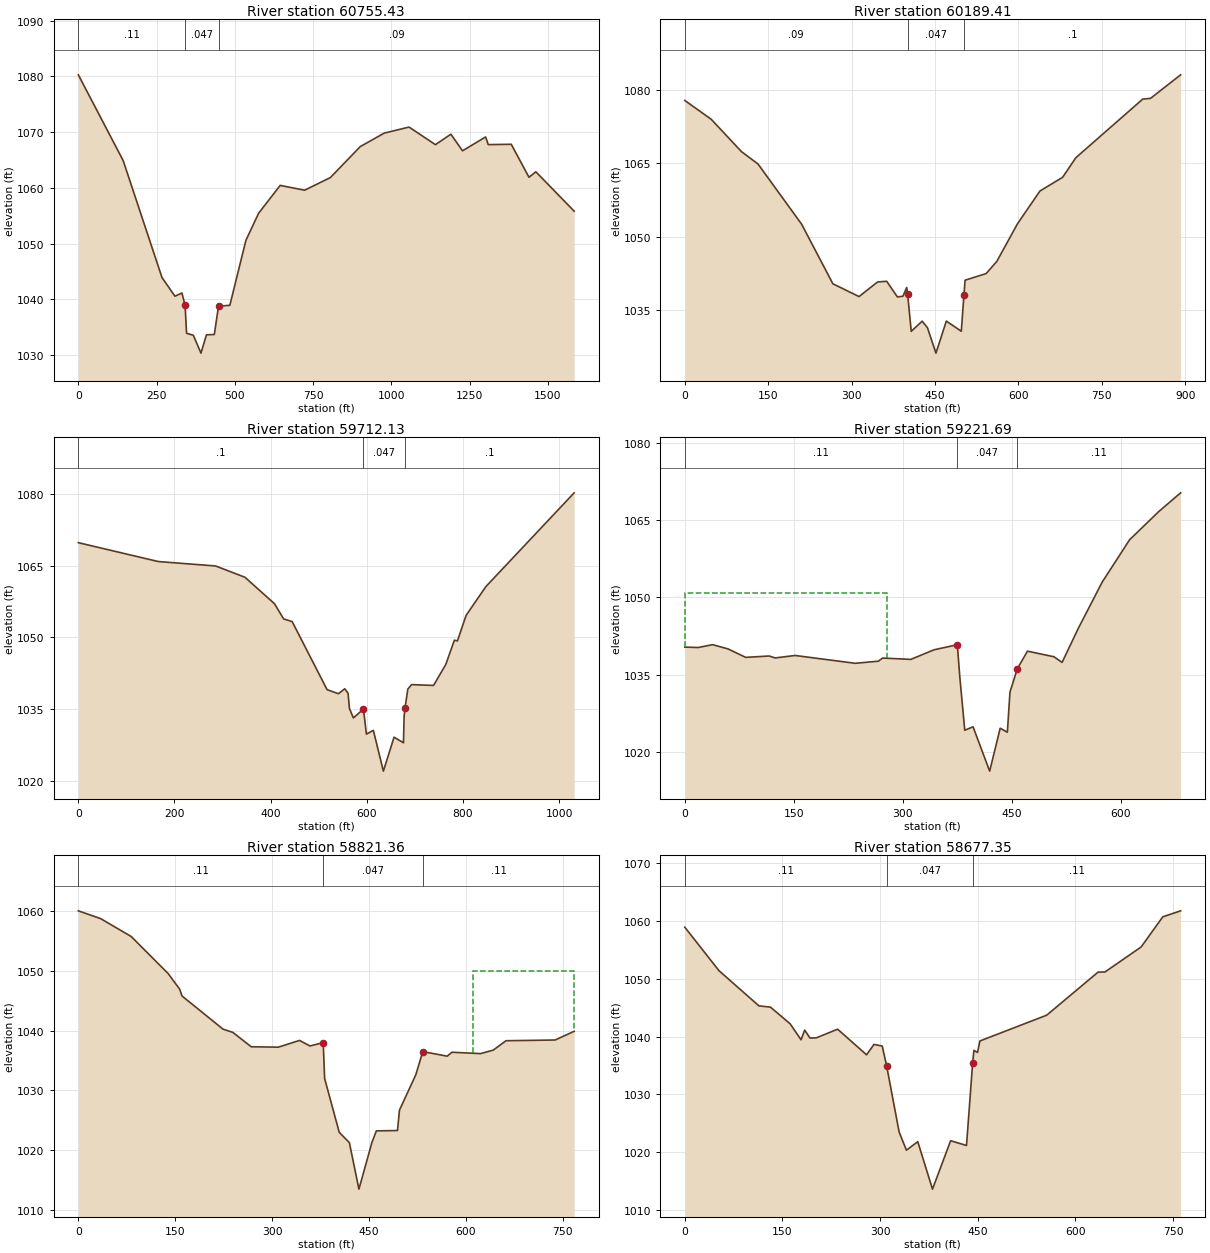
Type RM Length L Ch R = 1 ,60755.43,566.02,566.02,413.41
XS GIS Cut Line= 3
  1343372.953714   793029.051504   1342817.39813   793070.718192
  1341918.489201   792574.897648
#Sta/Elev= 30
       0  1080.3  143.25  1064.9  267.22  1043.9  308.59 1040.55  330.93 1041.12
  340.95 1038.93  345.69  1033.9  367.36 1033.53  391.73 1030.33  409.14 1033.61
   434.4 1033.68  447.71 1038.75  483.97 1038.92   535.2 1050.57  575.78 1055.44
  644.77 1060.45  722.79 1059.58  805.05 1061.85   900.6 1067.42  976.98 1069.83
 1056.26 1070.92 1140.64 1067.76 1189.96 1069.64 1227.12 1066.66 1300.95 1069.15
 1309.28 1067.77 1382.81 1067.83 1439.36 1061.91  1461.4 1062.89  1583.7 1055.82
#Mann= 3 , 0 , 0
       0     .11       0  340.95    .047       0  447.71     .09       0
Bank Sta=340.95,447.71
Exp/Cntr=0.3,0.1

Type RM Length L Ch R = 1 ,60189.41,477.28,477.28,493.45
XS GIS Cut Line= 2
   1343554.94501   792854.549488  1342862.537074   792292.940399
#Sta/Elev= 30
       0 1077.78   47.52 1073.94  101.69 1067.36  131.69 1064.81  210.08 1052.53
  266.28 1040.37  313.26 1037.76  346.61 1040.74  363.06 1040.88  382.26 1037.69
  392.24 1037.83  399.02 1039.63  400.71 1038.21  407.15 1030.67  426.81 1032.74
  436.34  1031.4  451.58 1026.22  470.28 1032.76  497.15 1030.69  501.85 1037.98
  503.99  1041.1  541.91 1042.46  560.91 1044.92   598.4 1052.65  638.67 1059.31
  679.34  1062.1  703.17  1066.1  823.44 1078.06  837.35  1078.2  891.53 1083.01
#Mann= 3 , 0 , 0
       0     .09       0  400.71    .047       0  501.85      .1       0
Bank Sta=400.71,501.85
Exp/Cntr=0.3,0.1

Type RM Length L Ch R = 1 ,59712.13,490.45,490.45,511.24
XS GIS Cut Line= 2
  1344077.814771   792605.440368   1343227.12037   792022.107119
#Sta/Elev= 30
       0 1069.78  166.38 1065.84  285.52 1064.92  346.68 1062.56  408.07 1057.04
  427.16 1053.87  444.86 1053.31   517.5 1039.11  541.08 1038.26  554.24 1039.29
  561.15 1038.36  563.98 1035.19  572.16 1033.22  593.21 1035.05  599.27 1029.83
  613.75 1030.62   634.6 1022.11   656.8 1029.19  676.41 1028.03  677.69  1033.5
   679.7 1035.37  685.53 1039.24  693.34 1040.16  738.96 1039.99  764.42 1044.36
  782.33 1049.43  788.69 1049.28  806.71 1054.61  847.78 1060.61 1031.48 1080.18
#Mann= 3 , 0 , 0
       0      .1       0  593.21    .047       0   679.7      .1       0
Bank Sta=593.21,679.7
Exp/Cntr=0.3,0.1

Type RM Length L Ch R = 1 ,59221.69,400.33,400.33,350.99
XS GIS Cut Line= 2
  1344154.664819   792017.631215  1343555.055474   791691.459311
#Sta/Elev= 30
       0 1040.34   18.39 1040.26   38.26 1040.81   59.46 1039.99    83.9 1038.34
  116.17 1038.61  124.27 1038.23  151.91 1038.71  234.62 1037.19  266.46  1037.6
  272.39 1038.21  311.17 1037.95     343 1039.81  375.19  1040.8  378.56 1034.61
  385.42 1024.17  396.84 1024.84   419.7 1016.22  434.17 1024.56  444.07 1023.79
  447.64 1031.58  457.71  1036.1  471.72 1039.55  508.25 1038.46  519.39 1037.36
   541.6 1043.95  574.59 1052.97  612.29  1061.2  652.12 1066.65  682.58 1070.34
#Mann= 3 , 0 , 0
       0     .11       0  375.19    .047       0  457.71     .11       0
#XS Ineff= 2 , 0
          278.02 1050.94
Permanent Ineff=
       F       F
Bank Sta=375.19,457.71
Exp/Cntr=0.3,0.1

Type RM Length L Ch R = 1 ,58821.36,144.01,144.01,75.26
XS GIS Cut Line= 3
  1344212.638067   791772.502767  1344046.622451   791504.924655
  1343648.184946   791290.080878
#Sta/Elev= 30
       0 1060.09   34.46 1058.79   81.91 1055.78   138.8 1049.61  156.83 1046.97
  160.61 1045.81  224.17 1040.25  239.13 1039.72  267.66 1037.31  309.62 1037.24
  342.41 1038.37  358.56 1037.44  379.13    1038  381.29 1031.99  403.92 1022.97
  419.59 1021.24  434.39 1013.45  454.41 1021.24  461.37 1023.21  494.12 1023.27
  497.14 1026.69  522.42 1032.61  533.25  1036.5  571.06 1035.73  578.38 1036.39
  622.47 1036.16  642.23 1036.74  662.14 1038.32  738.05 1038.44  767.57  1039.9
#Mann= 3 , 0 , 0
       0     .11       0  379.13    .047       0  533.25     .11       0
#XS Ineff= 2 , 0
                          610.62         1049.97
Permanent Ineff=
       F       F
Bank Sta=379.13,533.25
Exp/Cntr=0.5,0.3

Type RM Length L Ch R = 1 ,58677.35,70.02,70.02,71
XS GIS Cut Line= 2
  1344227.567987   791688.895087  1343858.427379    791022.87947
#Sta/Elev= 30
       0 1058.91   52.52 1051.39  113.78 1045.31  131.66 1045.08  161.87 1042.19
  178.55 1039.44   184.1 1041.11  192.29 1039.74  201.73 1039.76   234.7 1041.27
  279.14 1036.84  290.55 1038.64  303.21 1038.35  309.96 1034.94  329.15  1023.5
  340.37 1020.34  357.78 1021.82  380.41 1013.61  408.27 1021.98  432.64 1021.16
  442.07 1035.44  444.01  1037.6  449.57 1037.25  453.15 1039.23   555.8 1043.69
  634.71 1051.14  645.38 1051.17  700.92  1055.5  734.05  1060.7  761.47 1061.74
#Mann= 3 , 0 , 0
       0     .11       0  309.96    .047       0  442.07     .11       0
Bank Sta=309.96,442.07
Exp/Cntr=0.5,0.3

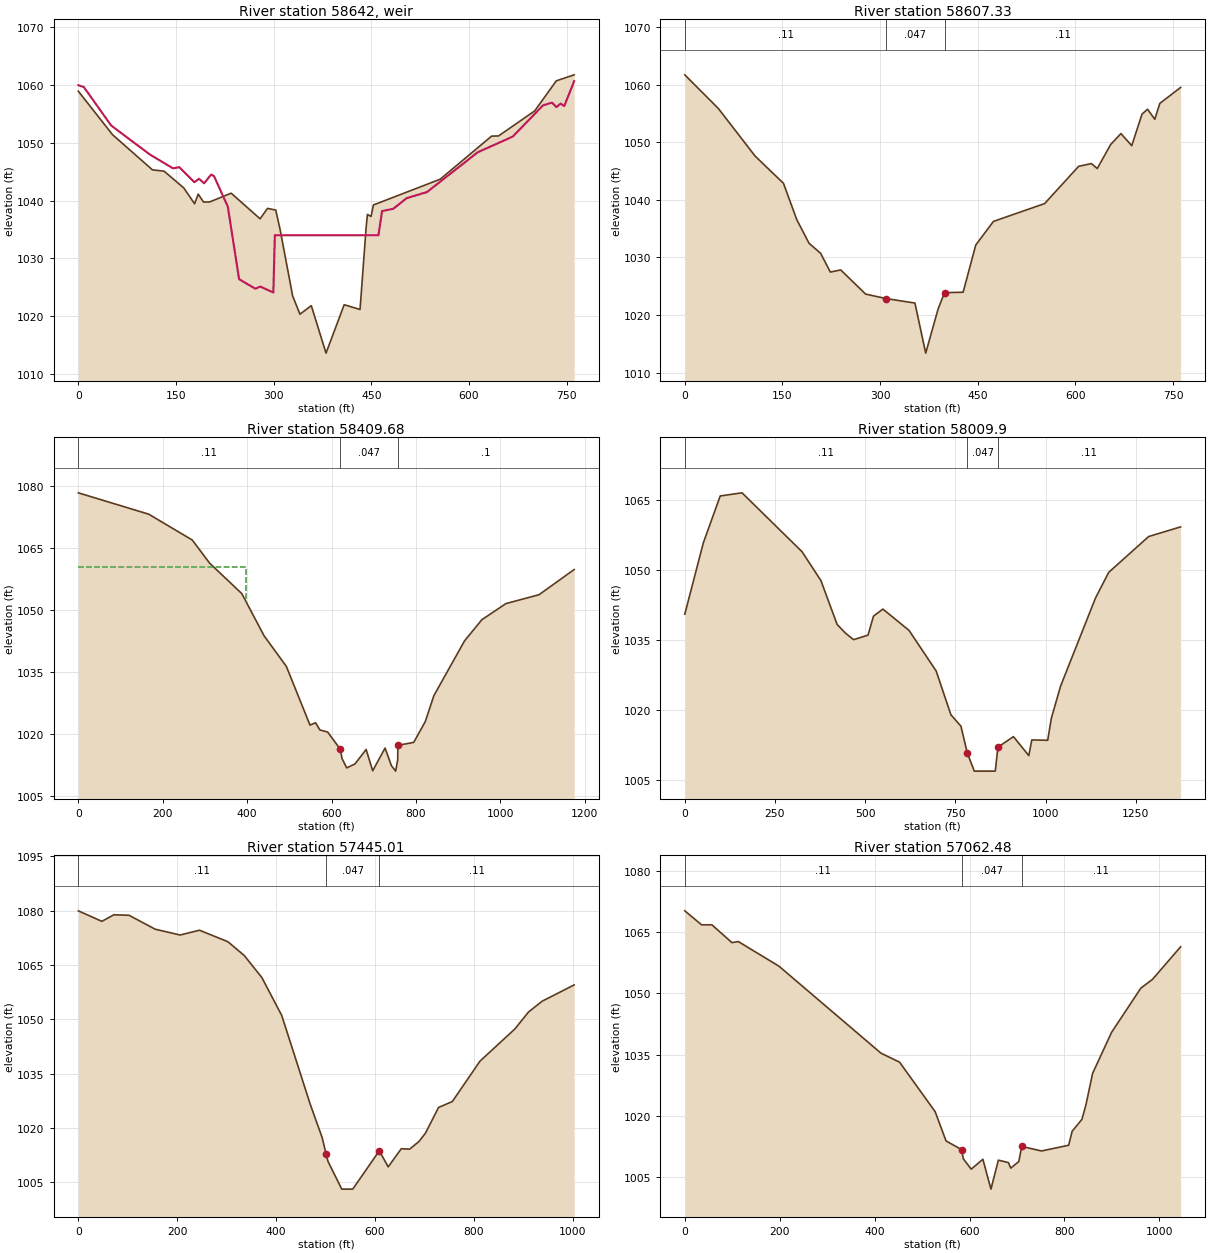
Type RM Length L Ch R = 5 ,58642   ,,,
BEGIN DESCRIPTION:
Dam 37003-0095
END DESCRIPTION:
IW Pilot Flow=0
#Inline Weir SE= 30
       0 1059.95    8.41 1059.63   50.52 1052.96  110.03 1047.95  145.31 1045.57
  155.05 1045.78  178.27 1043.17  185.37 1043.76  193.13 1042.98  204.16 1044.51
  208.57 1044.18  229.59 1038.94  246.87 1026.41  271.75 1024.75  279.62 1025.11
  299.51 1024.09  301.79    1034  460.88    1034  466.49 1038.18  483.49 1038.56
  504.21 1040.41  535.41 1041.46  613.27 1048.34  667.21 1051.06  713.64 1056.46
  727.61 1056.93  734.26 1056.15  740.57 1056.76  746.19 1056.34  761.47 1060.64
IW Dist,WD,Coef,Skew,MaxSub,Min_El,Is_Ogee,SpillHt,DesHd
60,10,2.6,0,0.95,, 0 ,,,0,0,

Type RM Length L Ch R = 1 ,58607.33,197.65,197.65,191.93
XS GIS Cut Line= 2
  1344288.792947   791654.961007  1343919.652339    790988.94539
#Sta/Elev= 30
       0 1061.73   51.63 1055.87  108.08  1047.6  151.54 1042.88  172.08 1036.54
  190.82 1032.46  208.64 1030.71  223.56 1027.45  239.47 1027.83  277.69 1023.63
  309.23 1022.85  353.43 1022.07  369.97 1013.37  389.12 1021.08  398.89 1023.88
  427.43 1023.95  446.84 1032.15  474.02 1036.26  552.69 1039.36  604.82 1045.83
  624.46 1046.31  633.44 1045.44  653.96 1049.61  669.81 1051.52   686.4 1049.42
  702.18  1054.9   710.7 1055.75  721.81 1054.01  729.49 1056.76  761.47 1059.54
#Mann= 3 , 0 , 0
       0     .11       0  309.23    .047       0  398.89     .11       0
Bank Sta=309.23,398.89
Exp/Cntr=0.5,0.3

Type RM Length L Ch R = 1 ,58409.68,399.77,399.77,470.27
XS GIS Cut Line= 3
  1344717.467763   791825.187823  1344446.977395   791565.068527
  1344078.493043   790855.521774
#Sta/Elev= 30
       0 1078.34  166.97 1073.17  270.04 1066.92  311.03 1061.34  387.31 1053.97
  440.19 1043.76  492.92 1036.36  548.84 1022.18  562.25 1022.73  572.32    1021
  590.75 1020.49  620.74 1016.34  624.83 1014.08  635.91 1011.82   655.5 1012.78
  681.92 1016.28  697.42 1011.12  726.75 1016.62  741.79 1012.36  751.85 1011.04
  756.71 1013.76  757.14 1017.28  794.67 1017.99  822.01 1023.01  842.29 1029.27
  915.06 1042.54  956.05 1047.65 1013.24 1051.56 1091.56  1053.7 1174.79 1059.79
#Mann= 3 , 0 , 0
       0     .11       0  620.74    .047       0  757.14      .1       0
#XS Ineff= 2 , 0
          398.26  1060.3
Permanent Ineff=
       F       F
Bank Sta=620.74,757.14
Exp/Cntr=0.3,0.1

Type RM Length L Ch R = 1 ,58009.9 ,564.89,564.89,774.65
XS GIS Cut Line= 2
  1345273.539444   791683.642351  1344258.387315   790756.969198
#Sta/Elev= 30
       0 1040.55   51.44 1055.85   98.23  1065.9  158.63 1066.57  325.31 1053.92
  377.35 1047.75  422.17 1038.36  444.77 1036.53  467.79 1035.08  507.93 1036.05
  523.11 1040.13   549.2 1041.64  621.62 1037.07  696.86 1028.36  737.63 1018.99
  765.52 1016.53  783.19 1010.75  802.62 1006.89  860.72 1006.89  867.99 1012.02
  911.09 1014.29  953.71 1010.21  961.87 1013.58 1006.02  1013.5 1016.11 1018.24
 1041.75 1025.12 1138.51 1044.01 1175.14 1049.51 1285.89  1057.2  1374.5 1059.27
#Mann= 3 , 0 , 0
       0     .11       0  783.19    .047       0  867.99     .11       0
Bank Sta=783.19,867.99
Exp/Cntr=0.3,0.1

Type RM Length L Ch R = 1 ,57445.01,382.53,382.53,401.14
XS GIS Cut Line= 2
  1345207.399284   790442.860782  1344248.414835   790735.829614
#Sta/Elev= 30
       0 1079.95   47.52 1077.05   71.94 1078.86  102.49 1078.72  155.44 1074.88
  205.82 1073.28     245  1074.6  302.45 1071.43  335.76 1067.59  371.17 1061.54
   411.4 1051.07  469.05 1026.56  493.09  1017.4  501.05 1012.86  504.91 1010.82
  532.75 1003.17  554.95 1003.17  608.65 1013.75  626.66 1009.31  653.09 1014.31
  670.05  1014.2  688.95 1016.32  701.93 1018.59  728.46  1025.7  756.35 1027.33
  812.28 1038.48  882.89 1047.36  910.57 1052.05  938.28 1055.04 1002.74 1059.51
#Mann= 3 , 0 , 0
       0     .11       0  501.05    .047       0  608.65     .11       0
Bank Sta=501.05,608.65
Exp/Cntr=0.3,0.1

Type RM Length L Ch R = 1 ,57062.48,660,660,342.32
XS GIS Cut Line= 3
  1345146.418292   790298.013165  1344723.504499   790175.052269
  1344164.430451   790404.349933
#Sta/Elev= 30
       0 1070.25   35.33 1066.82   57.07 1066.82   99.41 1062.45  112.76 1062.71
  198.52 1056.66  413.43 1035.32  452.55 1033.12  527.56 1020.96  550.46 1013.79
  583.34 1011.66  586.84 1009.41   603.5 1006.87  628.07  1009.3  645.05 1001.97
  660.72 1009.08   681.9 1008.48  686.73 1007.12  703.81 1008.75  709.91 1012.45
   751.6 1011.33  808.86 1012.74  816.09 1016.16  836.77 1019.09  845.43 1022.75
  859.21 1030.36  899.28 1040.45  960.88 1051.28  985.28 1053.42  1044.7 1061.43
#Mann= 3 , 0 , 0
       0     .11       0  583.34    .047       0  709.91     .11       0
Bank Sta=583.34,709.91
Exp/Cntr=0.3,0.1

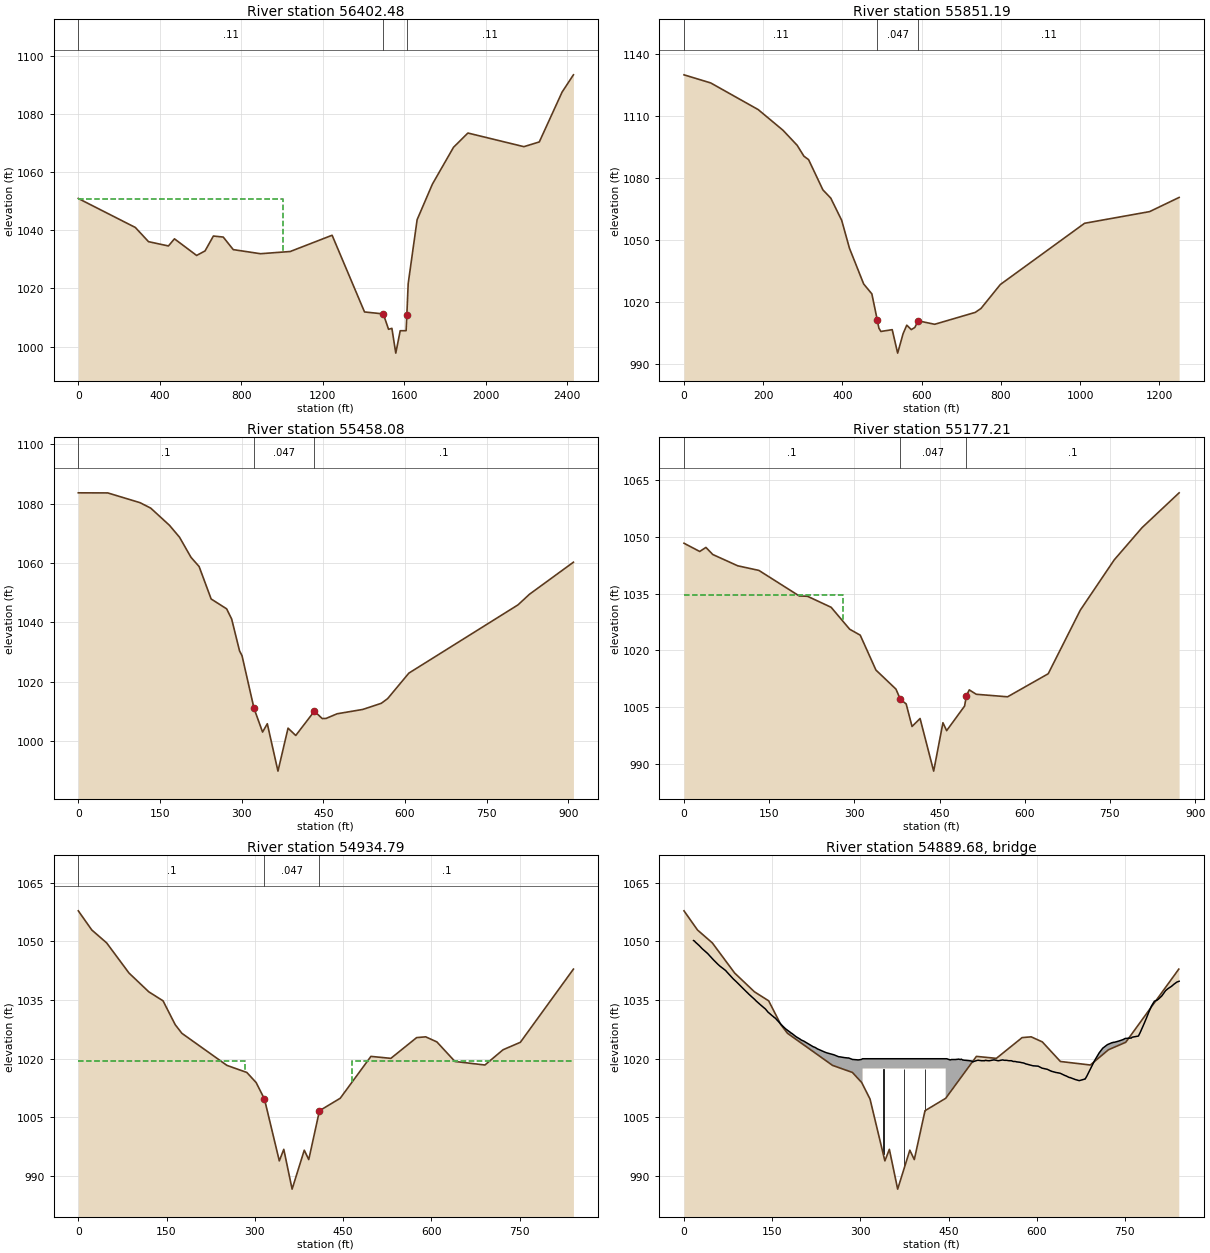
Type RM Length L Ch R = 1 ,56402.48,551.29,551.29,848.93
XS GIS Cut Line= 5
  1346138.652021   790213.478893  1345059.612788   790013.290861
  1344930.797044   790087.660653  1344708.918259   789607.040877
  1344056.140531   789548.013165
#Sta/Elev= 30
       0 1051.01  279.95 1041.03  344.76 1036.13  442.51 1034.65  472.11 1037.11
  580.97 1031.38  622.34 1032.94  663.26 1038.07  711.58 1037.72  760.88 1033.39
  894.58 1031.98 1040.49 1032.74 1246.19 1038.34  1405.3 1011.92 1497.44 1011.24
  1523.4 1005.94 1539.72 1006.27 1558.76  997.73 1580.52 1005.44 1609.48 1005.46
 1613.17 1010.94 1619.74 1021.69 1663.64 1043.71 1738.24  1055.9 1842.03 1068.62
 1912.87 1073.56 2187.78 1068.86 2263.46 1070.49 2375.31 1087.66    2431 1093.61
#Mann= 3 , 0 , 0
       0     .11       0 1497.44    .047       0 1613.17     .11       0
#XS Ineff= 2 , 0
         1003.81 1050.89
Permanent Ineff=
       F       F
Bank Sta=1497.44,1613.17
Exp/Cntr=0.3,0.1

Type RM Length L Ch R = 1 ,55851.19,393.11,393.11,437.47
XS GIS Cut Line= 3
  1345662.887156   789272.472044  1344830.446068   789544.540909
  1344469.335027   789447.318637
#Sta/Elev= 30
       0 1130.09   67.42 1126.16  187.36 1113.22   249.8 1103.22  285.68  1095.9
  302.66 1090.63  314.57 1088.93  350.56  1074.3  370.48 1070.29  398.06  1059.5
  417.64 1045.98  453.52 1028.65  474.17 1023.84  487.83 1011.21  491.91 1007.23
     497 1005.61  525.57 1006.48  539.28   995.1  552.99 1004.51   562.3 1008.66
  573.75 1006.51  582.61 1007.53  590.95 1010.78  632.72 1009.09  735.16 1014.86
  749.63 1016.76  798.51 1028.39 1011.08 1058.08 1175.24 1063.74 1249.74 1070.62
#Mann= 3 , 0 , 0
       0     .11       0  487.83    .047       0  590.95     .11       0
Bank Sta=487.83,590.95
Exp/Cntr=0.3,0.1

Type RM Length L Ch R = 1 ,55458.08,280.87,280.87,292.39
XS GIS Cut Line= 2
  1345291.220852   788906.031852  1344509.970931   789371.309549
#Sta/Elev= 30
       0  1083.6    54.1 1083.57  113.37 1080.29  133.06 1078.45   167.6 1072.65
   185.9 1068.67  206.98 1061.91  221.87 1058.82  243.99  1047.9  272.45 1044.58
  281.66 1041.15  296.16 1030.43  300.73 1028.81  322.72 1011.11  338.41 1003.15
  347.12 1005.94   366.7  990.01   385.2 1004.46  399.35    1002  433.57 1010.17
  447.98 1007.69  454.99 1007.73  475.42  1009.3  522.34 1010.75  556.51 1012.82
   568.2 1014.41  607.09 1022.97  807.51 1045.92  828.58 1049.49   909.3 1060.27
#Mann= 3 , 0 , 0
       0      .1       0  322.72    .047       0  433.57      .1       0
Bank Sta=322.72,433.57
Exp/Cntr=0.3,0.1

Type RM Length L Ch R = 1 ,55177.21,242.42,242.42,210.41
XS GIS Cut Line= 3
  1345210.926324   788761.702764  1345010.112628   788731.488492
  1344456.178547     789106.0915
#Sta/Elev= 30
       0 1048.31   27.69 1046.13   38.61  1047.2   50.67 1045.33   94.53 1042.34
  131.86 1041.12  203.01 1034.35  217.38 1034.28  259.07 1031.36  291.68 1025.56
   310.3 1023.98     338 1014.74  373.17 1009.71  380.89 1007.04  391.19 1005.78
  401.52  999.82  415.67 1001.92  439.61     988  455.93 1000.81  462.46  998.71
     494 1005.21  497.38    1008  502.26  1009.5  514.58 1008.34  569.74 1007.67
  641.29 1013.77  697.86 1030.62  757.57 1043.92  806.55 1052.44  871.78 1061.65
#Mann= 3 , 0 , 0
       0      .1       0  380.89    .047       0  497.38      .1       0
#XS Ineff= 2 , 0
          280.74 1034.57
Permanent Ineff=
       F       F
Bank Sta=380.89,497.38
Exp/Cntr=0.5,0.3

Type RM Length L Ch R = 1 ,54934.79,97.3,97.3,94.85
BEGIN DESCRIPTION:
Upstream xs of Bridge 37003-0046
END DESCRIPTION:
XS GIS Cut Line= 6
  1345007.963252   788301.162988  1344868.776436   788574.778092
  1344576.998387   788706.449132  1344450.499571   788692.208748
  1344310.535923   788532.416236  1344115.782131   788618.107884
#Sta/Elev= 30
       0  1057.8  22.981  1052.9  48.225  1049.6  86.196  1041.9 119.855  1037.1
 144.038  1034.8 164.756  1028.7  176.07  1026.5 252.649  1018.3 286.449  1016.5
 302.359  1013.9  316.43  1009.7  341.68   993.9  349.29  996.85  363.44  986.68
  384.11  996.63  391.73  994.23 409.768  1006.6 409.768  1006.7 445.194  1009.9
 497.379  1020.6  531.32  1020.1  575.09  1025.4 590.505  1025.6 609.526  1024.3
 640.214  1019.3 691.126  1018.4 722.027  1022.3 751.372  1024.2 841.598  1042.9
#Mann= 3 , 0 , 0
       0      .1       0  316.43    .047       0 409.768      .1       0
#XS Ineff= 2 , 0
       0 283.126  1019.4 465.701       0  1019.4
Permanent Ineff=
       F       F
#Block Obstruct= 2 , 0
          213.28 1034.47
Bank Sta=316.43,409.768
Skew Angle= 45
Exp/Cntr=0.5,0.3

Type RM Length L Ch R = 3 ,54889.68,,,
BEGIN DESCRIPTION:
Bridge : 37003-0046 - SR-1110 / Liledoun Rd
END DESCRIPTION:
Bridge Culvert--1,0,-1,-1, 0
Deck Dist Width WeirC Skew NumUp NumDn MinLoCord MaxHiCord MaxSubmerge Is_Ogee
29.1,32,2.6,45, 154, 154, , , 0.95, 0, 0,0,,
  16.193  17.678  19.375  25.314   29.84  31.113  40.164  50.558  57.912  60.882
  71.206  71.559  83.863   89.52  96.167 107.622  108.47 110.309 119.925 123.178
 131.451 138.593 142.977 153.937 154.503 163.695 168.928  173.17 181.302 182.504
 183.282 190.919 196.646 199.333 203.859 219.415  222.88 227.193 230.375 239.426
 243.033 253.215 255.195 263.256  264.67 272.519 278.247 280.014 283.691 287.015
 288.712 296.348  301.44 303.702 303.702 445.124 445.124 446.962 452.619 455.023
 461.529 467.256 470.014  471.64 473.832 477.792 479.348  485.57 489.601 491.439
 492.712 499.288 501.268 505.652 511.733 512.511 516.612 519.794 526.653 527.784
  531.32 533.512 535.492 541.644 545.321 548.573 552.321 554.301 556.705 560.029
 563.211 566.039 571.767 574.383  578.06  581.03 586.121 593.616 601.819 602.384
 609.031 617.941 623.385 623.951 624.941 632.436 639.295 639.719 648.134 650.114
 655.276 656.619 663.832 665.317 670.125 672.246  681.58 682.287 685.328 690.631
 691.904 698.268 705.268 705.622 706.188 712.269 720.118 727.896 729.168 729.805
 731.926 739.139 746.846 750.665 752.291 760.988  762.19 772.938 775.625 782.414
 786.586 790.545 795.212 800.091 805.112 809.567 812.961 819.112 821.658 823.072
 829.153 832.972 838.416 842.164
  1050.2  1050.1  1049.8    1049  1048.3  1048.1  1046.9  1045.2  1044.1  1043.7
  1042.5  1042.4  1040.4  1039.6  1038.6  1036.9  1036.8  1036.5  1035.2  1034.7
  1033.6  1032.7  1031.9  1030.5  1030.5    1029  1028.2  1027.6  1026.7  1026.5
  1026.5  1025.6  1025.1  1024.8  1024.5  1023.1  1022.9  1022.5  1022.3  1021.7
  1021.5  1021.1    1021  1020.5  1020.5  1020.3  1020.2  1020.2    1020  1019.8
  1019.8  1019.7  1019.8    1020    1020    1020    1020    1020  1019.7  1019.8
  1019.8  1019.9  1019.8  1019.9  1019.7  1019.6  1019.6  1019.5  1019.4  1019.2
  1019.3  1019.6  1019.6  1019.5  1019.5  1019.6  1019.5  1019.5  1019.7  1019.7
  1019.6  1019.5  1019.5  1019.7  1019.6  1019.6  1019.5  1019.5  1019.5  1019.3
  1019.3  1019.2  1019.1    1019  1018.9  1018.7  1018.5  1018.2  1018.1  1018.1
  1017.6  1017.3  1016.9  1016.9  1016.8  1016.5  1016.3  1016.3  1015.7  1015.6
  1015.2  1015.2  1014.8  1014.7  1014.5  1014.4  1014.8  1014.8  1015.6  1017.2
  1017.6  1019.5  1021.3  1021.4  1021.5  1022.7  1023.6  1024.1  1024.1  1024.2
  1024.2  1024.5  1024.9  1025.2  1025.2  1025.3  1025.5  1025.8  1026.6  1028.9
  1030.4  1031.9  1033.5  1034.7    1035  1035.6  1036.1  1037.4  1037.7  1037.9
  1038.5    1039  1039.6  1039.8
                                                                                
                                                                                
                                                                                
                                                                                
                                                                                
                                  1017.5  1017.5
                                                                                
                                                                                
                                                                                
                                                                                
                                                                                
                                                                                
                                                                                
                                                                                
                                                                                
                                
  -5.515  -4.031  -2.333   3.606   8.132   9.405  18.455   28.85  36.204  39.174
  49.497  49.851  62.155  67.812  74.458  85.913  86.762    88.6  98.217  101.47
 109.743 116.885 121.269 132.229 132.795 141.987  147.22 151.462 159.594 160.796
 161.574 169.211 174.938 177.625 182.151 197.707 201.172 205.485 208.667 217.718
 221.324 231.507 233.487 241.548 242.962 250.811 256.538 258.306 261.983 265.306
 267.004  274.64 279.731 281.994 281.994 423.416 423.416 425.254 430.911 433.315
  439.82 445.548 448.306 449.932 452.124 456.084 457.639 463.862 467.893 469.731
 471.004  477.58  479.56 483.944 490.025 490.803 494.904 498.086 504.945 506.076
 509.612 511.804 513.784 519.936 523.613 526.865 530.613 532.593 534.997  538.32
 541.502 544.331 550.058 552.675 556.352 559.321 564.413 571.908  580.11 580.676
 587.323 596.232 601.677 602.243 603.233 610.728 617.587 618.011 626.426 628.406
 633.568 634.911 642.124 643.609 648.417 650.538 659.872 660.579  663.62 668.923
 670.196  676.56  683.56 683.914 684.479  690.56 698.409 706.188  707.46 708.097
 710.218  717.43 725.138 728.956 730.583  739.28 740.482  751.23 753.917 760.706
 764.877 768.837 773.504 778.383 783.404 787.858 791.253 797.404  799.95 801.364
 807.445 811.264 816.708 820.456
  1050.2  1050.1  1049.8    1049  1048.3  1048.1  1046.9  1045.2  1044.1  1043.7
  1042.5  1042.4  1040.4  1039.6  1038.6  1036.9  1036.8  1036.5  1035.2  1034.7
  1033.6  1032.7  1031.9  1030.5  1030.5    1029  1028.2  1027.6  1026.7  1026.5
  1026.5  1025.6  1025.1  1024.8  1024.5  1023.1  1022.9  1022.5  1022.3  1021.7
  1021.5  1021.1    1021  1020.5  1020.5  1020.3  1020.2  1020.2    1020  1019.8
  1019.8  1019.7  1019.8  1019.9  1019.9  1019.9  1019.9    1020  1019.7  1019.8
  1019.8  1019.9  1019.8  1019.9  1019.7  1019.6  1019.6  1019.5  1019.4  1019.2
  1019.3  1019.6  1019.6  1019.5  1019.5  1019.6  1019.5  1019.5  1019.7  1019.7
  1019.6  1019.5  1019.5  1019.7  1019.6  1019.6  1019.5  1019.5  1019.5  1019.3
  1019.3  1019.2  1019.1    1019  1018.9  1018.7  1018.5  1018.2  1018.1  1018.1
  1017.6  1017.3  1016.9  1016.9  1016.8  1016.5  1016.3  1016.3  1015.7  1015.6
  1015.2  1015.2  1014.8  1014.7  1014.5  1014.4  1014.8  1014.8  1015.6  1017.2
  1017.6  1019.5  1021.3  1021.4  1021.5  1022.7  1023.6  1024.1  1024.1  1024.2
  1024.2  1024.5  1024.9  1025.2  1025.2  1025.3  1025.5  1025.8  1026.6  1028.9
  1030.4  1031.9  1033.5  1034.7    1035  1035.6  1036.1  1037.4  1037.7  1037.9
  1038.5    1039  1039.6  1039.8
                                                                                
                                                                                
                                                                                
                                                                                
                                                                                
                                  1017.4  1017.4
                                                                                
                                                                                
                                                                                
                                                                                
                                                                                
                                                                                
                                                                                
                                                                                
                                                                                
                                
Pier Skew, UpSta & Num, DnSta & Num=  ,339.058, 2 ,317.35, 2 , 0 , 0 , 0 ,,
       1       1
  1002.7    1018
       1       1
 1002.61 1017.91
Pier Skew, UpSta & Num, DnSta & Num=  ,374.413, 2 ,352.705, 2 , 0 , 0 , 0 ,,
       1       1
  1006.1    1018
       1       1
 1006.01 1017.91
Pier Skew, UpSta & Num, DnSta & Num=  ,409.768, 2 ,388.06, 2 , 0 , 0 , 0 ,,
       1       1
  1005.7    1018
       1       1
 1005.61 1017.91
BR Coef=-1 , 1 , 0 ,, 0 ,,,0.8,0,1.2,0,
WSPro=,,,, 1 ,,,, 0 ,,,, 0 ,,,,-1 ,-1 ,-1 , 0 , 0 , 0 , 0 , 0
BC Design=,, 0 ,, 0 ,,,,,,

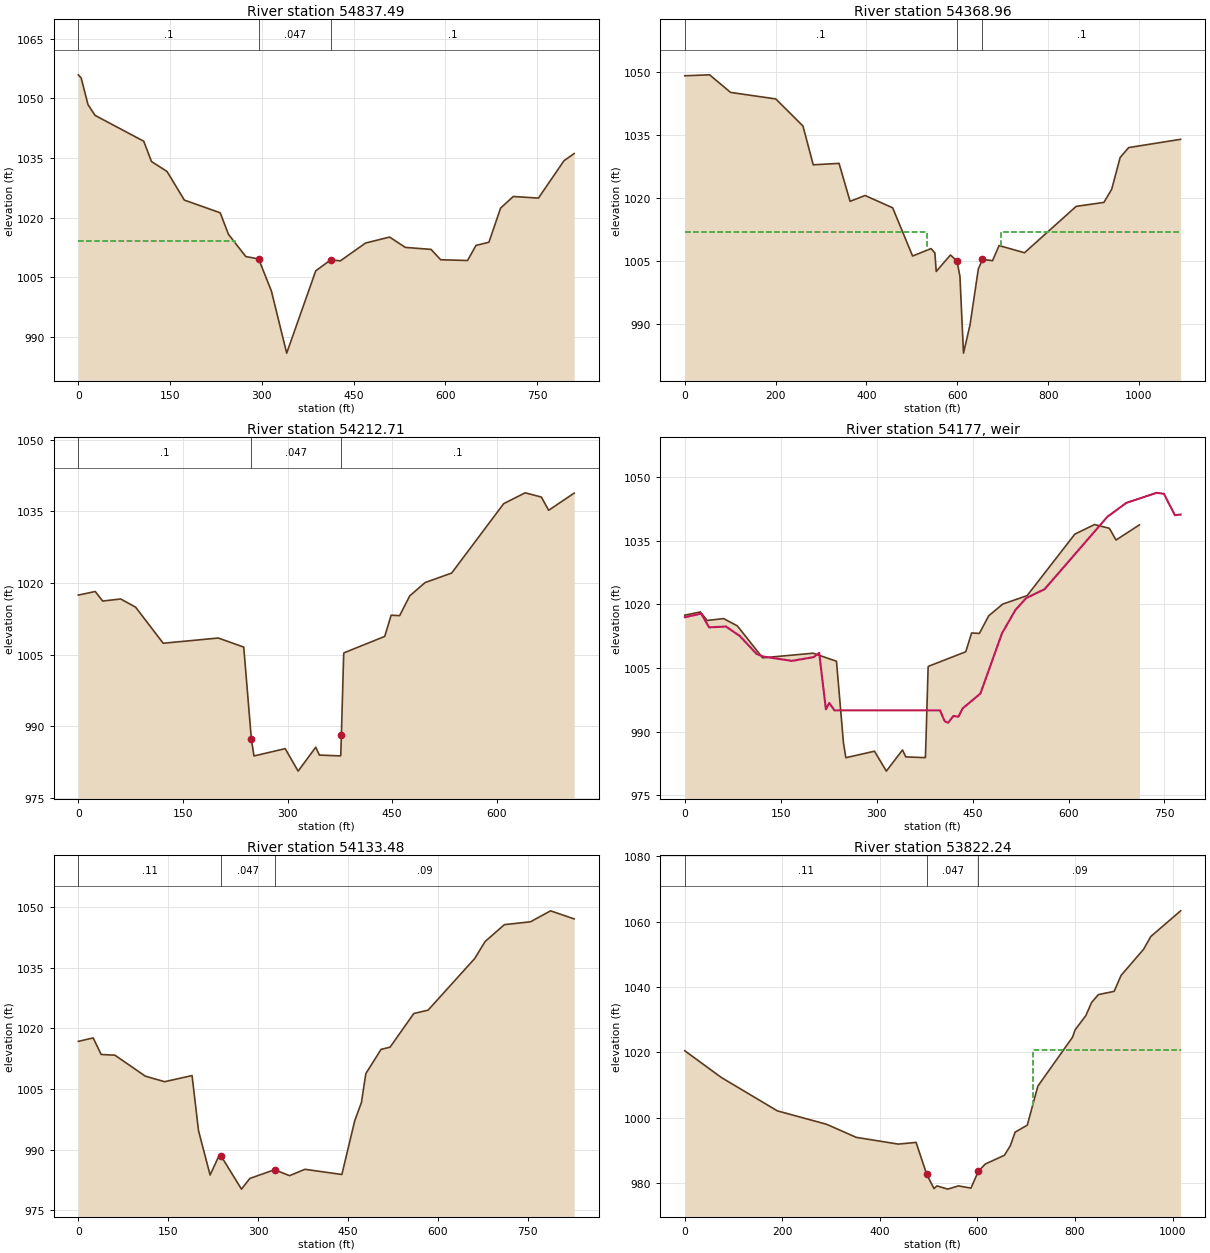
Type RM Length L Ch R = 1 ,54837.49,468.52,468.52,470.76
BEGIN DESCRIPTION:
Down stream xs of Bridge 37003-0046
END DESCRIPTION:
XS GIS Cut Line= 6
  1344940.038388   788252.816747  1344824.342388    788491.89694
  1344556.550003   788612.178924  1344483.830131   788602.981996
  1344330.825075   788420.001004  1344086.125683   788527.668716
#Sta/Elev= 30
       0  1055.9   4.667  1055.1  15.839  1048.4  27.365  1045.7 106.915  1039.2
 119.572  1034.1 144.957  1031.6 173.312  1024.4 231.931  1021.2 245.366  1015.8
 273.721  1010.2 294.722  1009.6  315.56 1001.56  340.59  985.91  388.06  1006.6
 412.809  1009.4 428.153  1009.1 469.519  1013.6 508.763  1015.1 534.502  1012.5
 576.575    1012 592.273  1009.4 636.184  1009.2 650.043    1013 671.186  1013.8
 690.278  1022.4 710.996  1025.3 752.079  1024.9 793.869  1034.3 810.486  1036.1
#Mann= 3 , 0 , 0
       0      .1       0 294.722    .047       0 412.809      .1       0
#XS Ineff= 2 , 0
       0 256.397    1014     493       0    1014
Permanent Ineff=
       F       F
#Block Obstruct= 2 , 0
          221.98 1030.62
Bank Sta=294.722,412.809
Skew Angle= 45
Exp/Cntr=0.5,0.3

Type RM Length L Ch R = 1 ,54368.96,156.25,156.25,58.78
XS GIS Cut Line= 2
  1344910.280052   787950.329707  1343920.045683   788410.290668
#Sta/Elev= 30
       0  1049.1   54.57 1049.32  100.95 1045.13  200.37 1043.58  260.25 1037.13
  282.84  1027.9   339.7 1028.24  363.95  1019.2  397.02 1020.59  457.75 1017.66
  501.62 1006.18  542.21 1007.95  550.75 1006.92  553.65  1002.5  584.98 1006.43
  599.35 1004.99  605.88 1001.35  613.71  983.06  628.07  989.77  646.35 1003.08
   655.5 1005.38  677.69 1005.07     692 1008.67  748.06 1006.96  861.86    1018
  922.94 1018.95  940.02 1022.06  958.71 1029.65   977.5    1032 1091.85 1033.97
#Mann= 3 , 0 , 0
       0      .1       0  599.35    .047       0   655.5      .1       0
#XS Ineff= 2 , 0
          532.47 1011.81  696.31         1011.91
Permanent Ineff=
       F       F
#Block Obstruct= 2 , 0
          440.04  1028.5
Bank Sta=599.35,655.5
Exp/Cntr=0.5,0.3

Type RM Length L Ch R = 1 ,54212.71,79.24001,79.24001,22.46
XS GIS Cut Line= 5
  1344549.479027   788060.825195  1344417.645043   788101.168107
  1344384.048627   788031.146731  1344015.562099   788171.452267
  1343970.393587   788261.789035
#Sta/Elev= 30
       0 1017.47   24.29 1018.22   34.88 1016.22   60.64 1016.66   82.09 1014.95
  121.65  1007.4   200.7 1008.49  237.15 1006.59   248.1  987.31  251.81  983.83
  296.58  985.36  315.13  980.66  340.37  985.66  345.59  984.02  375.69  983.84
   376.2  983.93  377.12   988.2   380.4 1005.06  380.79 1005.39  439.26 1008.83
  448.42 1013.26  460.64 1013.17  475.12 1017.31  497.17 1020.09  535.25 1022.08
  609.83 1036.59  640.57 1038.85  663.81 1037.97  674.26  1035.2  710.83 1038.79
#Mann= 3 , 0 , 0
       0      .1       0   248.1    .047       0  377.12      .1       0
#Block Obstruct= 2 , 0
          116.65 1023.58
Bank Sta=248.1,377.12
Exp/Cntr=0.5,0.3

Type RM Length L Ch R = 5 ,54177   ,,,
BEGIN DESCRIPTION:
DAM
END DESCRIPTION:
IW Pilot Flow=0
#Inline Weir SE= 30
       0 1016.98   25.68 1017.84    37.9 1014.59   64.37 1014.78   85.89 1012.56
  112.43  1008.3  122.35 1007.71  167.43 1006.68   201.2 1007.55  210.12 1008.57
  220.62  995.23   225.9  996.74  234.02     995  399.04     995   406.4  992.43
  411.66  992.07  419.91  993.67  427.88  993.52  434.45  995.46  462.22  998.97
  495.88 1013.17   516.9 1018.68   533.6 1021.48  562.49 1023.59  660.58 1040.67
  690.27 1043.96  737.57 1046.34  749.13 1046.11  766.17 1041.06  775.22 1041.22
IW Dist,WD,Coef,Skew,MaxSub,Min_El,Is_Ogee,SpillHt,DesHd
69,10,2.6,0,0.95,, 0 ,,,0,0,

Type RM Length L Ch R = 1 ,54133.48,311.23,311.23,440.38
XS GIS Cut Line= 5
  1344545.640307   788039.711851  1344438.154099   788070.422251
  1344396.034035   787951.668587  1343965.154291   788116.382699
  1343907.783667   788231.123947
#Sta/Elev= 30
       0 1016.77   24.76 1017.63   38.08 1013.53   61.07 1013.35  111.79 1008.16
  144.03 1006.79  189.77 1008.31  200.56  994.68   219.9  983.69  235.78  988.81
  237.79   988.5   272.2   980.2  286.23  982.85  327.43     985  352.52  983.53
  378.11  985.11  439.72  983.82  461.33  997.19  472.37 1001.62  479.73 1008.79
  505.21 1014.79  520.21 1015.34  559.81 1023.67  583.67  1024.5  661.43 1037.28
  678.68 1041.47  710.98 1045.66  754.54 1046.37  787.98 1049.08  827.36 1047.08
#Mann= 3 , 0 , 0
       0     .11       0  237.79    .047       0  327.43     .09       0
#Block Obstruct= 2 , 0
          110.99 1022.13
Bank Sta=237.79,327.43
Exp/Cntr=0.5,0.3

Type RM Length L Ch R = 1 ,53822.24,525.64,525.64,334.03
XS GIS Cut Line= 6
  1344672.700787   787901.257451  1344573.091315   787830.945003
  1344560.823283   787662.671083  1344130.159219   787708.813675
  1344092.668403   787769.101035  1343882.829555   787840.512235
#Sta/Elev= 30
       0 1020.51   74.76 1012.35  189.77 1002.12  290.45  998.03  351.59  994.01
   437.6  991.95  474.19  992.47  495.89   982.7  510.88  978.33  516.94  979.16
  539.11  978.17  561.17  979.16   586.6  978.48  601.75  983.61  616.07  985.86
  655.25  988.53  667.38  991.46   677.1   995.6  702.12  997.75  723.82  1009.7
  794.81 1024.65  800.21 1026.93   822.3 1031.31  833.86 1035.28  847.82  1037.7
  880.24  1038.7  894.41 1043.59  940.44 1051.55  955.37 1055.49 1016.47 1063.34
#Mann= 3 , 0 , 0
       0     .11       0  495.89    .047       0  601.75     .09       0
#XS Ineff= 2 , 0
                          712.95          1020.9
Permanent Ineff=
       F       F
#Block Obstruct= 2 , 0
          335.58 1015.49
Bank Sta=495.89,601.75
Exp/Cntr=0.3,0.1