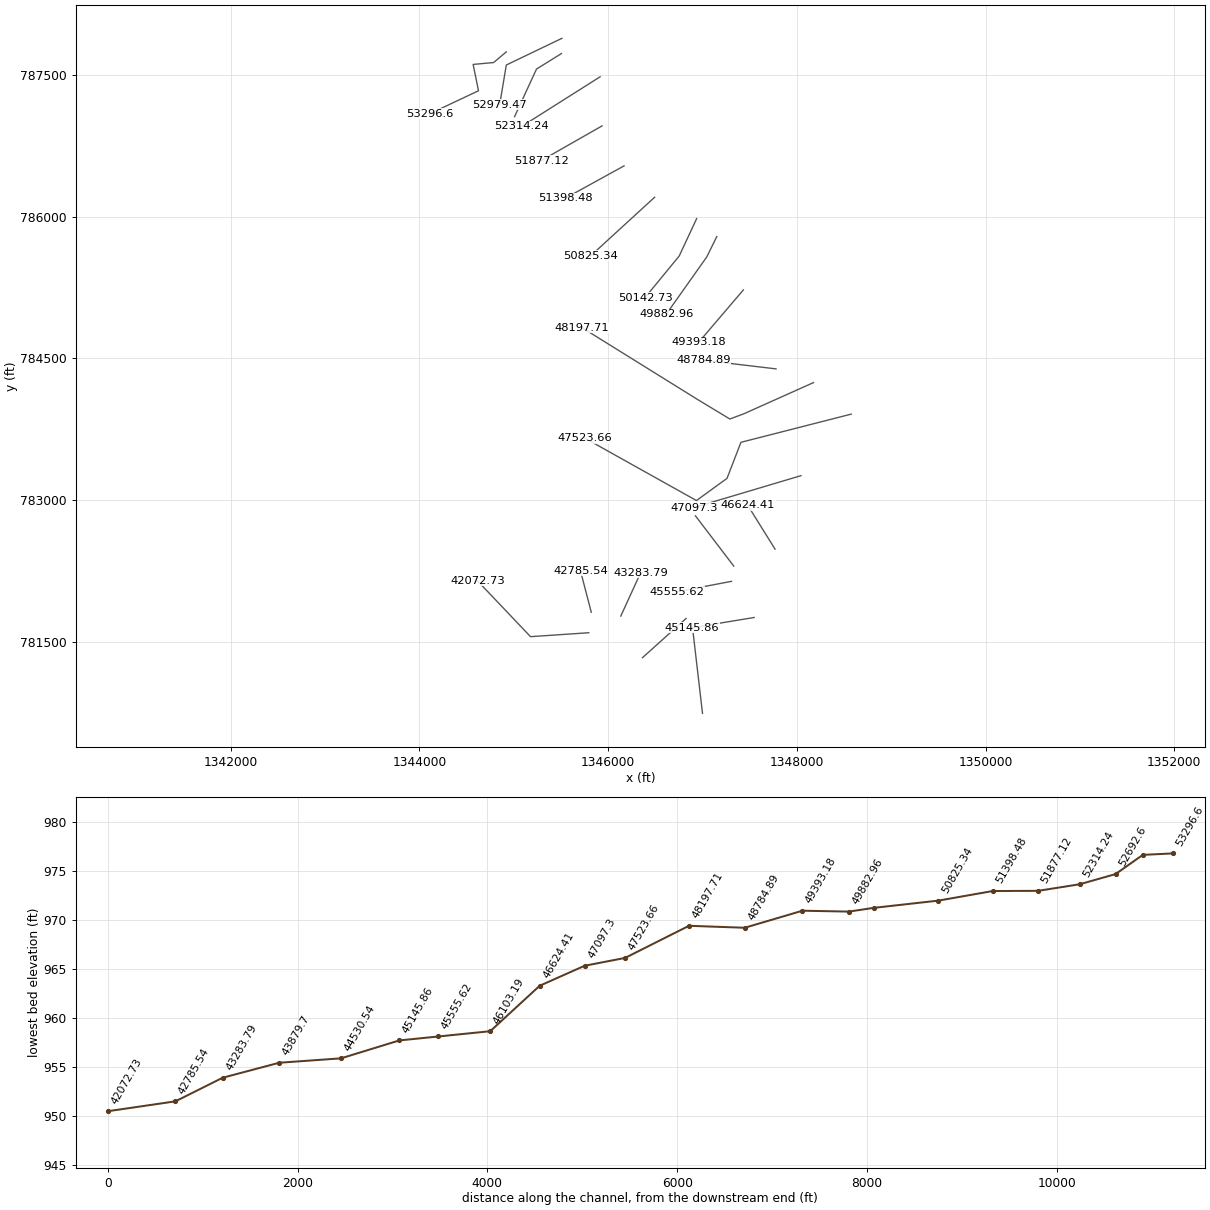
HEC-RAS study LLRiver.prj: LLRiver

--- LLRiver.g01 (geometry) --- (continued)

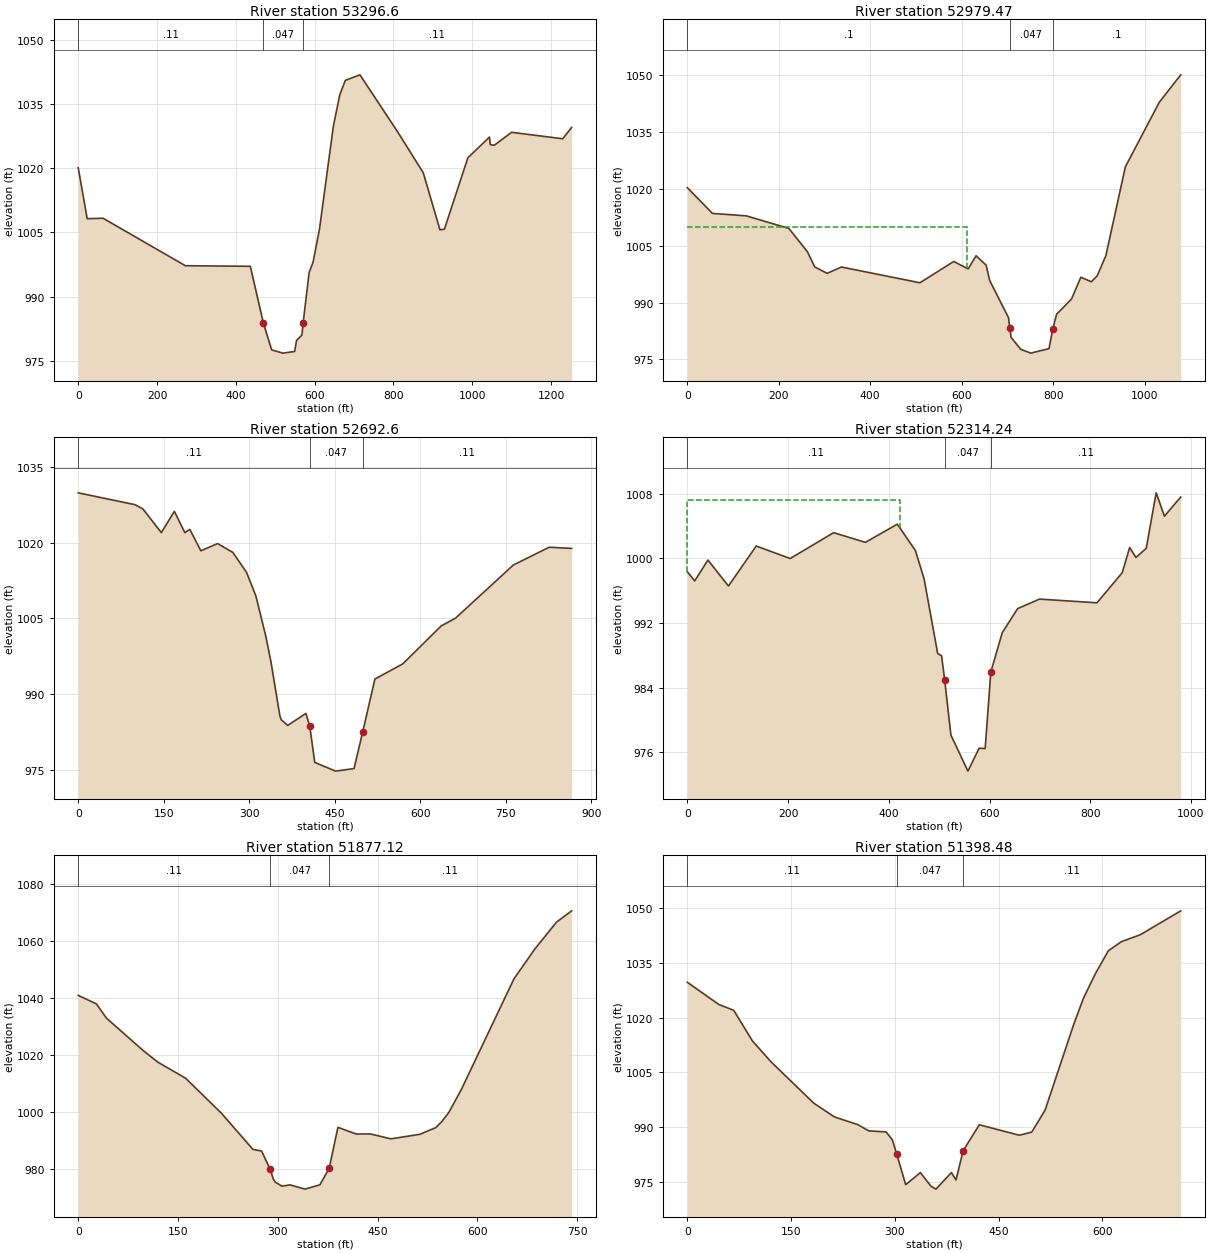
Type RM Length L Ch R = 1 ,53296.6 ,317.13,317.13,181.94
XS GIS Cut Line= 5
  1344921.166964   787744.519147  1344786.401267   787631.726187
  1344569.715571   787611.892203  1344626.333811   787332.845291
  1344106.659571   787088.173802
#Sta/Elev= 30
       0 1020.09    22.8 1008.19   63.22 1008.29   271.9  997.22  436.88  997.08
  470.11  983.81  491.04  977.57  519.54  976.82  549.34   977.2  554.22  979.79
  567.91  981.05  570.85  983.81  586.11  995.62  596.32   998.1  612.59 1005.85
  647.72 1029.81  663.97  1037.1  678.06 1040.47  715.07 1041.76  809.38 1028.66
  875.83 1018.91  918.21  1005.6  929.53 1005.74   989.1 1022.41 1043.94 1027.24
 1046.01 1025.47 1056.21 1025.33 1099.98 1028.35 1229.69 1026.84 1252.45 1029.49
#Mann= 3 , 0 , 0
       0     .11       0  470.11    .047       0  570.85     .11       0
Bank Sta=470.11,570.85
Exp/Cntr=0.3,0.1

Type RM Length L Ch R = 1 ,52979.47,286.88,286.88,248.67
XS GIS Cut Line= 3
  1345510.432628   787888.142955    1344921.1749   787605.542123
  1344850.862324   787185.864426
#Sta/Elev= 30
       0 1020.37   55.04 1013.56  128.92 1012.92  222.03  1009.6  262.73 1003.43
   278.6  999.43  305.82  997.74  337.07  999.41  508.67  995.25  582.61 1000.87
  614.21  998.91  631.48 1002.38  653.52  999.89  661.01  995.92  702.42  986.02
  705.17  983.43  707.93  980.85  729.24  977.67  751.18  976.67  790.95  977.86
  799.26  983.05  807.51  986.92   840.2  990.96  860.68  996.72  883.52  995.51
  896.27  997.07  915.29 1002.39  957.97 1025.87 1032.27 1042.94 1079.05 1050.16
#Mann= 3 , 0 , 0
       0      .1       0  705.17    .047       0  799.26      .1       0
#XS Ineff= 2 , 0
           612.4 1010.01
Permanent Ineff=
       F       F
Bank Sta=705.17,799.26
Exp/Cntr=0.3,0.1

Type RM Length L Ch R = 1 ,52692.6 ,378.35,378.35,453.33
XS GIS Cut Line= 3
  1345504.670964   787726.635883  1345240.999028   787562.573419
   1345008.57714   787058.667114
#Sta/Elev= 30
       0 1029.93   99.79 1027.57  113.43 1026.74  145.81 1022.04   168.7 1026.26
  186.95 1022.04  195.76 1022.67  215.13 1018.43  244.45 1019.86  271.09 1018.12
  295.15 1014.17  311.54  1009.5  328.94 1001.53   338.1   996.4  353.77  985.63
  356.06  984.92  367.45  983.78  399.41  986.16  406.21  983.57  414.91  976.44
  451.42  974.71  483.81  975.22  499.08  982.51  520.36  992.97  569.38     996
  636.84 1003.54  661.68 1005.05  763.15  1015.6  826.18 1019.14  865.47  1018.9
#Mann= 3 , 0 , 0
       0     .11       0  406.21    .047       0  499.08     .11       0
Bank Sta=406.21,499.08
Exp/Cntr=0.3,0.1

Type RM Length L Ch R = 1 ,52314.24,437.12,437.12,446.34
XS GIS Cut Line= 2
  1345914.827253   787480.542187  1345086.702196   786957.104618
#Sta/Elev= 30
       0  998.34   14.68  997.21   40.96  999.79   81.68  996.58  136.87 1001.53
  204.23  999.98  290.55 1003.18  353.51 1001.98  416.93 1004.23  452.75 1000.98
  470.07  997.48  497.09  988.22  504.83  987.95  511.07  984.92  523.35  978.13
  557.15  973.67  579.32   976.5  591.39  976.47  602.59  985.93  625.35  990.81
  655.84  993.78  699.26  994.96  813.38   994.5  863.54  998.23  878.26 1001.34
  890.76 1000.11  911.21 1001.25   930.9 1008.11  947.31 1005.22  979.68 1007.59
#Mann= 3 , 0 , 0
       0     .11       0  511.07    .047       0  602.59     .11       0
#XS Ineff= 2 , 0
           422.2 1007.26
Permanent Ineff=
       F       F
Bank Sta=511.07,602.59
Exp/Cntr=0.3,0.1

Type RM Length L Ch R = 1 ,51877.12,478.64,478.64,481.65
XS GIS Cut Line= 2
  1345936.311541   786961.010922   1345291.78034   786593.823338
#Sta/Elev= 30
       0 1040.99   27.39 1037.98   42.37 1033.01   98.11 1021.54  119.61 1017.56
  161.51 1011.91  215.31  999.63  262.67  986.93  275.63  986.38  288.63  979.95
  293.26  976.54  296.23  975.47  306.32  974.04  318.47   974.5  340.92     973
  363.36  974.52   377.3  980.31  390.43  994.68  418.06  992.32  438.96  992.37
  470.22  990.64   513.7  992.24  537.59  994.58  546.65  996.69  557.27  999.95
  575.99 1007.96   655.1 1046.78  686.12 1057.14  719.09 1066.68  741.79 1070.64
#Mann= 3 , 0 , 0
       0     .11       0  288.63    .047       0   377.3     .11       0
Bank Sta=288.63,377.3
Exp/Cntr=0.3,0.1

Type RM Length L Ch R = 1 ,51398.48,573.14,573.14,524.93
XS GIS Cut Line= 2
  1346168.733429   786537.182826  1345543.733492    786193.43281
#Sta/Elev= 30
       0 1029.69   45.59 1023.59   67.01 1022.01   94.19 1013.59  120.96 1007.89
  182.89  996.53  212.84  992.76   246.8  990.64  262.34  988.94   287.2  988.67
  296.28  986.54  302.58  982.65  315.71   974.2   336.9  977.51  352.17   973.8
  359.34  972.98  381.77  977.52  388.43  975.49  398.68  983.47  422.08  990.62
  480.03  987.75  497.93  988.62  517.19  994.63  558.85 1018.29  572.61 1025.29
  589.73 1031.99  608.74 1038.34  627.67 1040.83  654.75 1042.71  713.29 1049.27
#Mann= 3 , 0 , 0
       0     .11       0  302.58    .047       0  398.68     .11       0
Bank Sta=302.58,398.68
Exp/Cntr=0.3,0.1

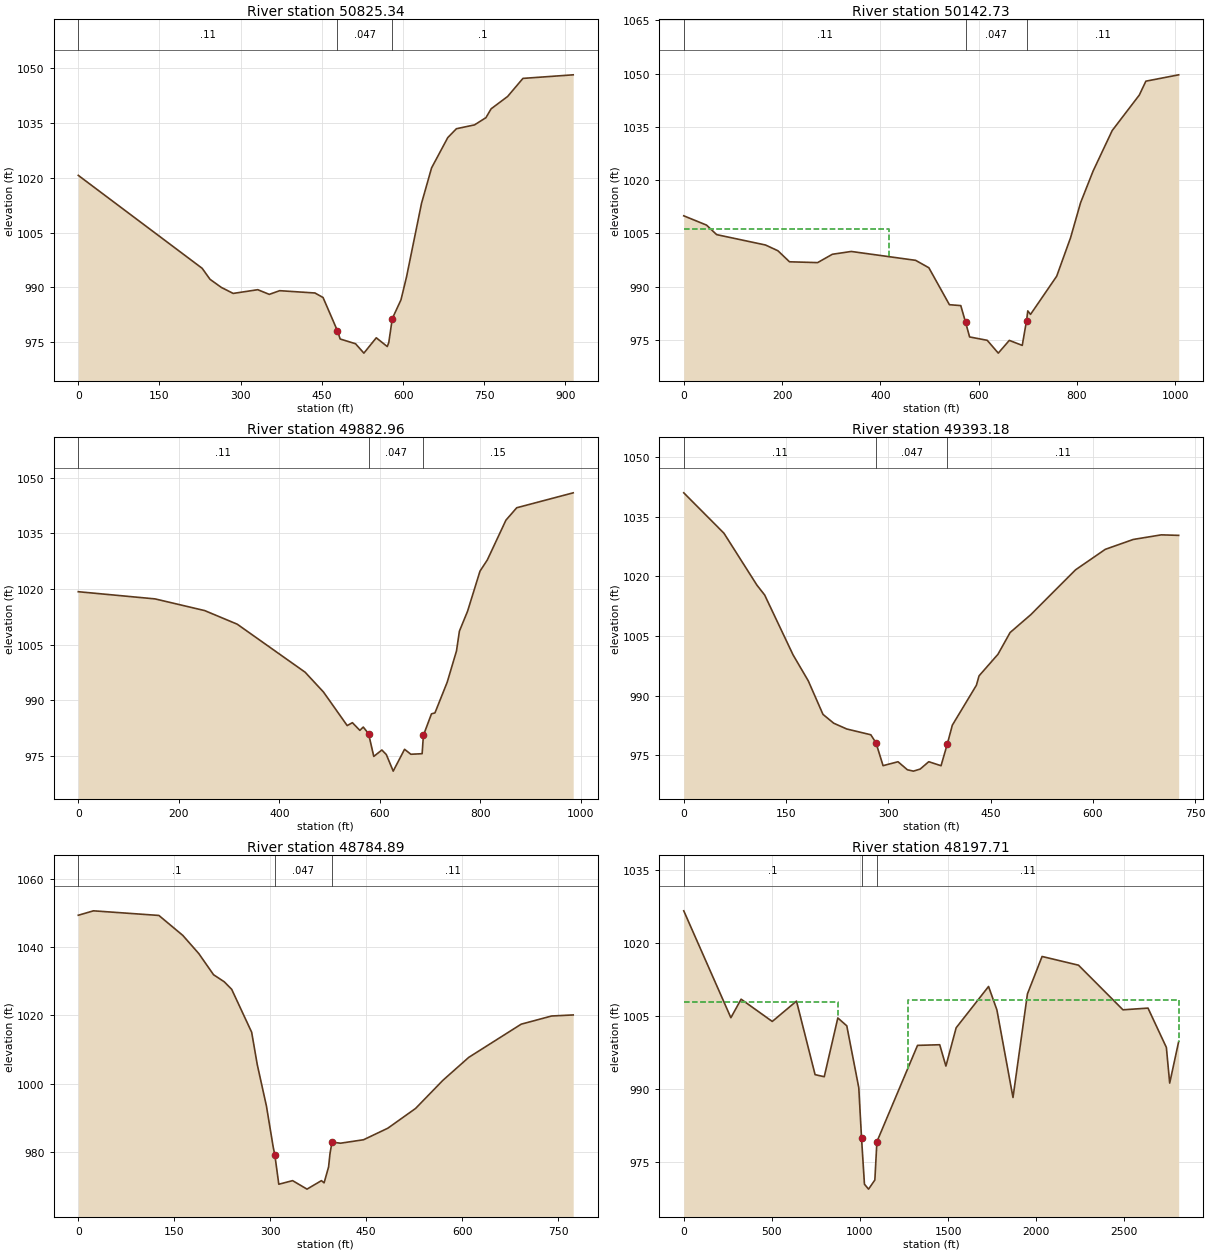
Type RM Length L Ch R = 1 ,50825.34,682.61,682.61,654.33
XS GIS Cut Line= 2
  1346492.952181   786205.151466  1345818.473076   785587.964009
#Sta/Elev= 30
       0 1020.71   228.9  995.23   243.4  992.22  264.31     990  286.17  988.36
  331.56  989.38  352.87   988.1  371.97  989.11  437.18  988.48  452.14  987.24
  478.56  978.18  483.77  975.87  512.18  974.57  527.58     972  550.45   976.2
  570.74  973.81  573.56  974.89  580.06  981.47  596.08   986.6   606.4  992.92
  634.05 1013.05  652.62 1022.76  682.58 1031.07  698.53 1033.49  731.92 1034.54
  753.03 1036.52  762.64 1038.95   793.1 1042.33  821.36 1047.28  914.24 1048.26
#Mann= 3 , 0 , 0
       0     .11       0  478.56    .047       0  580.06      .1       0
Bank Sta=478.56,580.06
Exp/Cntr=0.3,0.1

Type RM Length L Ch R = 1 ,50142.73,259.76,259.76,245.28
XS GIS Cut Line= 3
  1346938.264693   785978.589033  1346753.368821   785582.755689
  1346391.389685   785142.651497
#Sta/Elev= 30
       0 1009.94   46.29 1007.33   67.01 1004.64  166.29 1001.72  191.52  1000.1
  215.12  996.99  272.27  996.76   302.3  999.11  340.74   999.9  471.67   997.4
  498.58  995.31   540.4   984.9  563.51  984.65  573.23  979.97  581.46  975.82
  617.34  974.87  639.78  971.26  662.21  974.85  688.52  973.44  697.28  980.38
  699.79  983.16  705.39  982.17  758.56  992.92  786.78 1003.75  807.16 1013.62
  832.72 1022.57  871.45 1033.95  926.64 1043.96  940.01 1047.87 1006.73 1049.66
#Mann= 3 , 0 , 0
       0     .11       0  573.23    .047       0  697.28     .11       0
#XS Ineff= 2 , 0
          416.54  1006.1
Permanent Ineff=
       F       F
Bank Sta=573.23,697.28
Exp/Cntr=0.3,0.1

Type RM Length L Ch R = 1 ,49882.96,489.78,489.78,507.89
XS GIS Cut Line= 3
  1347151.806326   785788.484841   1347045.03551   785572.339049
  1346615.348085   784965.568232
#Sta/Elev= 30
       0 1019.29  152.75 1017.35  251.38  1014.2  316.16 1010.53  451.25  997.57
  487.87  992.21  534.97  983.17  545.32  983.95  560.15  981.88  566.93  982.77
  577.47  980.98  587.86  974.85  603.94  976.58  612.86  975.34  626.51  970.88
  649.09  976.77  661.63  975.43  684.04  975.58  686.55  980.51  702.59  986.33
  709.54  986.59  733.89  994.86  752.41 1003.31   758.2 1008.64   774.5 1014.05
  799.17 1024.84  813.74 1027.86   850.7 1038.58  872.21 1041.94  984.59 1045.97
#Mann= 3 , 0 , 0
       0     .11       0  577.47    .047       0  686.55     .15       0
Bank Sta=577.47,686.55
Exp/Cntr=0.3,0.1

Type RM Length L Ch R = 1 ,49393.18,608.28,608.28,806.58
XS GIS Cut Line= 2
  1347433.056374   785223.380713  1346961.702262   784671.297384
#Sta/Elev= 30
       0 1041.03   58.96 1030.86  107.31  1017.8   118.7  1015.3  160.35 1000.23
  182.61  993.71   204.2  985.26  219.97  983.03  239.03  981.58  274.39  980.12
  282.01  978.07  292.33  972.35  314.26  973.33  328.02  971.31  336.81  970.97
  346.72  971.48  359.36  973.34  377.38  972.33  386.51  977.77  393.97  982.55
  429.24  992.59  433.12  994.95  460.88 1000.39  478.68 1005.86   508.9 1010.34
  574.59 1021.64  618.35 1026.81  659.28 1029.29  700.44 1030.45  725.93 1030.32
#Mann= 3 , 0 , 0
       0     .11       0  282.01    .047       0  386.51     .11       0
Bank Sta=282.01,386.51
Exp/Cntr=0.3,0.1

Type RM Length L Ch R = 1 ,48784.89,587.18,587.18,480.33
XS GIS Cut Line= 2
   1347779.41055   784387.443176  1347011.181302   784478.589032
#Sta/Elev= 30
       0 1049.28   23.77 1050.57  125.99 1049.22  163.37 1043.39  188.36 1038.08
   211.4  1031.9  228.18 1029.83  239.82 1027.62  271.01 1015.09  279.76 1005.63
  294.12   993.5  304.58  981.63  307.29  979.15  313.42  970.66  335.01  971.71
  357.53  969.23  380.06  971.71  384.24  971.06  391.28  975.74  393.36  979.48
  396.54  982.98   409.8  982.65  445.86  983.66  483.82  987.03  527.23  992.81
  569.76    1001  610.27 1007.73  692.31 1017.44  739.87 1019.83  773.62 1020.14
#Mann= 3 , 0 , 0
       0      .1       0  307.29    .047       0  396.54     .11       0
Bank Sta=307.29,396.54
Exp/Cntr=0.3,0.1

Type RM Length L Ch R = 1 ,48197.71,674.05,674.05,494.55
XS GIS Cut Line= 5
  1348176.907255   784242.505448  1347436.011126   783910.816871
  1347289.799286   783856.738535  1346945.300341   784065.040232
  1345723.864436   784823.806056
#Sta/Elev= 30
       0 1026.56   267.4 1004.62  325.47 1008.42  502.28 1003.85   639.7 1008.03
  745.16  992.93  797.14   992.5  874.23 1004.57  925.04 1002.95  993.06  990.26
 1008.71  979.92 1025.26  970.44 1048.55  969.43 1084.28   971.3 1095.98  979.17
 1326.38  998.94 1452.34  999.07 1487.44  994.69 1545.55 1002.55 1729.47 1011.03
  1776.7 1006.23 1868.14  988.24  1950.1 1009.51 2033.15 1017.19 2239.82  1015.4
 2492.14 1006.24 2634.15 1006.59 2738.33  998.52  2757.2   991.2 2808.15  999.72
#Mann= 3 , 0 , 0
       0      .1       0 1008.71    .047       0 1095.98     .11       0
#XS Ineff= 2 , 0
          874.86 1007.88 1269.86         1008.17
Permanent Ineff=
       F       F
Bank Sta=1008.71,1095.98
Exp/Cntr=0.3,0.1

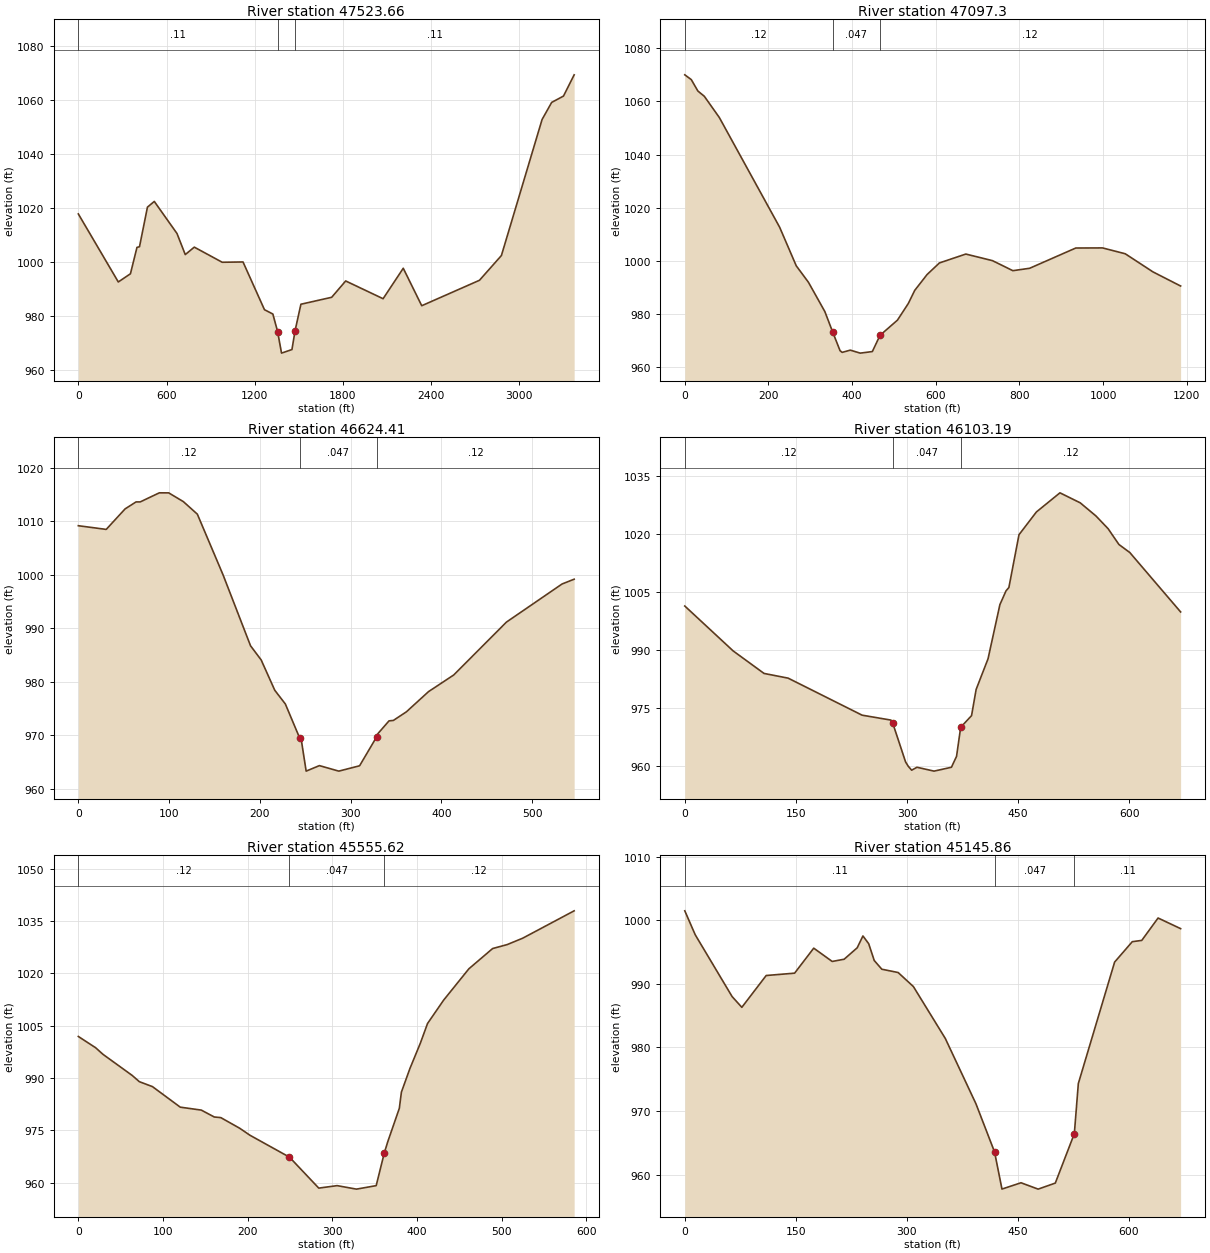
Type RM Length L Ch R = 1 ,47523.66,426.36,426.36,611.32
XS GIS Cut Line= 5
  1348575.930743   783908.188391  1347407.618678   783609.819495
   1347260.20095   783228.050151  1346936.175989   782993.043047
  1345750.458484   783655.335655
#Sta/Elev= 30
       0  1017.8  271.91  992.56  354.54  995.59  398.96 1005.38  416.19 1005.63
  470.23 1020.32  516.78 1022.44  671.42 1010.53  727.51 1002.71  788.94 1005.48
  978.91  999.87 1120.49  999.98 1266.52  982.26 1323.59  980.66 1356.09  974.09
 1382.52  966.15 1453.41  967.48 1474.48  974.42 1514.32  984.29 1723.75  986.87
 1819.01  992.93 2073.51  986.34 2210.75  997.64 2336.44  983.74 2729.31  993.18
 2878.55 1002.37 3155.23 1052.84 3220.43 1059.18 3300.91 1061.54 3373.47 1069.42
#Mann= 3 , 0 , 0
       0     .11       0 1356.09    .047       0 1474.48     .11       0
Bank Sta=1356.09,1474.48
Exp/Cntr=0.3,0.1

Type RM Length L Ch R = 1 ,47097.3 ,472.88,472.88,736.4
XS GIS Cut Line= 2
  1348043.557751   783256.535783  1346907.690229   782918.268007
#Sta/Elev= 30
       0 1070.02   15.54 1068.22   31.21 1063.94   46.65 1061.95    82.5 1053.98
  226.76 1012.69  266.41  998.19  295.56     992  334.74  980.99  353.14  973.43
  371.07  966.29  376.16  965.63  395.57  966.47  419.37  965.35  448.31  965.94
  466.64  972.04  508.31  977.76  534.24  984.01  549.62  988.95  579.15  994.91
  608.59  999.27  671.74 1002.61  735.33 1000.14  784.17  996.36  824.28  997.26
  934.53 1004.88  998.53 1004.92  1052.8 1002.72 1119.09   995.9 1185.17  990.59
#Mann= 3 , 0 , 0
       0     .12       0  353.14    .047       0  466.64     .12       0
Bank Sta=353.14,466.64
Exp/Cntr=0.3,0.1

Type RM Length L Ch R = 1 ,46624.41,521.23,521.23,503.48
XS GIS Cut Line= 2
   1347768.99391    782478.58903  1347479.931382   782942.130663
#Sta/Elev= 30
       0  1009.2   30.73 1008.51   51.57 1012.35   63.58 1013.65   68.18 1013.65
   89.25 1015.35   99.59 1015.34  115.68 1013.71  131.13 1011.36  159.54  999.98
  189.73  986.75  201.46   984.1  216.44  978.43  228.11  975.86  243.72  969.56
  245.72   969.1  251.01  963.31   265.6  964.34     287  963.31  309.89  964.31
  328.72  969.73  329.66  970.24  342.33  972.71  347.11  972.79  361.45   974.4
  385.81  978.17  413.61  981.29   471.7  991.18  532.94   998.3  546.29   999.2
#Mann= 3 , 0 , 0
       0     .12       0  243.72    .047       0  328.72     .12       0
Bank Sta=243.72,328.72
Exp/Cntr=0.3,0.1

Type RM Length L Ch R = 1 ,46103.19,547.57,547.57,324.74
XS GIS Cut Line= 2
  1347331.493878   782298.901478  1346925.437173   782831.024358
#Sta/Elev= 30
       0 1001.36    65.3  989.75  106.97  983.93  139.56  982.71  239.31  973.14
  278.45  971.86  280.75  971.06  298.05  961.05  301.62  959.94  306.26  958.91
   313.4  959.67  336.51  958.67  359.95  959.67  366.87  962.49  372.45  970.01
  387.12  973.02  393.29  979.78  409.38  987.72  425.37 1001.71  433.64 1005.28
  437.52 1006.15  451.15 1019.79  474.66 1025.68  506.44 1030.63  533.78 1028.05
   555.1 1024.64   571.4 1021.37  586.08 1017.27  600.73  1015.2  669.36  999.83
#Mann= 3 , 0 , 0
       0     .12       0  280.75    .047       0  372.45     .12       0
Bank Sta=280.75,372.45
Exp/Cntr=0.3,0.1

Type RM Length L Ch R = 1 ,45555.62,409.77,409.77,414.55
XS GIS Cut Line= 2
  1347308.056438   782137.443174  1346732.535541   782028.068198
#Sta/Elev= 30
       0 1001.92   20.44  998.69    29.1   996.8   63.65  990.74    72.1  988.95
   87.62  987.53  120.45  981.64  145.29   980.8  160.64  978.82  168.36  978.64
  190.81  975.57  202.75  973.59  249.47   967.3  284.09  958.42  305.76  959.13
  328.64  958.13  351.92  959.13  361.44  968.45  365.61  971.74  379.28  981.32
  381.71  985.95  391.75  992.71  404.12 1000.01  412.57 1005.63  431.69 1012.37
  461.44 1021.33  489.48 1027.14  506.74 1028.28  524.97  1030.1  585.82 1037.96
#Mann= 3 , 0 , 0
       0     .12       0  249.47    .047       0  361.44     .12       0
Bank Sta=249.47,361.44
Exp/Cntr=0.3,0.1

Type RM Length L Ch R = 1 ,45145.86,615.32,615.32,945.47
XS GIS Cut Line= 2
   1347547.63967   781754.630629  1346886.181365   781645.255653
#Sta/Elev= 30
       0 1001.48   14.08  997.72   63.98     988   77.12  986.31  110.05  991.31
  148.47  991.68  174.35  995.61  199.32  993.52  215.46  993.87  233.12  995.67
  240.87  997.53  248.67  996.31  256.16  993.67  266.43   992.3  288.49  991.78
  309.12  989.57  352.24  981.42  393.72  971.14  418.83  963.58  428.86  957.74
  454.64  958.73  477.75  957.73  500.99  958.68  526.73  966.45  532.13  974.33
  581.19  993.42  605.08  996.63   617.9  996.83  639.97 1000.35  670.44  998.68
#Mann= 3 , 0 , 0
       0     .11       0  418.83    .047       0  526.73     .11       0
Bank Sta=418.83,526.73
Exp/Cntr=0.3,0.1

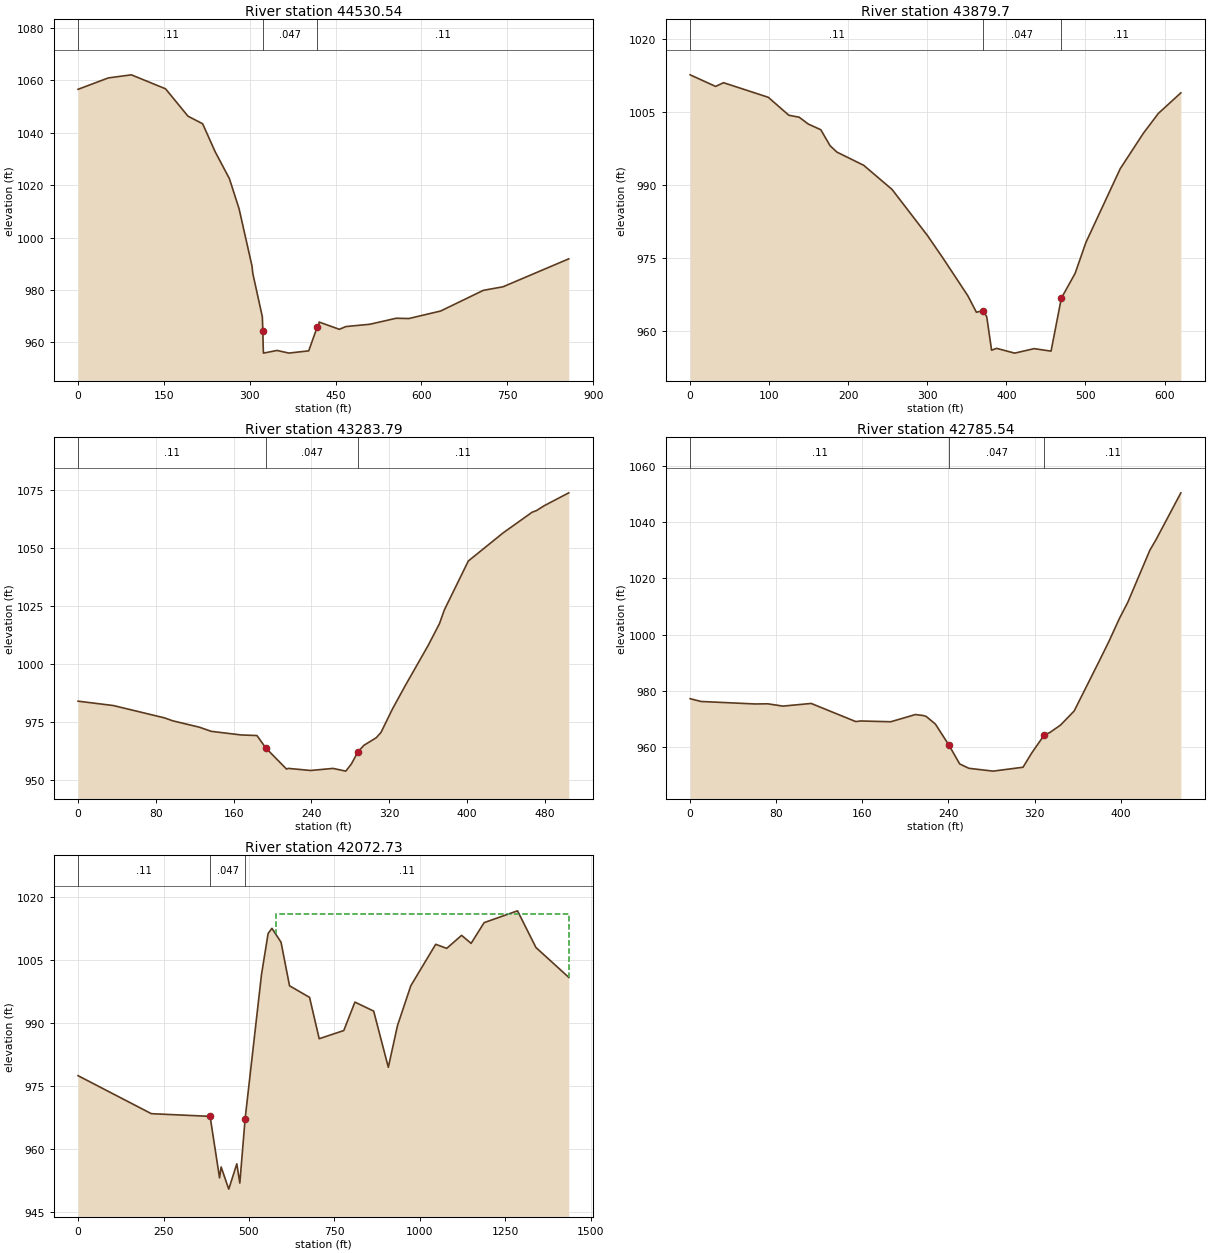
Type RM Length L Ch R = 1 ,44530.54,650.84,650.84,851.97
XS GIS Cut Line= 2
   1347000.26879   780739.111524  1346901.172213   781590.816101
#Sta/Elev= 30
       0 1056.59    52.9 1060.93   93.12 1062.11  152.88 1056.77  192.16 1046.31
  217.65 1043.44   239.6 1032.74  264.37 1022.52  281.37 1010.97   303.9  989.14
   305.3  986.33  321.96  969.78  322.88  964.36   323.4  958.87  323.89   955.9
  347.52  956.92  368.38  955.92  403.04  956.77  417.67  965.75  420.38  965.41
  421.15  967.76  456.53  964.99  468.08  966.04  509.89  966.92  555.89  969.21
  577.98   969.1   633.5  971.97  708.13  979.86  742.58  981.22  857.45  991.89
#Mann= 3 , 0 , 0
       0     .11       0  322.88    .047       0  417.67     .11       0
Bank Sta=322.88,417.67
Exp/Cntr=0.3,0.1

Type RM Length L Ch R = 1 ,43879.7 ,595.92,595.92,513.47
XS GIS Cut Line= 2
  1346364.647413   781329.293925  1346826.285557   781744.213989
#Sta/Elev= 30
       0 1012.65   32.17 1010.27   42.22 1011.03   98.84 1008.03  124.84 1004.34
  137.86 1003.94  149.44 1002.53  165.21 1001.37  176.98  998.08  185.63  996.77
  219.55  994.05   255.4  989.09  299.98  979.66  319.82  974.97  351.27  967.23
  362.06  963.85  370.23  964.19  375.12  962.95  381.27  956.05  387.65  956.43
  410.48  955.45   435.1  956.37  456.49  955.86  469.52  966.75  486.95  971.85
  500.62  978.22  543.97  993.35   573.3 1000.65  592.21 1004.72   620.7 1008.95
#Mann= 3 , 0 , 0
       0     .11       0  370.23    .047       0  469.52     .11       0
Bank Sta=370.23,469.52
Exp/Cntr=0.3,0.1

Type RM Length L Ch R = 1 ,43283.79,498.24,498.24,360
XS GIS Cut Line= 2
  1346134.403957   781769.658085  1346344.514677    782228.58903
#Sta/Elev= 30
       0  984.09   36.31   982.2   88.93  976.88   97.43  975.61   124.8  972.86
  136.97  971.08  167.88  969.51  183.98  969.27  193.18  963.87  214.41  954.81
  216.17   955.1  239.21   954.2  262.26  955.09  275.39  953.92  281.17  957.05
  287.69  962.12  293.97  965.04   306.7  968.33  311.53  970.57  323.62  980.93
  336.62  990.85  360.19 1008.19  371.77 1017.56  376.67 1023.38  401.42 1044.54
  437.41 1056.72  467.01 1065.56  471.53 1066.28  479.26 1068.33  504.74 1073.93
#Mann= 3 , 0 , 0
       0     .11       0  193.18    .047       0  287.69     .11       0
Bank Sta=193.18,287.69
Exp/Cntr=0.3,0.1

Type RM Length L Ch R = 1 ,42785.54,712.81,712.81,434.59
XS GIS Cut Line= 2
   1345821.60818   781809.849189  1345706.394612   782251.079398
#Sta/Elev= 30
       0  977.24   10.09  976.26   60.39  975.37   72.09  975.43   86.17  974.61
  112.46  975.56  153.94  969.11  158.46  969.33  186.44  969.05  209.28  971.61
  216.74  971.26  219.45  970.91  227.89  968.23  240.62  960.67  250.45  954.07
  259.06  952.51  281.49  951.51  309.34  952.89  317.38  957.94  329.19  964.42
  334.19  965.21  344.15  967.86  356.86  972.88  380.41  990.82  389.28   997.7
  398.95 1005.78   406.6 1011.42  427.22 1030.02  432.74 1033.62  456.02 1050.39
#Mann= 3 , 0 , 0
       0     .11       0  240.62    .047       0  329.19     .11       0
Bank Sta=240.62,329.19
Exp/Cntr=0.3,0.1

Type RM Length L Ch R = 1 ,42072.73,675.7,675.7,351.29
XS GIS Cut Line= 3
  1345795.035508   781593.172325  1345177.848052   781551.505637
  1344614.875379    782143.51767
#Sta/Elev= 30
       0  977.52  214.32  968.47  386.22  967.83  413.88  953.18  418.51  955.78
  440.79   950.5  464.41  956.53  473.17  951.94   488.7  967.26  536.62 1001.63
  555.97 1011.39  567.18 1012.61  593.77  1009.3  618.59  998.93  677.19  996.17
   705.4  986.32  777.31  988.27  809.88  995.04  864.78   992.9   907.6  979.52
  934.46  989.46  973.51  998.96 1046.19 1008.81 1078.48 1007.84 1121.95 1010.94
 1149.82 1009.03 1187.88 1013.97 1285.57 1016.78 1339.53 1008.04 1435.55 1000.93
#Mann= 3 , 0 , 0
       0     .11       0  386.22    .047       0   488.7     .11       0
#XS Ineff= 2 , 0
                          579.76         1016.07
Permanent Ineff=
       F       F
Bank Sta=386.22,488.7
Exp/Cntr=0.3,0.1