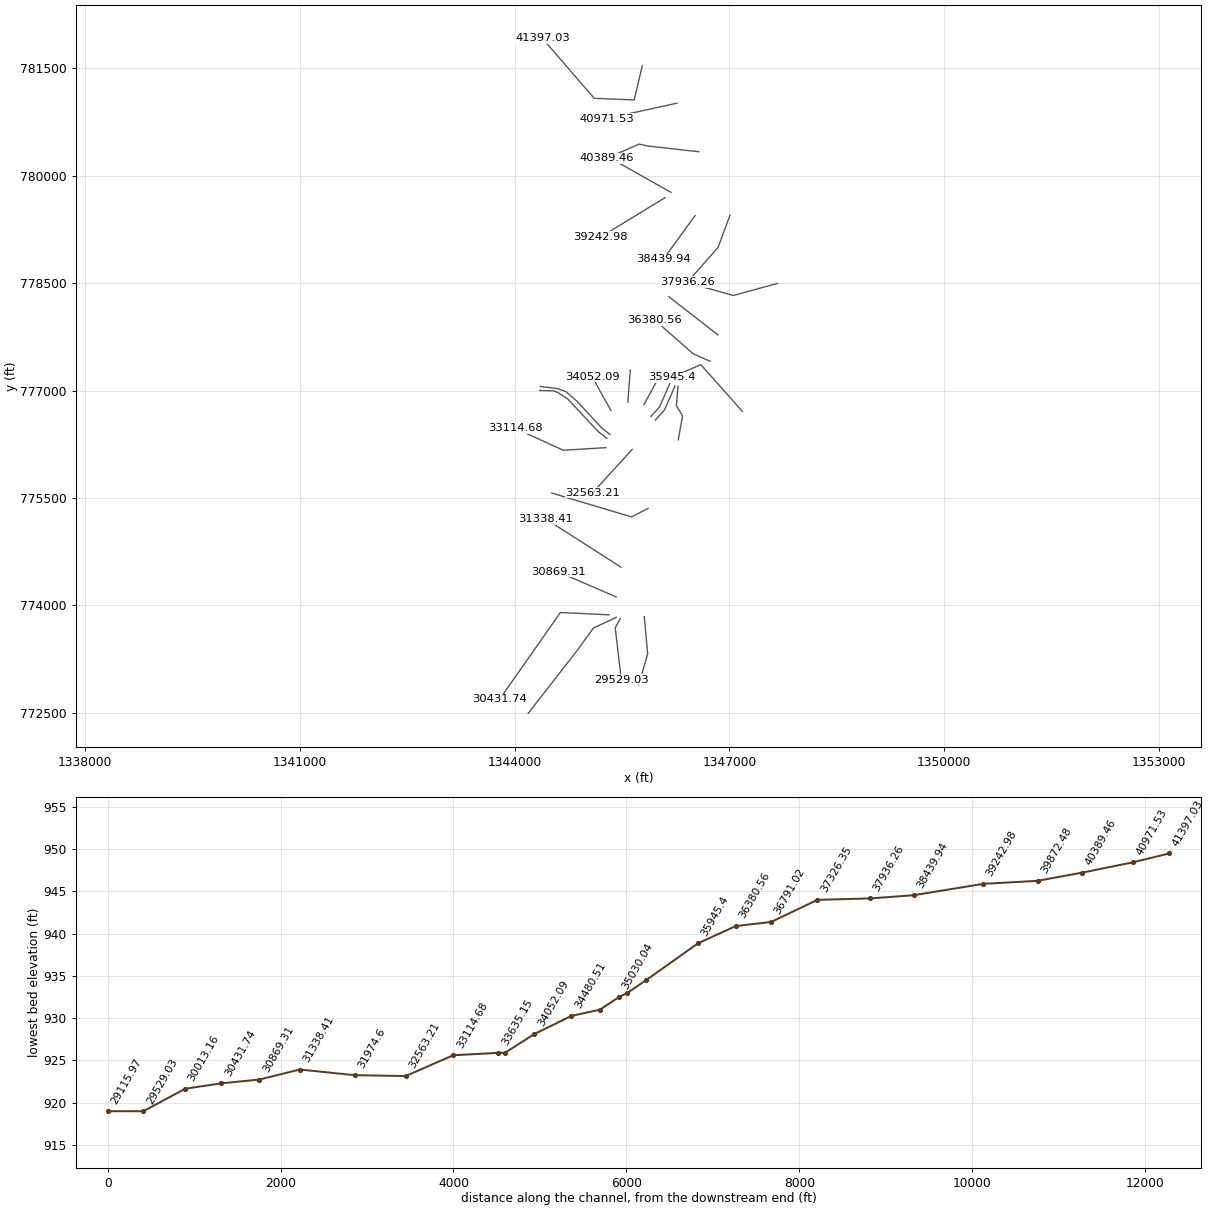
HEC-RAS study LLRiver.prj: LLRiver

--- LLRiver.g01 (geometry) --- (continued)

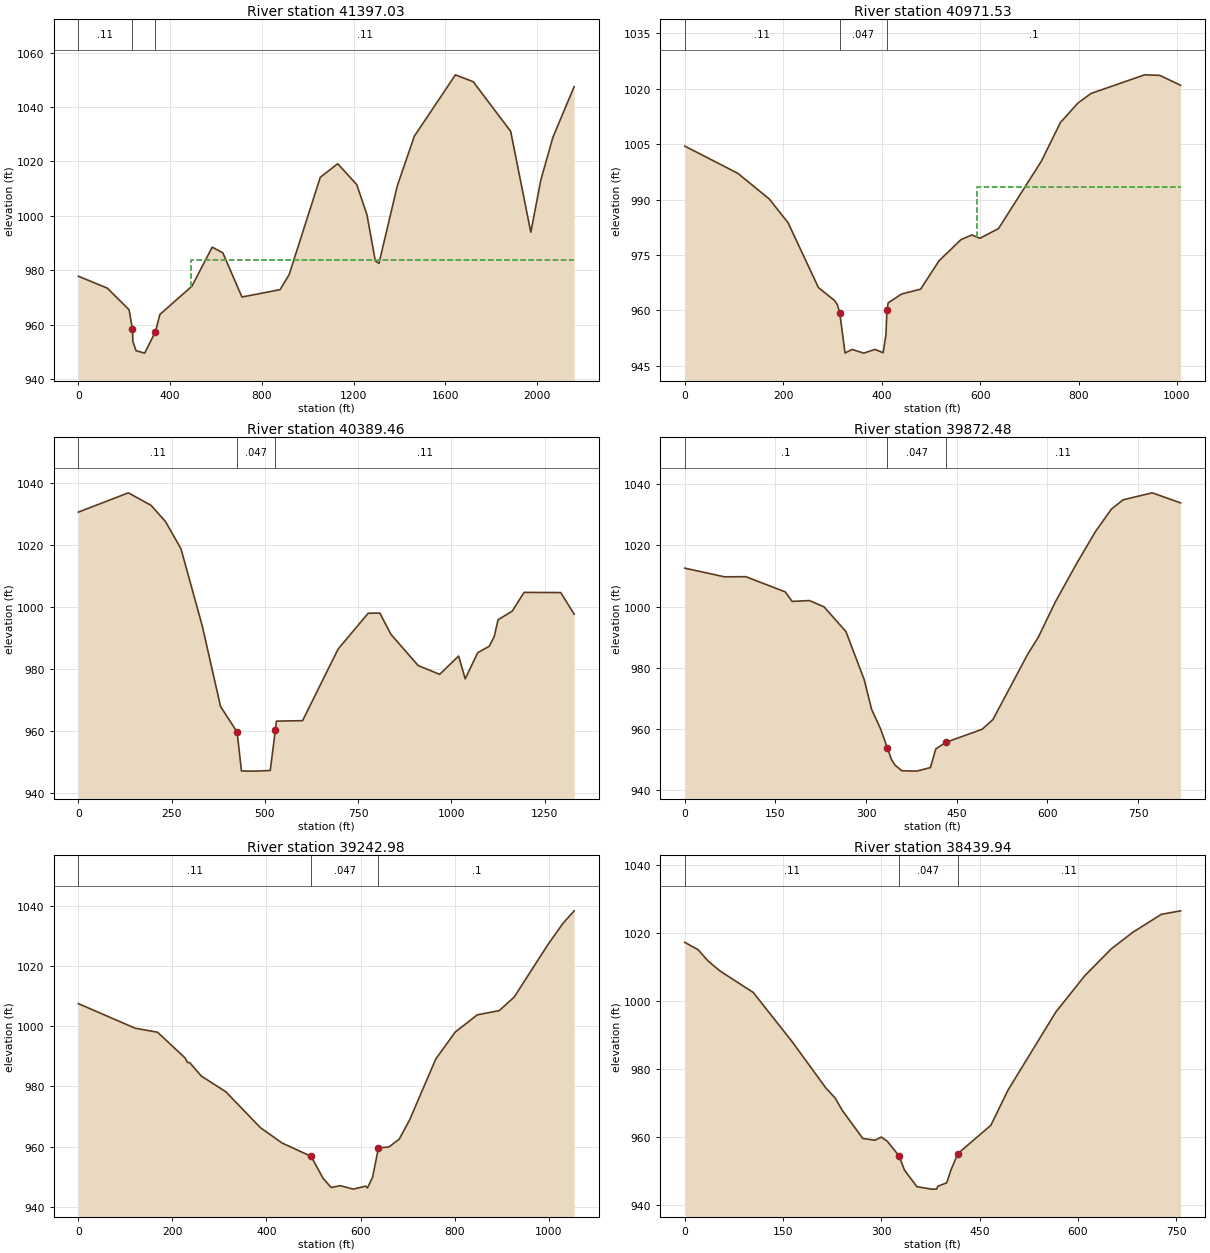
Type RM Length L Ch R = 1 ,41397.03,425.5,425.5,655.5
XS GIS Cut Line= 4
  1345784.618868   781541.088997  1345670.035572   781059.318245
  1345111.094516   781081.916901  1344388.402547   781919.740902
#Sta/Elev= 30
       0  977.78   126.3  973.39  221.15  965.43  235.86  958.32  237.87  953.73
  251.54  950.37  289.05  949.47  336.21  957.38  355.46  963.69  495.21  974.12
  583.43  988.46   629.6  986.41  713.17  970.11  879.31  972.83  918.66  978.33
 1054.61 1014.18 1130.59 1019.17 1213.54 1011.48 1258.03 1000.38  1294.4  983.42
 1310.37   982.5 1390.13 1011.01 1464.65 1029.32 1643.58 1051.88 1721.25 1049.34
 1884.36 1031.08 1972.23  993.96 2015.61  1013.1 2068.17 1028.84 2161.06 1047.53
#Mann= 3 , 0 , 0
       0     .11       0  235.86    .047       0  336.21     .11       0
#XS Ineff= 2 , 0
                          491.24          983.76
Permanent Ineff=
       F       F
Bank Sta=235.86,336.21
Exp/Cntr=0.3,0.1

Type RM Length L Ch R = 1 ,40971.53,582.06,582.06,649.41
XS GIS Cut Line= 2
  1346267.587573   781013.849701  1345283.509364   780798.161253
#Sta/Elev= 30
       0 1004.49  107.78  997.12   171.8  990.15  209.88  983.73  271.54  966.17
  304.48  962.64  310.34  961.44   315.1  959.15  325.52  948.44  340.04  949.41
  363.43  948.41   386.3  949.41  403.01  948.52  408.68   953.3   410.7  960.03
  413.25  962.03  440.47  964.42  479.12  965.74   516.6  973.43  561.21  979.16
  583.17  980.43   599.6  979.52   637.4  982.15   724.4 1000.38   763.2 1010.87
  798.57 1016.13   825.6 1018.77   934.3  1023.8  965.17 1023.65 1007.44 1020.97
#Mann= 3 , 0 , 0
       0     .11       0   315.1    .047       0   410.7      .1       0
#XS Ineff= 2 , 0
                          592.82          993.35
Permanent Ineff=
       F       F
Bank Sta=315.1,410.7
Exp/Cntr=0.3,0.1

Type RM Length L Ch R = 1 ,40389.46,516.98,516.98,599.66
XS GIS Cut Line= 4
  1346571.077237   780335.359844  1345857.535604   780416.088932
   1345740.34802    780442.13066  1345289.827188   780246.818148
#Sta/Elev= 30
       0  1030.7  134.08 1036.93  194.92  1032.9  233.67 1027.67  275.16  1018.9
  332.13  994.07  381.27  968.04  425.65   959.8  437.31  947.24  476.89   947.2
  514.43  947.41  528.23  960.44  530.86  963.32  601.19  963.47   696.2  986.52
  776.86   998.1  808.28  998.16  838.14  991.28  911.13  981.23  968.68  978.41
 1019.39  984.31 1037.13  976.95  1070.6  985.38 1101.61  987.47 1115.04  990.62
 1125.13  995.99 1163.06  998.78 1194.85 1004.83 1293.18 1004.77 1329.18  997.82
#Mann= 3 , 0 , 0
       0     .11       0  425.65    .047       0  528.23     .11       0
Bank Sta=425.65,528.23
Exp/Cntr=0.3,0.1

Type RM Length L Ch R = 1 ,39872.48,629.5,629.5,386.73
XS GIS Cut Line= 2
  1346184.008309   779768.249316   1345469.51474    780171.29738
#Sta/Elev= 30
       0 1012.56   65.53 1009.73  101.06 1009.76  166.14 1004.81  177.62 1001.69
  206.16 1001.97  230.26  999.93  266.63  991.82  296.71  976.19  309.16  966.38
  323.82  960.08  334.87  953.95  341.91  950.05  347.54  948.25  358.91  946.36
  383.49  946.23  406.32  947.38  415.24  953.47   432.2  955.66  491.99  959.91
  509.79  963.08  566.98  984.31  585.15  990.08  612.33 1001.25  648.16 1014.03
  679.27 1024.47  705.61 1031.81  725.08 1034.88  773.21 1037.17  820.33 1033.89
#Mann= 3 , 0 , 0
       0      .1       0  334.87    .047       0   432.2     .11       0
Bank Sta=334.87,432.2
Exp/Cntr=0.3,0.1

Type RM Length L Ch R = 1 ,39242.98,803.04,803.04,667.04
XS GIS Cut Line= 2
  1346102.327285    779694.73482  1345202.626164   779145.449059
#Sta/Elev= 30
       0 1007.55  120.65  999.38  168.36  998.04   226.9   989.5  232.31  987.97
  236.79  987.93  261.62  983.45  313.67  978.23  387.08  966.31  433.42  961.18
  494.79  956.78  520.59  949.41  537.47  946.42  556.95  947.02  584.44  945.87
  610.83  946.86  614.71  946.27  625.63  949.88  638.02  959.59  660.29  959.89
  682.06  962.45  704.26  968.87  759.87  989.12  801.48  998.13  848.22 1003.82
  894.78 1005.22  926.55 1009.71  998.71 1027.26 1030.69 1034.32 1054.12  1038.4
#Mann= 3 , 0 , 0
       0     .11       0  494.79    .047       0  638.02      .1       0
Bank Sta=494.79,638.02
Exp/Cntr=0.3,0.1

Type RM Length L Ch R = 1 ,38439.94,503.68,503.68,522.22
XS GIS Cut Line= 2
  1346521.598069   779444.734819  1346076.285557   778832.755683
#Sta/Elev= 30
       0 1017.14   20.36 1014.96   35.23 1011.72   53.16 1008.79  104.51 1002.39
  163.85  987.91  215.39  974.28  229.33  971.37  240.43   967.7  271.76  959.43
  290.44  958.91  299.67  959.85  309.11  958.63  326.83  954.36  335.42   950.1
  354.26  945.26  376.26  944.53  384.42  944.53  386.26  945.38  399.77  946.38
  406.22  950.14  416.84  954.98  467.18  963.31  493.29  973.64  566.53  996.69
  610.78 1007.36  650.76 1015.18  684.04 1020.12  727.57 1025.39  756.85 1026.41
#Mann= 3 , 0 , 0
       0     .11       0  326.83    .047       0  416.84     .11       0
Bank Sta=326.83,416.84
Exp/Cntr=0.3,0.1

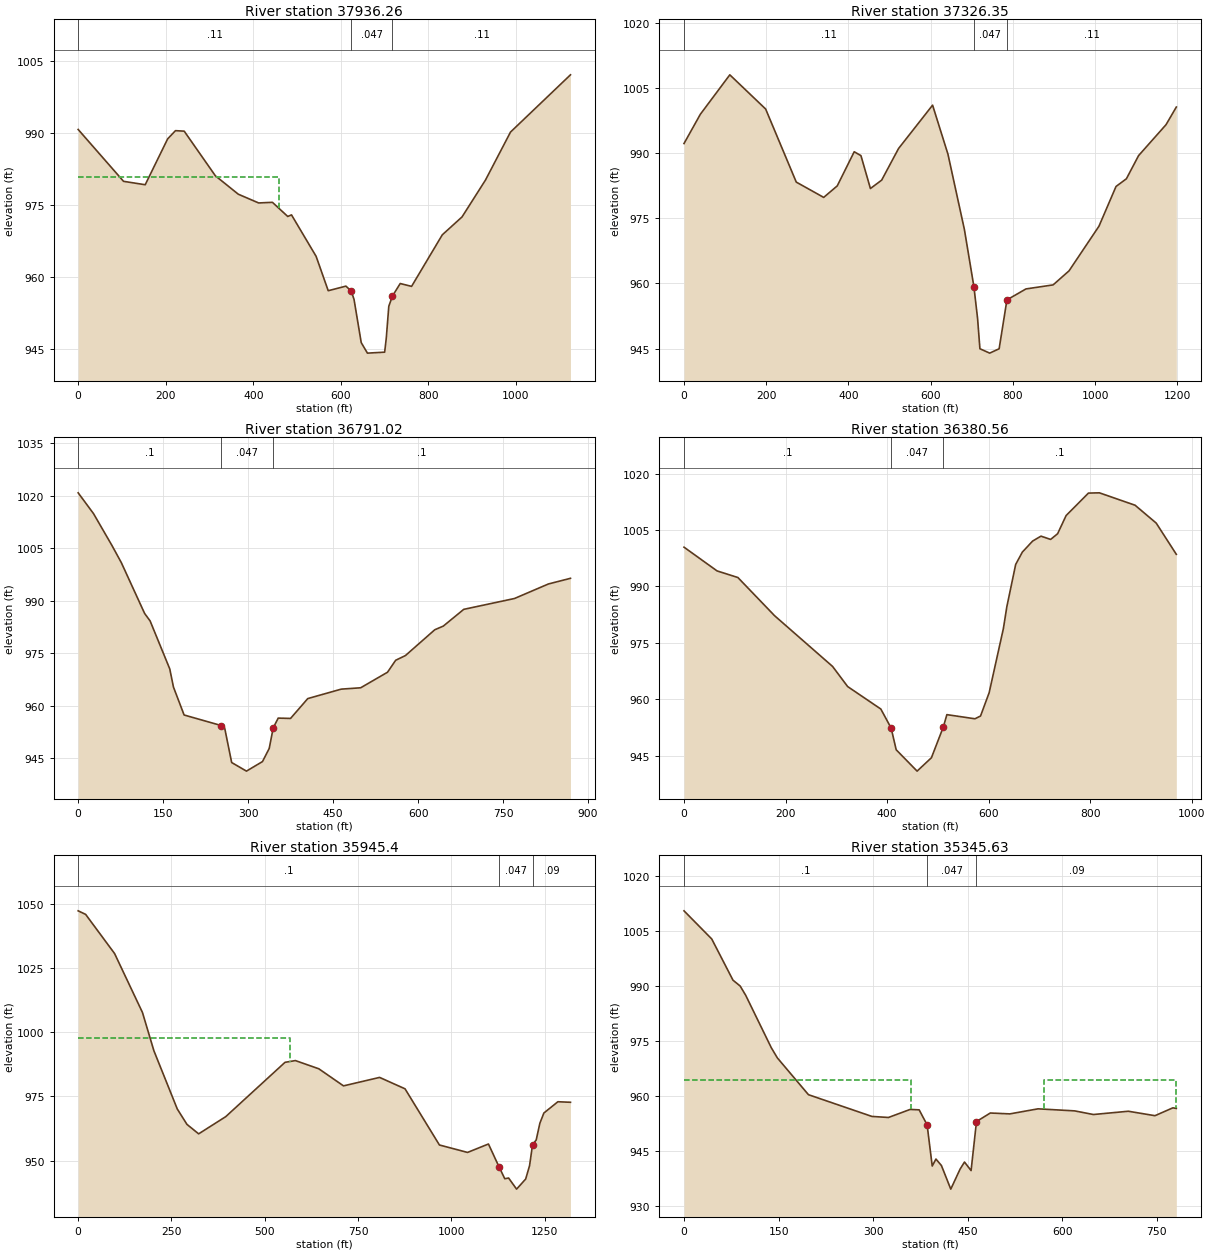
Type RM Length L Ch R = 1 ,37936.26,609.91,609.91,777.51
XS GIS Cut Line= 3
  1347007.963894   779448.484707  1346841.910517   778999.422307
  1346414.827253   778515.047394
#Sta/Elev= 30
       0  990.81  103.65  979.99  153.17  979.28  204.44  988.85  222.28  990.56
  242.22  990.46  313.41  981.15  365.88   977.3  412.29  975.48  443.74  975.61
  478.78  972.66  487.35  972.99  543.57  964.34  571.22  957.17  611.76  958.13
  624.03  957.05  630.18  955.35  646.61  946.34  660.77  944.15  700.12  944.35
  703.82  947.27  709.58  953.92  717.89  956.06  735.67  958.67  761.64  958.08
  831.77  968.83   876.9  972.57  930.44  980.26  987.61  990.27 1124.55 1002.21
#Mann= 3 , 0 , 0
       0     .11       0  624.03    .047       0  717.89     .11       0
#XS Ineff= 2 , 0
          458.32  980.98
Permanent Ineff=
       F       F
Bank Sta=624.03,717.89
Exp/Cntr=0.3,0.1

Type RM Length L Ch R = 1 ,37326.35,535.33,535.33,674.61
XS GIS Cut Line= 3
  1347672.639734   778496.818146   1347055.45215   778327.547362
  1346518.993909   778478.589026
#Sta/Elev= 30
       0   992.2   39.77  998.94   111.4 1008.01  198.56 1000.14  273.01  983.33
  339.73  979.81  372.69  982.46  413.91  990.31   430.3  989.42  453.35  981.85
   480.7  983.78   521.8  991.06  604.53 1001.03  641.93  989.74  681.89  972.43
  704.99  959.28  713.96  951.96  719.64  944.99   743.4  943.98  766.36  944.98
  785.34  956.23  831.64  958.75  897.67  959.68  936.38  962.91 1009.15  973.18
 1050.64  982.32 1075.91   984.1 1105.49  989.42 1172.26  996.54 1197.29  1000.6
#Mann= 3 , 0 , 0
       0     .11       0  704.99    .047       0  785.34     .11       0
Bank Sta=704.99,785.34
Exp/Cntr=0.3,0.1

Type RM Length L Ch R = 1 ,36791.02,410.46,410.46,422.31
XS GIS Cut Line= 2
  1346839.306357   777778.068194  1346153.031285   778311.074786
#Sta/Elev= 30
       0  1020.9   27.12 1014.96    59.5  1005.9   76.23 1000.94  117.32  986.43
  127.02  984.29  161.71  970.57  168.19  965.41  187.02  957.41  252.67  954.39
  258.58  953.71  270.95  943.83  297.06  941.37  325.35   944.1  337.25  947.86
  344.29  953.74   353.1  956.52  374.89  956.43  405.26   962.1  464.32   964.8
   498.7  965.19  546.01  969.63  560.44  973.05  577.69   974.4  629.38  981.76
  644.53  982.82   680.6   987.6  770.13   990.7  830.14  994.86  868.95  996.47
#Mann= 3 , 0 , 0
       0      .1       0  252.67    .047       0  344.29      .1       0
Bank Sta=252.67,344.29
Exp/Cntr=0.3,0.1

Type RM Length L Ch R = 1 ,36380.56,435.16,435.16,207.25
XS GIS Cut Line= 3
  1346729.209589   777409.399649  1346492.638837   777514.444513
  1345958.914933   777984.183906
#Sta/Elev= 30
       0 1000.43   65.09  994.12  106.15  992.36  178.41  982.21  292.74  968.71
  322.33  963.37  387.72  957.39  408.01  952.34  417.99  946.56  459.19  940.88
  487.42  944.44  511.07  952.71  517.84   955.9  573.13   954.8  584.16  955.54
  601.16  961.75  629.17   978.8  635.96  984.59  653.38  995.84  666.52  999.12
  686.83 1002.06  703.21 1003.36  722.23 1002.49  736.01 1004.01  752.69 1008.83
  796.73 1014.81  818.34 1014.88  888.62 1011.58  930.23 1006.83  969.84  998.53
#Mann= 3 , 0 , 0
       0      .1       0  408.01    .047       0  511.07      .1       0
Bank Sta=408.01,511.07
Exp/Cntr=0.3,0.1

Type RM Length L Ch R = 1 ,35945.4 ,599.77,599.77,994.65
XS GIS Cut Line= 3
  1347183.200502   776707.048929  1346601.493109   777361.575393
  1346194.792821   777185.380833
#Sta/Elev= 30
       0 1047.29   20.08  1045.9   97.58 1030.65  172.23  1007.7  202.85  992.79
  265.51  970.09  291.46  964.08  322.81  960.39  395.27  967.08   554.2  988.26
  582.03  988.94  644.82  985.73  710.87  979.08  807.51  982.38  875.66  977.94
  967.81  956.05 1043.11  953.15 1099.18  956.43  1127.2  947.64 1142.87  942.91
 1153.21  943.17 1174.54  938.85 1198.91  942.79 1209.33  948.02 1217.32   956.2
 1227.05  957.99 1236.97  964.55 1247.66  968.51 1285.19   972.9 1318.89  972.69
#Mann= 3 , 0 , 0
       0      .1       0  1127.2    .047       0 1217.32     .09       0
#XS Ineff= 2 , 0
           566.7  997.62
Permanent Ineff=
       F       F
Bank Sta=1127.2,1217.32
Exp/Cntr=0.3,0.1

Type RM Length L Ch R = 1 ,35345.63,223.02,223.02,364.49
XS GIS Cut Line= 4
  1346285.900789    776311.80976  1346345.774709   776646.159841
  1346259.696245   776788.871393  1346283.133685   777062.308961
#Sta/Elev= 30
       0 1010.44   43.98 1002.76   77.66  991.52   89.06  989.92   97.93  987.36
  138.44  973.08  148.08   970.3  197.35  960.27  297.95  954.34  324.26  954.05
  358.65  956.25  372.94  956.13  385.55  952.03  393.65   940.8  399.56  942.71
  408.27  940.93  423.07   934.5  437.87  939.97  444.83  941.89  455.28  939.56
  463.84  952.94  485.74  955.27  516.69  955.03  561.48  956.41  619.58  955.85
  649.16  954.86  704.64  955.75   746.9  954.54   775.3  956.68  780.77  956.52
#Mann= 3 , 0 , 0
       0      .1       0  385.55    .047       0  463.84     .09       0
#XS Ineff= 2 , 0
          360.15   964.2  571.22           964.2
Permanent Ineff=
       F       F
Bank Sta=385.55,463.84
Exp/Cntr=0.5,0.3

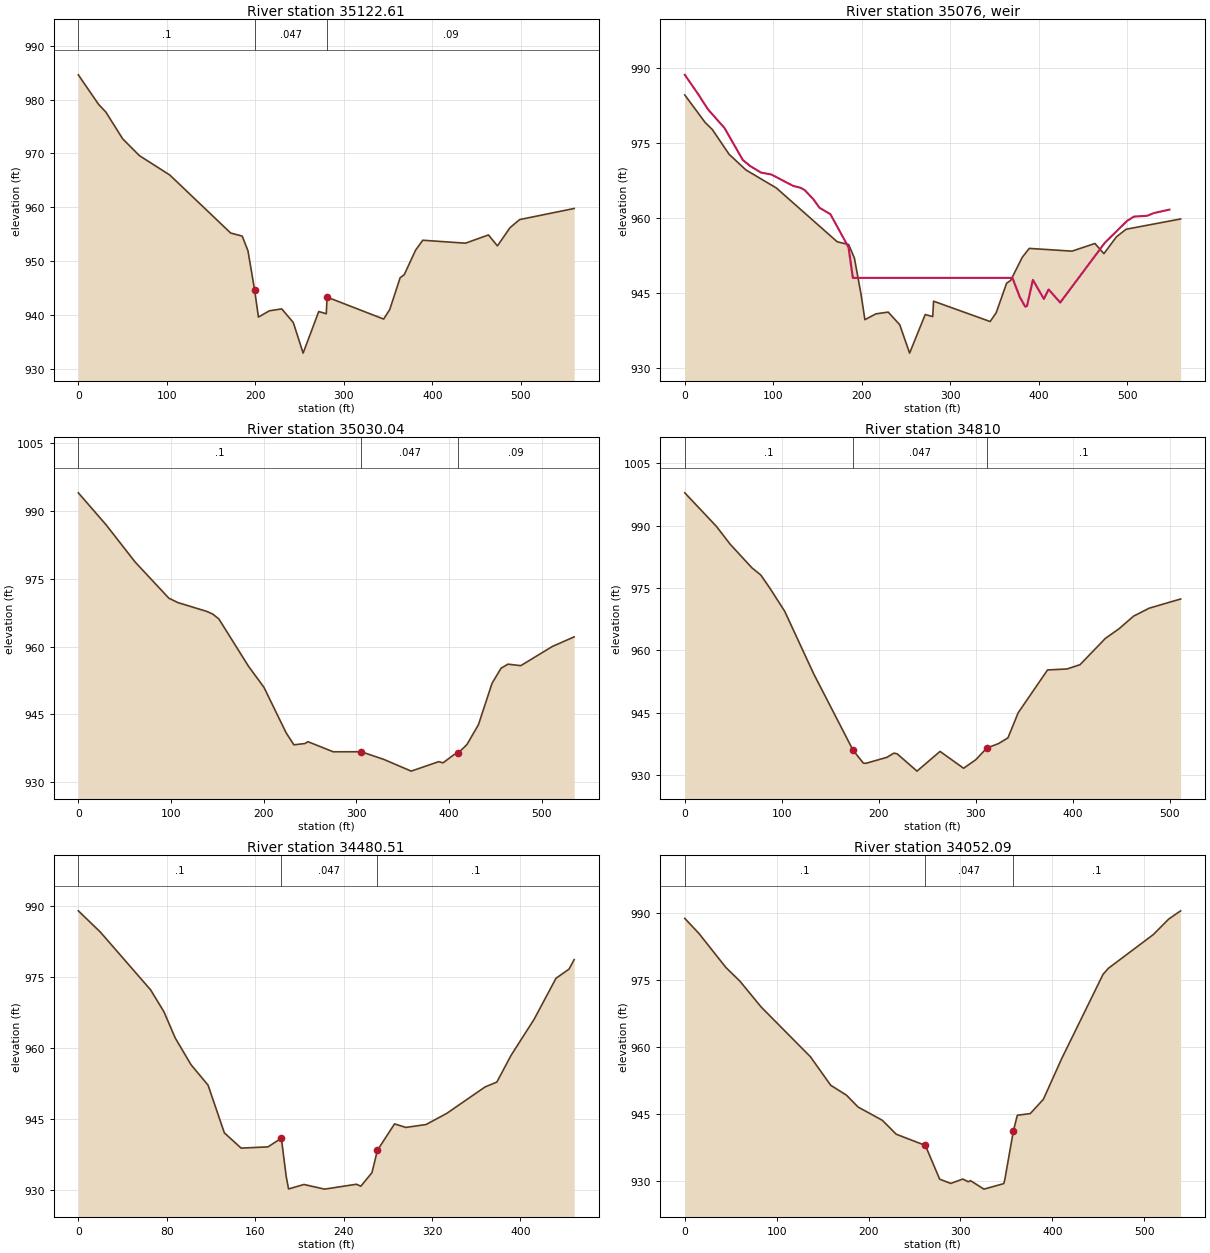
Type RM Length L Ch R = 1 ,35122.61,92.56,92.56,81.85
XS GIS Cut Line= 3
  1345963.992693   776584.397281  1346094.547957   776730.846305
  1346241.016309   777064.034017
#Sta/Elev= 30
       0  984.59   22.94   979.1   31.06  977.69   50.09  972.72   68.99   969.6
   103.4  965.99  172.14  955.23  185.13  954.67  191.66  951.93  199.13  944.69
  203.47  939.64  215.95  940.81  229.82  941.16  242.87  938.62  253.97  932.95
   271.6  940.67  280.09  940.26  281.06  943.34  344.95  939.27  351.78  941.03
  363.55  946.93  368.21  947.51  381.04  952.06  389.09   953.9  437.39  953.35
  463.34  954.88  473.47  952.85  487.65  956.22  498.56  957.73  560.15  959.79
#Mann= 3 , 0 , 0
       0      .1       0  199.13    .047       0  281.06     .09       0
Bank Sta=199.13,281.06
Exp/Cntr=0.5,0.3

Type RM Length L Ch R = 5 ,35076   ,,,
BEGIN DESCRIPTION:
DAM: 37003-0091
END DESCRIPTION:
IW Pilot Flow=0
#Inline Weir SE= 30
       0  988.62    15.1  984.76   25.96  981.76   44.93  977.96   65.41  971.62
   73.39  970.43   85.87  969.08   97.96  968.67  122.25  966.41  130.54  966.04
  135.35  965.58  145.04  963.78  152.29  962.01  164.47  960.75  184.97  954.12
  189.86     948  370.13     948   378.5  944.15  384.58  942.24  386.58  942.37
  393.22   947.6  405.66  943.79  411.01  945.69  424.11  943.07  474.55  955.03
  499.63   959.4  507.44  960.26  522.27  960.42  530.31  960.99  547.49  961.66
IW Dist,WD,Coef,Skew,MaxSub,Min_El,Is_Ogee,SpillHt,DesHd
82,10,2.6,0,0.95,, 0 ,,,0,0,

Type RM Length L Ch R = 1 ,35030.04,220.04,220.04,200.1
XS GIS Cut Line= 3
  1345904.276597   776637.632609  1346026.406901   776774.630881
  1346167.780341   777096.228321
#Sta/Elev= 30
       0  993.97   30.04  986.88   61.41  978.65   97.62   970.7  107.32  969.73
  138.44  967.78  144.93  967.19  151.55  966.12  183.53  955.67  200.18  951.02
  224.14  940.96  232.54   938.3  244.55  938.59   247.7  938.99  275.01  936.76
  305.16  936.77  329.27   935.1  359.09  932.49  388.71  934.58  393.41  934.32
  405.18  936.13  409.77  936.47  419.29   938.4  431.61  942.76  446.27   951.9
  455.97  955.22   463.4  956.12  477.24  955.79  511.25  960.02  534.83  962.15
#Mann= 3 , 0 , 0
       0      .1       0  305.16    .047       0  409.77     .09       0
Bank Sta=305.16,409.77
Exp/Cntr=0.5,0.3

Type RM Length L Ch R = 1 ,34810   ,329.49,329.49,244.38
XS GIS Cut Line= 2
   1345806.08626   776802.589281  1346051.009269   777251.429857
#Sta/Elev= 30
       0  997.89   32.75  989.79   46.86  985.52   69.25  979.86   78.41  978.13
   87.64  975.01  102.99  969.44  132.97  954.37  173.62  935.99  184.12  932.94
  186.66  932.87  208.48  934.32  215.72  935.33  219.03  935.16  239.46     931
  263.21  935.74  287.53  931.69   300.1  933.75  311.43  936.54   323.6  937.63
  333.25     939  343.76  945.01  374.07  955.32  394.13  955.55  407.62  956.59
  433.69   962.9  447.77  965.21  462.74  968.24  478.99  970.17  511.32  972.37
#Mann= 3 , 0 , 0
       0      .1       0  173.62    .047       0  311.43      .1       0
Bank Sta=173.62,311.43
Exp/Cntr=0.3,0.1

Type RM Length L Ch R = 1 ,34480.51,428.42,428.42,310.7
XS GIS Cut Line= 2
  1345581.371764   776838.574305  1345616.527988   777285.839969
#Sta/Elev= 30
       0  988.99   19.94  984.51   65.42  972.31   77.51  967.68   87.58  962.21
  101.88  956.55  117.41   952.2  132.12  942.15  147.33  938.92  171.63  939.19
  183.71  941.01  188.11  932.93  190.22  930.31  204.18  931.25  222.82  930.27
  251.65   931.3  255.59  930.88  265.71  933.75  270.64  938.47  286.12  944.03
  296.41  943.29  314.64   943.9  333.36  946.25  367.98  951.82  378.71  952.86
  391.64  958.53  412.49  966.13  432.22  974.76     444  976.69  448.65  978.69
#Mann= 3 , 0 , 0
       0      .1       0  183.71    .047       0  270.64      .1       0
Bank Sta=183.71,270.64
Exp/Cntr=0.3,0.1

Type RM Length L Ch R = 1 ,34052.09,341.59,341.59,301.8
XS GIS Cut Line= 2
  1345345.125108   776721.305569  1345082.918004   777192.985185
#Sta/Elev= 30
       0   988.9   15.38  985.52   44.87  977.85   59.88  974.84   83.15     969
  136.82  957.82  158.84  951.43  175.94  949.22  188.62  946.55  215.05  943.57
   230.1  940.45  261.83  937.93  277.43  930.35   289.5   929.4  302.55  930.38
  308.64  929.77  310.93  930.03  325.58  928.12  347.19  929.36  348.41  930.38
  357.56   941.1  361.92   944.7  376.08  945.09  390.28  948.29  410.23  957.43
  455.26  976.35  461.06   977.7     510  985.28   526.7  988.75  539.66   990.6
#Mann= 3 , 0 , 0
       0      .1       0  261.83    .047       0  357.56      .1       0
Bank Sta=261.83,357.56
Exp/Cntr=0.5,0.3

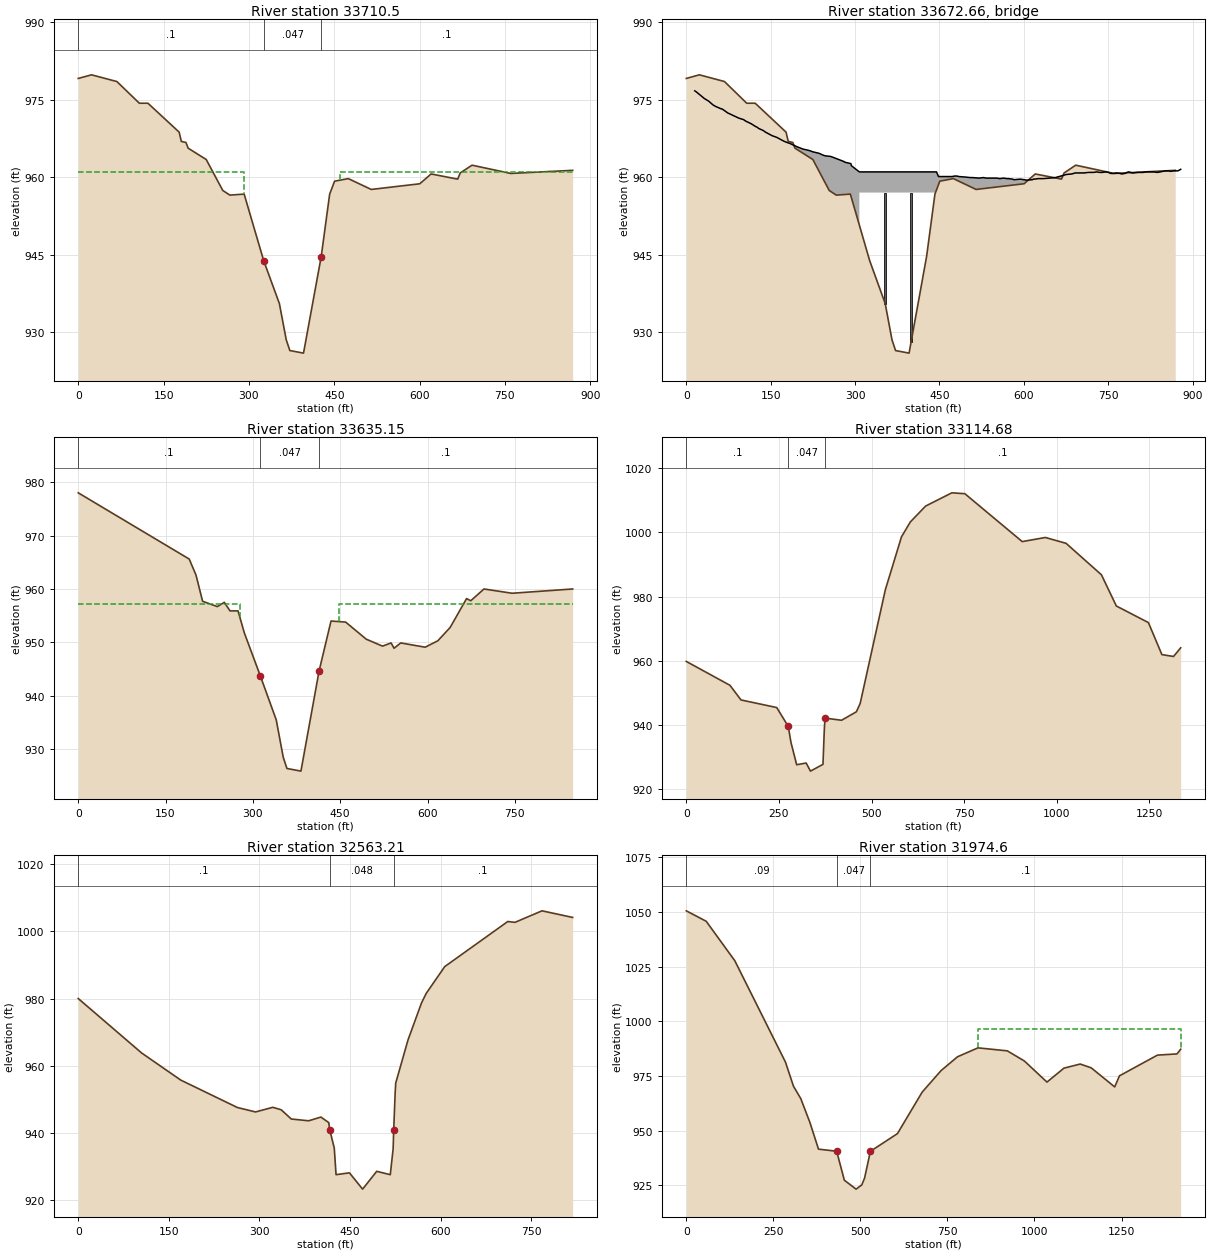
Type RM Length L Ch R = 1 ,33710.5 ,75.35,75.35,109.57
BEGIN DESCRIPTION:
Upstream xs of Bridge 37003-0060
END DESCRIPTION:
XS GIS Cut Line= 6
    1345331.9941   776386.498528  1345214.081524   776479.530337
   1344876.48626   776845.635809  1344717.830899   776983.996129
  1344606.934515   777025.152225  1344357.774579   777056.889057
#Sta/Elev= 30
       0   979.1  23.335   979.8  67.882   978.5  107.41   974.3 122.471   974.3
 177.342   968.7 181.231   966.9 189.292   966.7 193.111   965.6 224.931   963.4
 254.063   957.4 266.579   956.5 291.611   956.7 325.976   943.8 353.553   935.5
 365.574   928.5 371.938   926.4  395.98   925.9 427.092   944.6 441.942   956.7
 450.568   959.2 474.681   959.7 515.057   957.6 600.334   958.7 620.274   960.6
 666.943   959.6 671.539   960.8 692.187   962.3  760.21   960.7 869.105   961.3
#Mann= 3 , 0 , 0
       0      .1       0 325.976    .047       0 427.092      .1       0
#XS Ineff= 2 , 0
       0 291.469   960.9 460.892       0   960.9
Permanent Ineff=
       F       F
Bank Sta=325.976,427.092
Skew Angle= 45
Exp/Cntr=0.5,0.3

Type RM Length L Ch R = 3 ,33672.66,,,
BEGIN DESCRIPTION:
Bridge : 37003-0060 - SR-1131 / Alspaugh Dam Rd
END DESCRIPTION:
Bridge Culvert--1,0,-1,-1, 0
Deck Dist Width WeirC Skew NumUp NumDn MinLoCord MaxHiCord MaxSubmerge Is_Ogee
22.8,30,2.6,45, 133, 133, , , 0.95, 0, 0,0,,
  15.061  17.748  32.244   39.81  47.164  51.619  62.296  63.427  67.529  73.893
  76.085  83.792  89.308  93.621 102.389 103.308 106.207 113.915 115.824 122.895
 125.158 128.906 136.967 140.714 152.735 160.584 172.463 176.635 184.272 188.444
 196.081  207.96 212.486  219.91 224.506 231.931 235.962 244.235 247.699 256.326
 259.013 268.347 270.539 280.439 281.075  292.53 293.096 293.449 307.591 307.591
  444.77  444.77 448.235 460.327 468.882 472.347 477.014 481.186 484.368  496.46
 504.591 508.551 520.643 528.209 532.946 540.088 545.109 551.755 557.059 563.423
 564.342 569.362 572.544 579.969  582.09  583.08 593.758 605.425 615.678 616.809
 617.375 619.072 625.789  633.78 634.345 635.053 645.023   655.7 656.124 665.741
 675.499 685.399 691.268 692.965  695.44 702.652 706.117 707.319 714.673 721.956
 722.875 723.936 729.734 734.543 736.805 738.997 745.644 750.382 754.483 759.574
 763.817 771.241 773.221 779.727 783.121 786.515 792.172 794.081 802.637 807.375
 812.112  816.92 821.163 830.709 837.497  850.72 851.215 857.508 860.973 864.579
 869.671 873.843 878.722
   976.7   976.5   975.2   974.7     974   973.7   973.2   973.2   972.9   972.4
   972.3   971.9   971.6   971.4   971.1     971   970.8   970.4   970.3   969.8
   969.7   969.4     969   968.7     968   967.7     967   966.8   966.5   966.3
   965.9   965.4   965.3   965.1   964.9   964.7   964.6   964.2   964.1     964
   963.9   963.5   963.4     963   962.9   962.6   962.3   962.2     961     961
     961     961   960.1   960.1   960.1   960.1   960.2   960.2   960.1     960
   959.9   959.9   959.8   959.9   959.8   959.8   959.8   959.8   959.7   959.8
   959.8   959.7   959.7   959.6   959.5   959.5   959.6   959.4   959.5   959.6
   959.6   959.6   959.7   959.7   959.7   959.7   959.8   959.9   959.9   960.2
   960.5   960.6   960.8   960.8   960.8   960.8   960.8   960.8   960.9   960.9
   960.9   960.9     961   960.9   960.9   960.9     961   960.9   960.7   960.7
   960.8   960.7   960.6   960.7   960.9     961   960.8   960.8   960.9   960.9
   960.9     961     961     961   960.9   961.2   961.2   961.2   961.1   961.2
   961.2   961.2   961.5
                                                                                
                                                                                
                                                                                
                                                                                
                                                                             957
     957
                                                                                
                                                                                
                                                                                
                                                                                
                                                                                
                                                                                
                                                                                
                        
    2.97   5.657  20.223  27.719  35.143  39.527  50.275  51.336  55.437  61.801
  64.064  71.771  77.287  81.529  90.298  91.287  94.187 101.823 103.803 110.874
 113.137 116.814 124.946 128.693 140.644 148.563 160.372 164.544  172.18 176.423
  184.06 195.939 200.394 207.819 212.415 219.839 223.941 232.143 235.608 244.235
 246.992 256.326 258.448 268.418 268.983 280.439 281.075 281.358 294.156 294.156
 431.335 431.335 436.214 448.235 456.862 460.327 464.923 469.095 472.277 484.439
   492.5  496.53 508.622 516.117 520.855 527.997 533.017 539.664 545.038 551.402
  552.25 557.342 560.453 567.948 569.999 571.059 581.666 593.333 603.586 604.788
 605.354  606.98 613.769 621.688 622.325 622.961 632.931 643.609 644.104  653.72
 663.408 673.378 679.247 680.873 683.419  690.56 694.025 695.227 702.581 709.865
 710.784 711.844 717.643 722.451 724.784 726.906 733.623  738.29 742.462 747.553
 751.796 759.221  761.13 767.635 771.029 774.423  780.08 781.989 790.545 795.354
 800.091 804.829 809.142 818.688 825.476 838.629 839.194 845.488 848.882 852.559
  857.65 861.751 866.701
   976.7   976.5   975.2   974.7     974   973.7   973.2   973.2   972.9   972.4
   972.3   971.9   971.6   971.4   971.1     971   970.8   970.4   970.3   969.8
   969.7   969.4     969   968.7     968   967.7     967   966.8   966.5   966.3
   965.9   965.4   965.3   965.1   964.9   964.7   964.6   964.2   964.1     964
   963.9   963.5   963.4     963   962.9   962.6   962.3   962.2     961     961
     961     961   960.1   960.1   960.1   960.1   960.2   960.2   960.1     960
   959.9   959.9   959.8   959.9   959.8   959.8   959.8   959.8   959.7   959.8
   959.8   959.7   959.7   959.6   959.5   959.5   959.6   959.4   959.5   959.6
   959.6   959.6   959.7   959.7   959.7   959.7   959.8   959.9   959.9   960.2
   960.5   960.6   960.8   960.8   960.8   960.8   960.8   960.8   960.9   960.9
   960.9   960.9     961   960.9   960.9   960.9     961   960.9   960.7   960.7
   960.8   960.7   960.6   960.7   960.9     961   960.8   960.8   960.9   960.9
   960.9     961     961     961   960.9   961.2   961.2   961.2   961.1   961.2
   961.2   961.2   961.5
                                                                                
                                                                                
                                                                                
                                                                                
                                                                             957
     957
                                                                                
                                                                                
                                                                                
                                                                                
                                                                                
                                                                                
                                                                                
                        
Pier Skew, UpSta & Num, DnSta & Num=  ,353.553, 2 ,340.118, 2 , 0 , 0 , 0 ,,
       3       3
   934.5   957.5
       3       3
   934.5   957.5
Pier Skew, UpSta & Num, DnSta & Num=  ,399.515, 2 ,386.08, 2 , 0 , 0 , 0 ,,
       3       3
   927.5   957.5
       3       3
   927.5   957.5
BR Coef=-1 , 1 , 0 ,, 0 ,,,0.8,0,1.2,0,
WSPro=,,,, 1 ,,,, 0 ,,,, 0 ,,,,-1 ,-1 ,-1 , 0 , 0 , 0 , 0 , 0
BC Design=,, 0 ,, 0 ,,,,,,

Type RM Length L Ch R = 1 ,33635.15,520.46,520.46,299.71
BEGIN DESCRIPTION:
Down stream xs of Bridge 37003-0060
END DESCRIPTION:
XS GIS Cut Line= 6
  1345288.635252   776331.543776  1345167.045748   776427.476832
  1344741.708019   776882.496481  1344605.797107   776971.693537
  1344546.651251   776995.579361  1344349.762931   777000.807777
#Sta/Elev= 30
       0     978 190.636   965.6 202.303   962.6 213.617   957.7 239.002   956.7
 250.952   957.5  260.64   955.9 274.499   955.9 285.247   951.8 312.541   943.8
 340.118   935.5 352.139   928.5 358.503   926.4 382.545   925.9 413.657   944.6
 434.234     954 459.407   953.8 494.763   950.6 522.764   949.3 537.401   949.9
 542.563   948.9 554.018   949.9  595.95   949.1 617.728   950.3 638.942   952.8
 667.085   958.2 674.368   957.8 696.995     960 745.361   959.2 849.377     960
#Mann= 3 , 0 , 0
       0      .1       0 312.541    .047       0 413.657      .1       0
#XS Ineff= 2 , 0
       0 278.247   957.2 447.245       0   957.2
Permanent Ineff=
       F       F
Bank Sta=312.541,413.657
Skew Angle= 45
Exp/Cntr=0.5,0.3

Type RM Length L Ch R = 1 ,33114.68,551.48,551.48,392.7
XS GIS Cut Line= 3
   1345274.59954    776202.16624  1344680.108531     776165.7688
  1344007.934451   776472.041825
#Sta/Elev= 30
       0  959.79  117.75  952.36  147.69  947.79  244.12  945.42  275.24  939.53
  282.53  934.56  297.91  927.61  323.56  928.14  335.13  925.62  368.87  927.73
  372.42  938.36  374.38  942.15  419.03  941.46  459.03   944.1  469.32  946.71
  537.26  982.14  580.73  998.58  604.66 1003.23  645.83 1008.17  716.62  1012.3
  751.75 1012.03   906.6  997.11  968.97  998.39 1025.02  996.57 1120.38  986.77
 1160.66  977.05 1247.15  971.88 1283.54  961.91 1314.93  961.33 1334.27  964.03
#Mann= 3 , 0 , 0
       0      .1       0  275.24    .047       0  374.38      .1       0
Bank Sta=275.24,374.38
Exp/Cntr=0.3,0.1

Type RM Length L Ch R = 1 ,32563.21,588.61,588.61,815.56
XS GIS Cut Line= 2
   1345642.22386    776177.01424  1345090.140532   775572.847584
#Sta/Elev= 30
       0     980   104.8  963.78  169.67  955.68  263.41   947.5  293.47  946.18
  322.09  947.56  335.86  946.83  352.71  944.07   381.4  943.54  401.66  944.65
  414.66     943  416.41   940.8  423.78  935.39  426.74  927.47  448.89  928.02
  470.69  923.16  494.05  928.47  516.49  927.47  521.22  935.18  522.14  940.72
  524.53  951.67  525.51  954.79  545.82  967.63  568.24  978.71  576.05  981.55
  606.62  989.52     711 1002.97  723.03 1002.73  767.66 1006.16  818.42 1004.19
#Mann= 3 , 0 , 0
       0      .1       0  416.41    .048       0  522.14      .1       0
Bank Sta=416.41,522.14
Exp/Cntr=0.3,0.1

Type RM Length L Ch R = 1 ,31974.6 ,636.19,636.19,693.95
XS GIS Cut Line= 3
    1345863.0245   775352.893151  1345632.802036   775234.575199
  1344520.364275   775567.233504
#Sta/Elev= 30
       0 1050.57   57.22 1045.79  139.38 1027.74  284.93  981.34  307.91  970.32
  328.83  964.67  355.02  953.78  379.73  941.55  431.91  940.59  453.96  927.34
  487.65  923.26  503.99  925.18   512.1  928.32  528.73  940.56  606.45  948.65
  677.55  967.65  731.82  977.49  778.96   983.8  837.79  987.89  922.09  986.51
  971.16  981.86 1035.92  972.22 1084.71  978.61 1131.43  980.48 1162.93  978.75
 1230.43  970.02 1244.08  975.08 1353.19  984.56 1409.25  985.11 1419.96  987.26
#Mann= 3 , 0 , 0
       0     .09       0  431.91    .047       0  528.73      .1       0
#XS Ineff= 2 , 0
                          837.43          996.61
Permanent Ineff=
       F       F
Bank Sta=431.91,528.73
Exp/Cntr=0.3,0.1

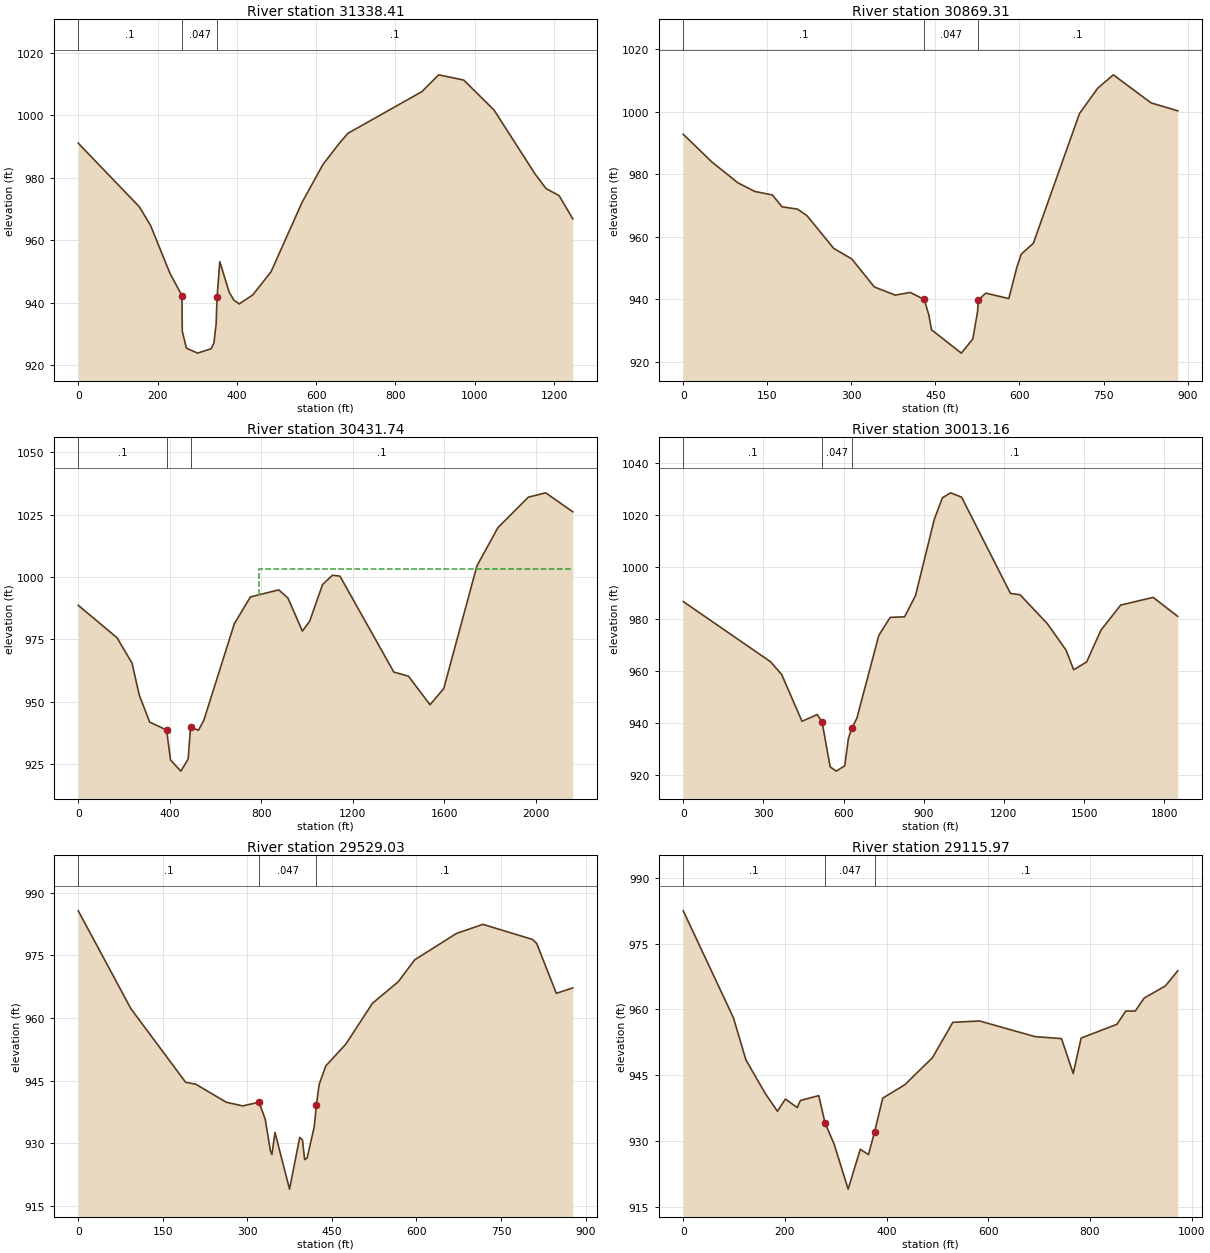
Type RM Length L Ch R = 1 ,31338.41,469.1,469.1,436.59
XS GIS Cut Line= 3
  1345484.983156   774532.794463  1345047.483252   774814.044511
  1344434.713843   775205.162079
#Sta/Elev= 30
       0   991.1  154.15  970.73  182.36  964.76  231.23  949.47   261.4  942.34
  262.34  930.94  272.74  925.51  301.09  923.93   335.1  925.34  342.19  927.21
  347.65  933.23     350  941.82  356.92  953.19  380.47  943.48  392.32   940.9
  405.87  939.68  440.18  942.56  486.19  949.97  564.03  972.07  617.08  984.29
     658     991  679.96  994.25  866.42 1007.58  908.95 1012.97  972.11  1011.3
 1048.42 1001.73 1152.46  981.17 1179.65  976.59 1212.78  974.31 1247.06  966.91
#Mann= 3 , 0 , 0
       0      .1       0   261.4    .047       0     350      .1       0
Bank Sta=261.4,350
Exp/Cntr=0.3,0.1

Type RM Length L Ch R = 1 ,30869.31,437.58,437.58,365.17
XS GIS Cut Line= 2
  1345419.153908   774116.597342  1344609.335667   774467.222751
#Sta/Elev= 30
       0  992.74   51.08  983.88   97.53  977.21  127.84  974.44  159.05  973.33
  176.29  969.53  203.85   968.8  220.74  966.72  268.41  956.26  300.78  952.86
  340.96   943.9  378.24   941.3     405  942.15  429.98   939.9  438.28  934.94
  442.98  930.23  496.19  922.74  516.76  927.28   525.3  936.15   526.5  939.71
  539.92  941.92  580.93  940.19  595.48  950.32  603.22  954.41  624.72  957.86
  707.12  999.38  739.54 1007.45  767.45 1011.75  834.95 1002.77  882.46 1000.24
#Mann= 3 , 0 , 0
       0      .1       0  429.98    .047       0   526.5      .1       0
Bank Sta=429.98,526.5
Exp/Cntr=0.3,0.1

Type RM Length L Ch R = 1 ,30431.74,418.58,418.58,217.47
XS GIS Cut Line= 3
  1345319.307252    773867.11843  1344639.584243   773899.294686
  1343788.950643   772685.223389
#Sta/Elev= 30
       0  988.68  169.45   975.7   235.2  965.55  266.82  952.76  312.42  941.93
  386.31  938.76  403.73  926.72  448.86   922.3  480.62  927.13   491.2  939.89
  525.69  938.66  549.13  942.63  682.58  981.28  752.77  992.02  877.05  994.86
  917.13  991.58  980.29  978.37 1011.95  982.26 1068.78  997.03 1112.02 1000.72
 1144.57 1000.36  1380.2  961.96  1444.4   960.3 1538.62  948.87 1598.59  955.33
 1743.72 1004.47 1835.51 1019.74 1968.63 1031.97  2044.7  1033.7  2162.9 1026.11
#Mann= 3 , 0 , 0
       0      .1       0  386.31    .047       0   491.2      .1       0
#XS Ineff= 2 , 0
                           788.9         1003.39
Permanent Ineff=
       F       F
Bank Sta=386.31,491.2
Exp/Cntr=0.3,0.1

Type RM Length L Ch R = 1 ,30013.16,484.13,484.13,332.02
XS GIS Cut Line= 4
  1345417.976948    773830.88291  1345100.183284   773681.332958
  1344875.858292   773371.550814  1344189.530867   772490.274397
#Sta/Elev= 30
       0  986.77  326.66  963.67  368.37  958.74  444.43   940.8  501.35  943.38
  519.56  940.52  549.75   923.3  572.65  921.66  604.42  923.73  618.23  934.31
     631  938.23  649.75  941.96  731.84  973.78  774.39   980.7  828.38  980.93
  869.32   989.1  939.72 1018.43  969.92 1026.62 1000.33 1028.53 1041.64 1026.87
 1224.65   989.9 1260.56  989.39 1362.88  978.25 1432.93  968.09 1461.23  960.57
 1509.75  963.59  1562.9  975.74 1637.12  985.42 1758.61  988.38  1850.7  981.08
#Mann= 3 , 0 , 0
       0      .1       0  519.56    .047       0     631      .1       0
Bank Sta=519.56,631
Exp/Cntr=0.3,0.1

Type RM Length L Ch R = 1 ,29529.03,413.06,413.06,418.58
XS GIS Cut Line= 3
  1345475.557236   773812.430942   1345405.24466   773684.826846
  1345491.182196   772958.264285
#Sta/Elev= 30
       0  985.65   93.44  962.21  190.56  944.58  208.59  944.13   262.6  939.81
  291.79  938.93  320.76  939.81  331.74  935.72  341.08  928.03  343.53  927.31
  349.07  932.57  374.85     919  392.92  931.39  397.76   930.8  401.67  926.07
  406.06  926.46  418.73  933.99  422.51  939.17  427.42  944.07  439.14  948.51
  474.85  953.75  521.93  963.51  567.92  968.69  596.78  973.91  670.87  980.22
  717.89  982.41  805.86   978.8  813.32  977.85  848.14  965.89  877.32   967.2
#Mann= 3 , 0 , 0
       0      .1       0  320.76    .047       0  422.51      .1       0
Bank Sta=320.76,422.51
Exp/Cntr=0.3,0.1

Type RM Length L Ch R = 1 ,29115.97,481.13,481.13,466.92
XS GIS Cut Line= 3
  1345811.494644    773841.07683  1345858.369652   773322.847582
   1345733.10002   772888.184029
#Sta/Elev= 30
       0  982.52   98.68  958.11  123.33  948.47  161.61  940.78  185.25  936.77
  200.93  939.57  224.16  937.61   230.5  939.25  266.57  940.34  278.88  934.12
  296.78  929.27  324.35     919  348.22   928.1  364.36  926.88  376.38   932.1
  392.32  939.76  435.95  942.84  490.23  949.01  530.24  957.07  582.81  957.38
  691.99  953.81  744.04  953.35  767.05   945.4  782.65  953.48  853.02  956.62
   870.3  959.63  889.13  959.65  906.67  962.61   948.5  965.39   972.7  968.82
#Mann= 3 , 0 , 0
       0      .1       0  278.88    .047       0  376.38      .1       0
Bank Sta=278.88,376.38
Exp/Cntr=0.3,0.1