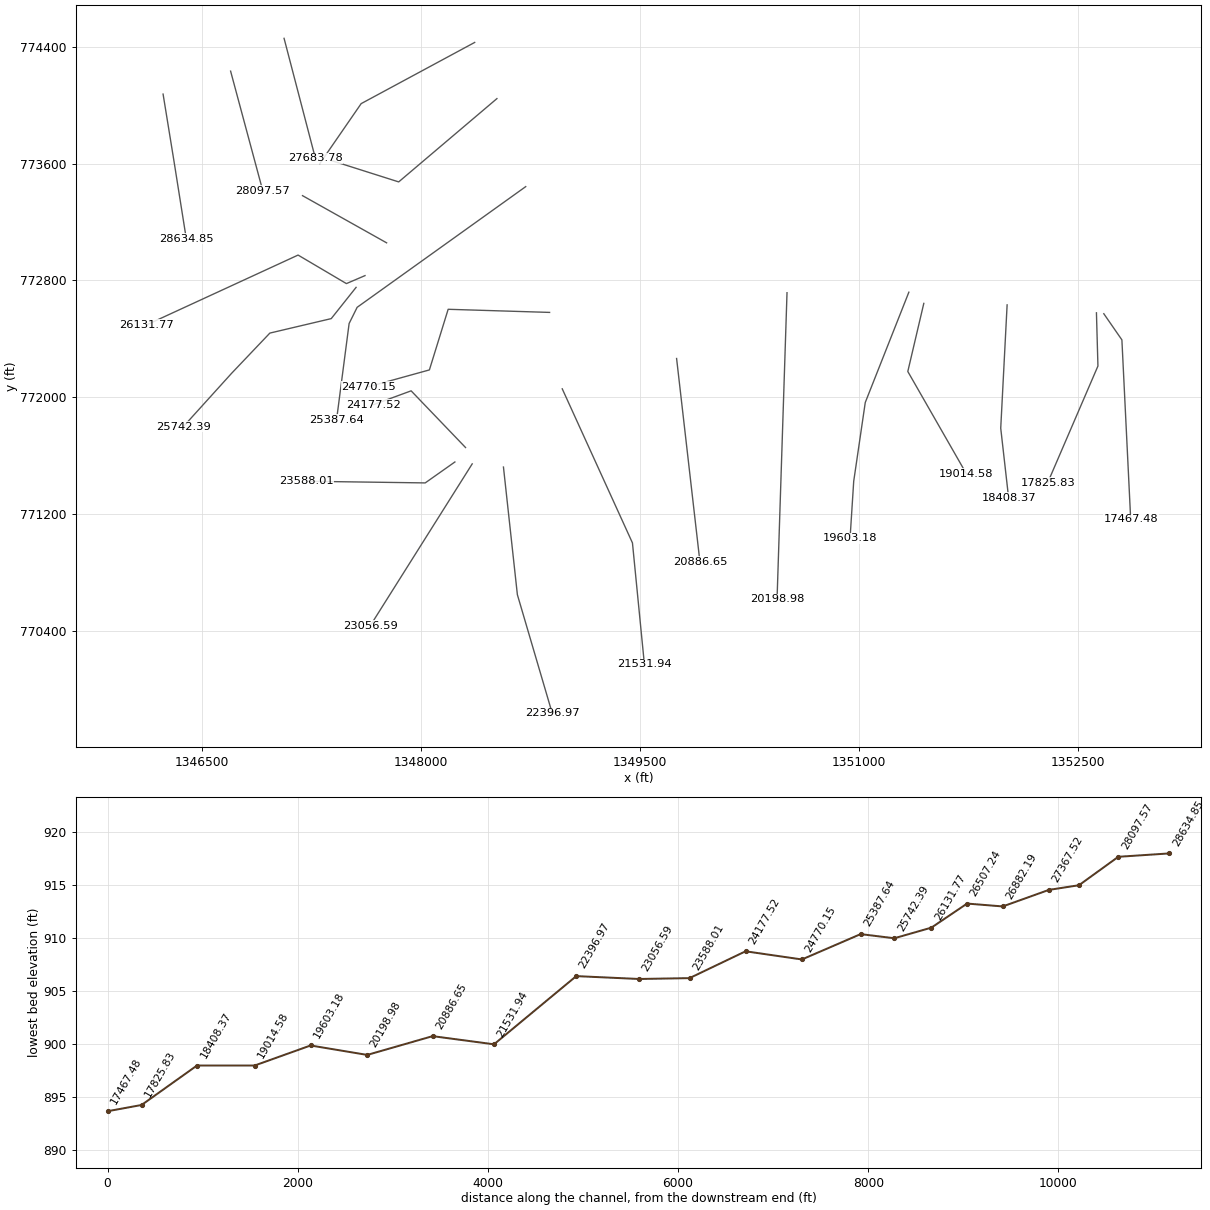
HEC-RAS study LLRiver.prj: LLRiver

--- LLRiver.g01 (geometry) --- (continued)

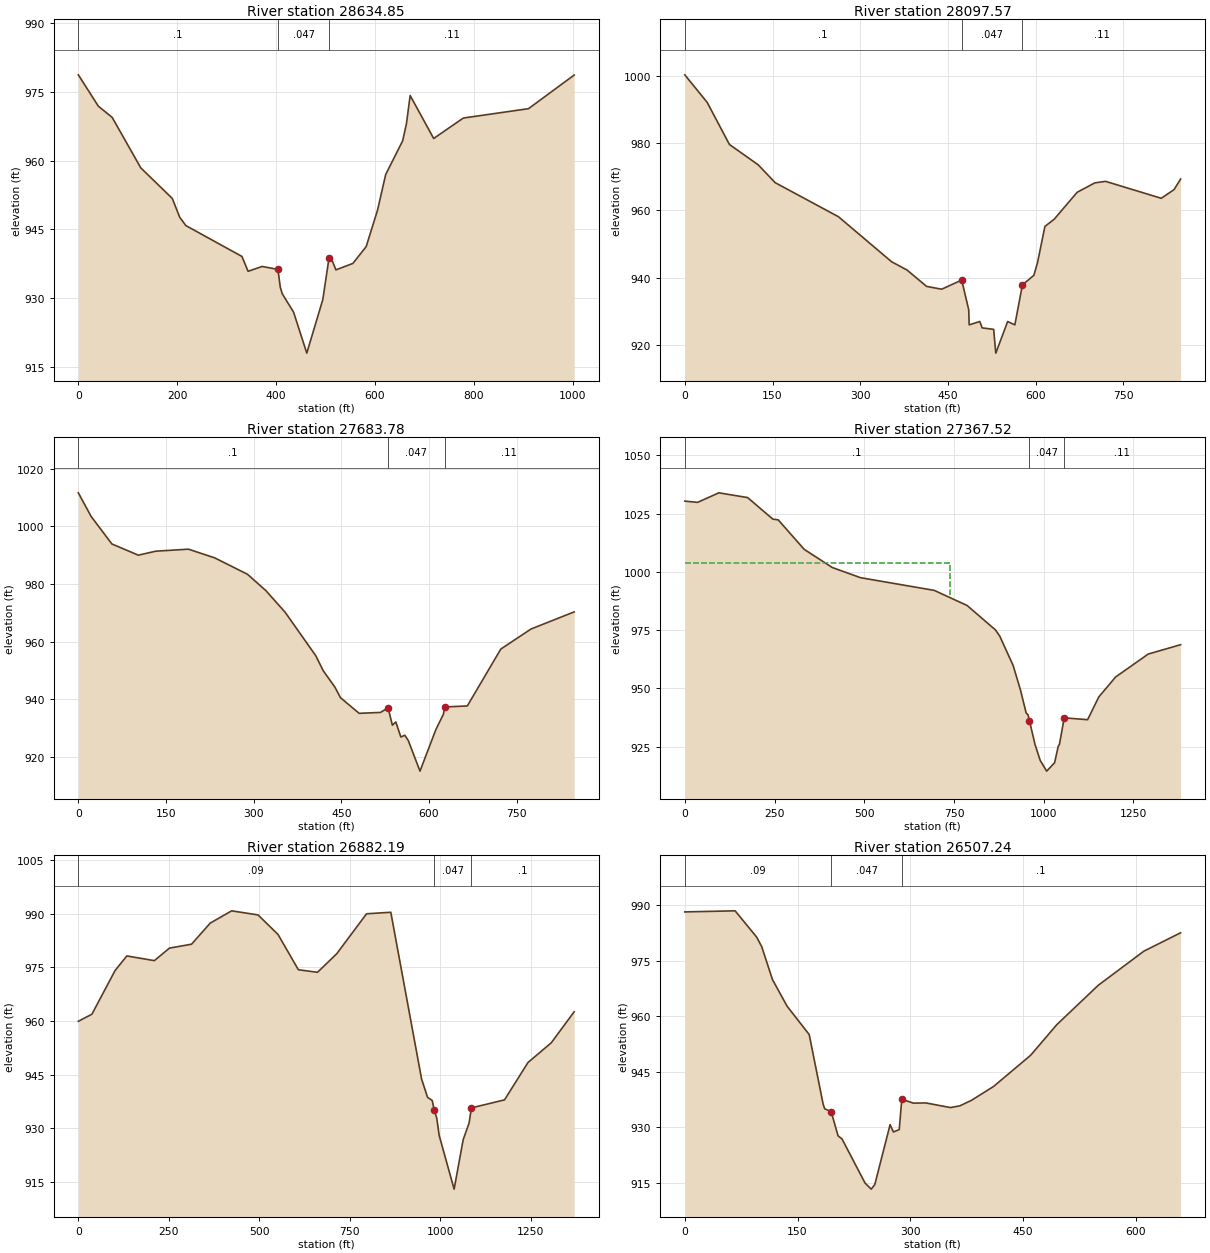
Type RM Length L Ch R = 1 ,28634.85,537.27,537.27,516.84
XS GIS Cut Line= 3
  1346235.973877   774075.451742  1346309.279861   773624.415198
  1346394.848373   773085.157853
#Sta/Elev= 30
       0  978.68   40.52  971.84   68.44   969.4  126.36  958.39  190.11  951.72
  205.12  947.62   217.5  945.81  330.94  939.08  343.41  935.84  371.89   936.9
  403.81  936.25  408.49  932.38  412.46  930.95  435.38  926.94  462.14     918
  494.53  929.68  507.06  938.72   511.1  938.83  521.08  936.15  555.32  937.56
  582.25  941.22  605.26  949.18  621.74  956.95   656.1   964.3   663.6  967.94
  671.23  974.17  718.81   964.8  778.79  969.26  910.61   971.3 1002.96  978.63
#Mann= 3 , 0 , 0
       0      .1       0  403.81    .047       0  507.06     .11       0
Bank Sta=403.81,507.06
Exp/Cntr=0.3,0.1

Type RM Length L Ch R = 1 ,28097.57,413.8,413.8,415.18
XS GIS Cut Line= 2
  1346698.142837   774232.661598  1346918.265589   773413.993438
#Sta/Elev= 30
       0 1000.21   38.39  992.01    76.3  979.56  125.48  973.53   154.5  968.23
  262.72  958.13  353.66  944.77  379.87  942.33  413.48  937.46  439.25  936.64
  473.42  939.35  485.44  930.55  486.22  926.06  504.36  927.06  508.42  925.17
  528.08  924.73  531.72  917.68  552.02  927.06  564.32  926.06  577.22   937.9
  596.82  940.76  603.01  944.47  615.72  955.25  631.65   957.4  670.84  965.38
  701.04  968.17   719.4  968.62  814.63   963.6  836.44  966.16  847.74   969.3
#Mann= 3 , 0 , 0
       0      .1       0  473.42    .047       0  577.22     .11       0
Bank Sta=473.42,577.22
Exp/Cntr=0.3,0.1

Type RM Length L Ch R = 1 ,27683.78,316.26,316.26,529.43
XS GIS Cut Line= 2
  1347064.139126   774457.112287  1347278.479478   773636.148446
#Sta/Elev= 30
       0 1011.69   21.99 1003.46   57.46  993.92  102.72  990.03  132.53  991.41
  188.51  992.11  233.55  989.08  289.36  983.41  320.96  977.71  353.89   970.2
  406.39  955.08  419.05   949.9  439.08  944.18  448.58  940.52  480.57  935.08
  517.11   935.4  530.11  937.02  537.37  930.96  543.32  932.08  551.93  926.85
  558.68  927.47  564.62  925.65  584.67     915   611.9  929.47  624.69  934.73
   626.9  937.29  665.65  937.65  722.94   957.4  774.61  964.37  848.48  970.32
#Mann= 3 , 0 , 0
       0      .1       0  530.11    .047       0   626.9     .11       0
Bank Sta=530.11,626.9
Exp/Cntr=0.3,0.1

Type RM Length L Ch R = 1 ,27367.52,485.33,485.33,631.97
XS GIS Cut Line= 3
  1348368.918007   774429.082719  1347591.901686   774010.233054
  1347308.810614   773599.751006
#Sta/Elev= 30
       0 1030.34   35.62 1029.81   94.95  1033.9  175.07 1031.86  245.28 1022.62
  260.32  1022.3  332.57 1009.67  410.67 1001.89  489.57  997.51  694.92  992.07
  786.45   985.6  865.64  975.09  877.42  972.47  914.64   959.9  934.82  949.56
  951.11  939.44  955.95  938.81  960.16  936.25  975.58  926.06  990.15  919.15
 1008.21  914.56 1030.26  918.16 1040.38   925.2 1043.76  926.06  1057.1  937.41
 1122.23  936.62 1153.45  946.38 1200.05   954.9 1291.05  964.76 1381.35  968.78
#Mann= 3 , 0 , 0
       0      .1       0  960.16    .047       0  1057.1     .11       0
#XS Ineff= 2 , 0
          738.85  1003.8
Permanent Ineff=
       F       F
Bank Sta=960.16,1057.1
Exp/Cntr=0.3,0.1

Type RM Length L Ch R = 1 ,26882.19,374.95,374.95,488.24
XS GIS Cut Line= 3
  1348521.138423   774044.525662  1347848.705654   773474.382174
   1347383.62751    773621.99395
#Sta/Elev= 30
       0  959.91   37.52  961.89  101.52  974.09  133.86  978.17     210  976.86
   251.7  980.36  312.66  981.45  364.39  987.35  423.53  990.78  496.42  989.63
  551.64  984.17  607.83  974.31  660.68   973.6  713.85   978.8  796.08  989.95
  863.09  990.38   948.1  943.79  964.56  938.67   977.5  937.77  982.84  935.22
  990.02  932.85  996.77  927.99 1038.01     913 1063.04  926.82 1079.42  931.49
 1085.68   935.7 1177.25  937.95 1241.96  948.38 1306.42  953.91 1369.55  962.57
#Mann= 3 , 0 , 0
       0     .09       0  982.84    .047       0 1085.68      .1       0
Bank Sta=982.84,1085.68
Exp/Cntr=0.3,0.1

Type RM Length L Ch R = 1 ,26507.24,375.47,375.47,294.27
XS GIS Cut Line= 2
   1347765.99871   773057.346141  1347190.477942   773380.262878
#Sta/Elev= 30
       0  988.19   66.99  988.48   95.71  981.37  102.46  978.75  116.72  969.89
  136.15  962.71  165.57  955.05  184.24  936.13  186.26  934.98  194.84  934.21
  203.99  927.67  209.21  926.85  239.93  914.91  248.12  913.27  252.88   914.5
  273.27  930.71  277.65  928.71   285.4  929.36  288.82  937.57  304.15  936.51
   320.9  936.56  353.64  935.31  366.06  935.78  381.58  937.27  410.93  941.01
  460.29  949.44  495.18  957.73  550.29  968.36  610.96  977.57  659.92  982.55
#Mann= 3 , 0 , 0
       0     .09       0  194.84    .047       0  288.82      .1       0
Bank Sta=194.84,288.82
Exp/Cntr=0.3,0.1

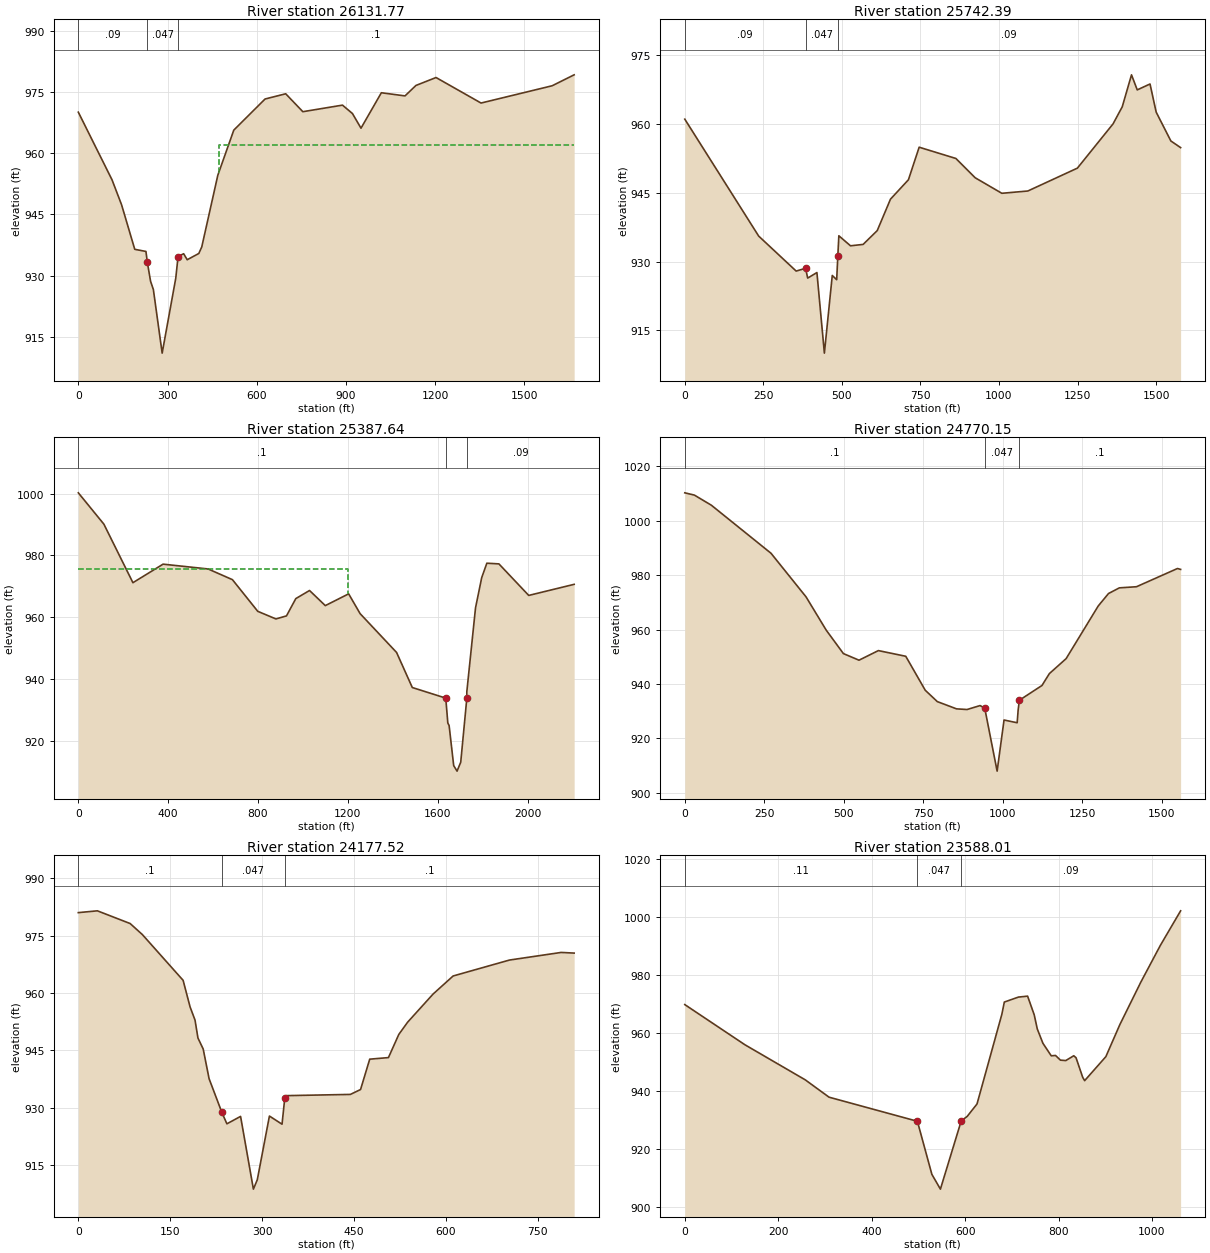
Type RM Length L Ch R = 1 ,26131.77,389.38,389.38,172.79
XS GIS Cut Line= 4
  1347618.188662   772832.933853  1347490.797686   772778.337757
  1347160.027766   772973.551069  1346120.678005   772494.678109
#Sta/Elev= 30
       0     970  113.42  953.42  145.53   947.3  189.74  936.42  227.32   935.9
  232.11   933.2  242.84  928.61   252.3  926.57  281.87     911  327.55  929.33
  335.38  934.66  354.08  935.34  366.09  933.87   405.1   935.4  414.95  936.99
  468.97  954.56  522.68  965.61  627.88  973.23  697.24  974.51  754.85  970.12
  888.11  971.73  921.53  969.68  950.39  966.09 1018.84  974.76 1098.32  973.99
 1135.15  976.55 1202.65  978.49 1353.99  972.24 1593.09  976.47 1667.04  979.15
#Mann= 3 , 0 , 0
       0     .09       0  232.11    .047       0  335.38      .1       0
#XS Ineff= 2 , 0
                          472.03           961.9
Permanent Ineff=
       F       F
Bank Sta=232.11,335.38
Exp/Cntr=0.3,0.1

Type RM Length L Ch R = 1 ,25742.39,354.76,354.76,232.64
XS GIS Cut Line= 5
  1347557.146358   772752.530525  1347387.015542   772538.625757
  1346966.887158   772439.534173  1346705.174773   772164.469085
  1346374.028405   771798.605788
#Sta/Elev= 30
       0  961.07  235.15  935.55  354.46  927.91  384.38  928.52  391.17  926.38
  420.51  927.59  444.28     910  469.36  926.95  483.44  926.03  487.08  931.27
  490.33  935.62  527.34  933.43  567.55  933.73  612.53  936.75  654.67  943.61
  711.74  947.84  745.96  954.95  862.85  952.49  924.24  948.28 1009.06  944.89
 1091.84  945.39 1249.51  950.38 1363.14  960.05 1392.32  963.77 1421.81  970.75
 1440.07  967.46 1480.71  968.75 1500.36   962.6  1547.1  956.31 1578.12  954.86
#Mann= 3 , 0 , 0
       0     .09       0  384.38    .047       0  487.08     .09       0
Bank Sta=384.38,487.08
Exp/Cntr=0.3,0.1

Type RM Length L Ch R = 1 ,25387.64,617.49,617.49,636.21
XS GIS Cut Line= 4
  1348718.199415   773442.028894   1347564.33599   772615.927901
  1347509.411318   772505.139293   1347423.47391   771846.285148
#Sta/Elev= 30
       0 1000.23  113.81  990.11  243.02  971.22  377.21   977.2  577.83  975.65
  685.95   972.2  798.67  961.98  879.56  959.52  926.56   960.5  968.02  966.08
 1029.19   968.7 1099.44  963.82 1203.34  967.62 1254.36  961.23 1416.68   948.7
 1486.71  937.38 1635.61  933.96 1644.82  925.92 1650.57   925.1 1670.97  912.17
 1685.94  910.39 1702.26  913.26 1729.31  933.84 1729.43  936.06 1768.15  963.11
 1795.73  972.88 1818.54  977.51 1872.28  977.29 2004.94  967.11 2207.19  970.69
#Mann= 3 , 0 , 0
       0      .1       0 1635.61    .047       0 1729.31     .09       0
#XS Ineff= 2 , 0
         1202.39  975.68
Permanent Ineff=
       F       F
Bank Sta=1635.61,1729.31
Exp/Cntr=0.3,0.1

Type RM Length L Ch R = 1 ,24770.15,592.63,592.63,1020.88
XS GIS Cut Line= 4
  1348881.660663   772581.072477  1348187.321591   772602.436829
  1348058.890487   772187.431005  1347644.828022   772072.847708
#Sta/Elev= 30
       0 1010.31   30.26 1009.47   83.32 1005.77  271.06  988.09  381.18  972.06
  444.48  959.85  498.61  951.21  547.64  948.78  608.56  952.31  694.67  950.22
  755.92  937.73  793.81  933.56  854.29  930.89  887.44  930.65  928.26   932.1
  942.91  931.16  981.87     908 1003.59  926.79 1044.87  925.78 1047.97   930.5
 1051.86  934.06 1122.88  939.49 1146.03  943.84 1198.79  949.36 1299.75  968.72
    1332  973.29 1366.04  975.37    1420  975.79 1548.87  982.49 1558.72  982.16
#Mann= 3 , 0 , 0
       0      .1       0  942.91    .047       0 1051.86      .1       0
Bank Sta=942.91,1051.86
Exp/Cntr=0.3,0.1

Type RM Length L Ch R = 1 ,24177.52,589.51,589.51,424.35
XS GIS Cut Line= 3
  1348306.286327   771656.180956   1347933.89055    772044.20182
   1347678.68223   771950.451804
#Sta/Elev= 30
       0     981   31.11  981.47   84.62  978.15  104.61  975.26  171.13  963.31
  182.48  956.37  190.56  952.93  195.34  948.25  203.89  945.38  213.53  937.62
  234.32  928.84  242.59  925.83  264.95  927.77  285.89  908.77  292.26  911.22
  312.06  927.86  332.67  925.73   337.1  932.55  339.42  933.19  444.22  933.51
  460.88  934.79  475.85  942.72  506.42  943.13  523.34  949.18  537.81  952.39
  579.32  959.73  612.06  964.45  704.04  968.61  788.46   970.6  809.69  970.43
#Mann= 3 , 0 , 0
       0      .1       0  234.32    .047       0   337.1      .1       0
Bank Sta=234.32,337.1
Exp/Cntr=0.3,0.1

Type RM Length L Ch R = 1 ,23588.01,531.42,531.42,329.02
XS GIS Cut Line= 3
  1348233.369719    771557.22262  1348030.244726   771413.993436
  1347217.592438   771425.342556
#Sta/Elev= 30
       0  969.75  128.51  955.94  257.84  943.85  308.81  937.88  497.86  929.59
  528.84  911.33  547.12  906.24  591.68  929.72  604.47  931.28  625.49  935.55
  678.66  966.42  683.92  970.62  714.03  972.33  733.75  972.66  747.89  966.24
  754.54  961.34  766.52  956.44  784.38  952.12  793.56  952.24  804.01  950.63
  815.47  950.49  832.57  952.14  837.41  951.46  851.69  944.73  855.84  943.57
  901.24  951.83  931.17  962.85  976.01  977.45 1017.91  990.13 1061.28 1002.02
#Mann= 3 , 0 , 0
       0     .11       0  497.86    .047       0  591.68     .09       0
Bank Sta=497.86,591.68
Exp/Cntr=0.3,0.1

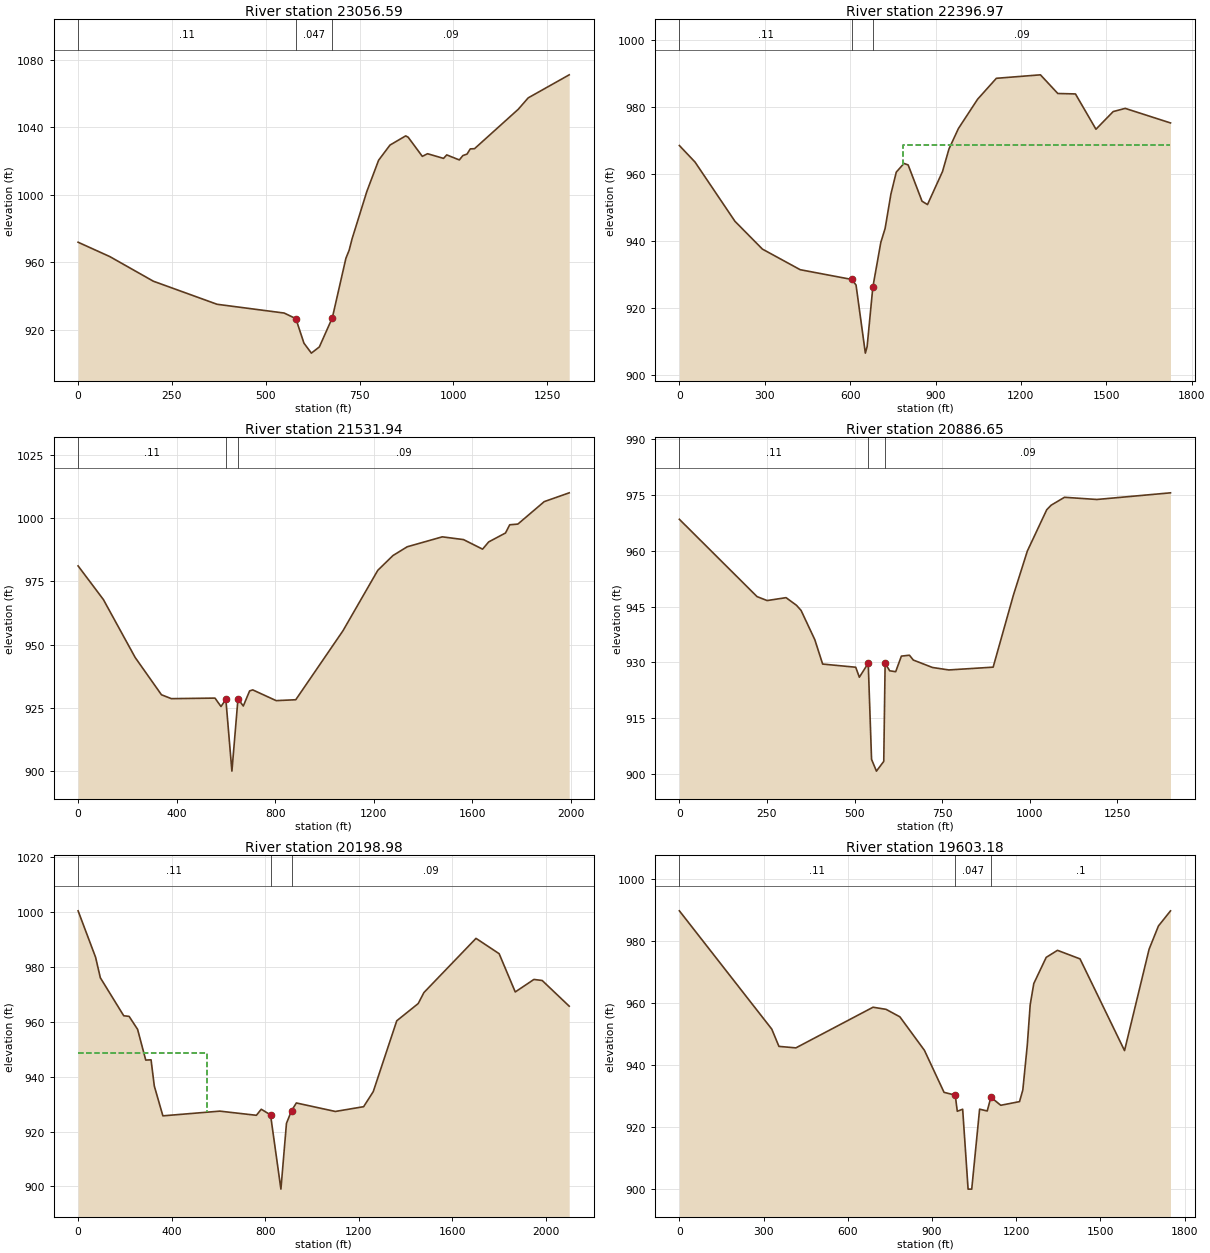
Type RM Length L Ch R = 1 ,23056.59,659.62,659.62,534.28
XS GIS Cut Line= 2
  1348351.957495   771544.216924  1347654.564982   770437.016539
#Sta/Elev= 30
       0  971.84   84.48  963.34  200.45  948.76  370.32  935.09     549   929.9
  580.18  926.59  601.74  912.07  621.55  906.16  642.87  909.85  677.47  927.16
  713.52  962.31  722.27  967.16  729.89  973.77  769.18 1001.81  800.71 1020.41
  830.99 1029.38  872.88 1034.83  879.44 1034.04  917.17 1022.69  931.02 1024.26
  973.69  1021.5  982.23 1023.56 1015.76 1020.58 1025.24 1023.17 1036.31 1024.05
 1044.94 1027.13 1056.24 1027.24 1172.89 1050.61 1199.27 1057.34 1308.53 1070.99
#Mann= 3 , 0 , 0
       0     .11       0  580.18    .047       0  677.47     .09       0
Bank Sta=580.18,677.47
Exp/Cntr=0.3,0.1

Type RM Length L Ch R = 1 ,22396.97,865.04,865.04,788.51
XS GIS Cut Line= 3
  1348565.834999   771522.500444  1348661.110775   770649.110107
  1348899.961847   769836.438106
#Sta/Elev= 30
       0  968.47   54.99  963.53  195.26  945.83  291.73  937.52  424.55  931.36
  606.11  928.44  620.76  926.77  653.44  906.43  659.64  908.35  679.76  926.14
  707.83  939.54  722.89  943.69  743.22  953.94  762.15  960.53  789.15  963.12
  803.87  962.67  852.61  951.83   871.8  950.83  924.53  960.69  947.36  967.47
  980.42  973.55 1047.88  982.31 1113.76  988.56 1268.63   989.6  1329.7  984.02
 1391.68  983.89 1463.75  973.34 1524.33  978.62 1566.59  979.57 1725.62  975.22
#Mann= 3 , 0 , 0
       0     .11       0  606.11    .047       0  679.76     .09       0
#XS Ineff= 2 , 0
                          785.42          968.67
Permanent Ineff=
       F       F
Bank Sta=606.11,679.76
Exp/Cntr=0.3,0.1

Type RM Length L Ch R = 1 ,21531.94,645.29,645.29,707.6
XS GIS Cut Line= 3
  1348968.263159    772058.02838  1349448.859384   771003.262683
  1349530.600696   770172.250075
#Sta/Elev= 30
       0  981.13  102.62  967.84  231.79  944.92  338.49  930.19  378.71  928.65
  555.84  928.87  580.24  925.54  599.97  928.36  601.15  928.23  601.28  926.86
  624.53     900  649.19  928.56   670.8  925.74  696.51  931.72  708.94  932.12
  804.28  927.87  883.78  928.22 1075.47  955.49 1216.93  979.39 1278.51  985.23
 1336.38  988.69 1478.85  992.62 1565.01  991.53 1642.34  987.75 1667.15  990.61
 1735.44  994.14 1752.56  997.39 1785.59  997.66 1892.73 1006.54 1994.12 1010.02
#Mann= 3 , 0 , 0
       0     .11       0  599.97    .047       0  649.19     .09       0
Bank Sta=599.97,649.19
Exp/Cntr=0.3,0.1

Type RM Length L Ch R = 1 ,20886.65,687.67,687.67,728.57
XS GIS Cut Line= 2
  1349751.020152   772265.555933  1349910.742392   770873.194843
#Sta/Elev= 30
       0  968.49  221.65   947.7  250.39  946.64  304.39  947.42  334.25  945.36
  347.32  943.98  386.56   936.1  408.86  929.56   503.2  928.71   513.6  926.02
  538.92   929.8  548.42  903.94  562.35  900.77  583.24  903.39  587.15   929.8
  600.18  927.75  617.29  927.51  633.54   931.7  656.45  931.94  667.63  930.64
  722.26  928.64  768.93  927.98  895.39  928.73  953.26  948.12  993.01  959.96
  1048.3  971.06 1060.92  972.28 1098.95  974.41 1191.36  973.82 1401.49  975.61
#Mann= 3 , 0 , 0
       0     .11       0  538.92    .047       0  587.15     .09       0
Bank Sta=538.92,587.15
Exp/Cntr=0.3,0.1

Type RM Length L Ch R = 1 ,20198.98,595.8,595.8,596.12
XS GIS Cut Line= 2
  1350506.840313   772715.877981  1350438.539001   770616.511067
#Sta/Elev= 30
       0 1000.48   74.87  983.53   95.16  976.07  195.29  962.21  218.16     962
  254.52  957.25  289.34  946.06  312.07  946.15  325.99  936.58  362.65  925.72
  606.01  927.44  762.57  925.92  783.34  928.13  823.08  926.07  867.44     899
  891.19  922.98  912.99  927.62  933.47  930.42 1100.24  927.32 1221.19  929.06
 1262.28  934.54 1362.85  960.38 1454.71  966.67 1478.99  970.67 1701.88  990.44
  1800.8  984.85 1869.71   970.9 1949.53  975.46 1984.88  975.08 2100.48  965.71
#Mann= 3 , 0 , 0
       0     .11       0  823.08    .047       0  912.99     .09       0
#XS Ineff= 2 , 0
          549.51  948.76
Permanent Ineff=
       F       F
Bank Sta=823.08,912.99
Exp/Cntr=0.3,0.1

Type RM Length L Ch R = 1 ,19603.18,588.6,588.6,470.83
XS GIS Cut Line= 4
   1351340.83545   772719.472861  1351042.466425    771964.56342
  1350963.380729   771425.342556  1350938.217081   771033.508571
#Sta/Elev= 30
       0  989.79   329.1  951.58  354.63     946  415.03  945.52  689.82  958.65
  736.07  957.97  785.43  955.55  872.79  944.74  942.78  931.15  982.57  930.25
  989.92  925.04 1009.08   925.7 1028.41  899.89 1041.36  899.89 1069.42  925.72
 1096.52  925.13 1109.68  929.58 1144.74  926.97 1211.62  928.16 1223.35  931.92
 1239.26   946.4 1249.59  959.44 1262.44  966.31 1306.71  974.76 1346.77  977.03
 1427.06  974.27 1585.66  944.64  1673.1  977.37 1706.41   984.9 1749.36  989.77
#Mann= 3 , 0 , 0
       0     .11       0  982.57    .047       0 1109.68      .1       0
Bank Sta=982.57,1109.68
Exp/Cntr=0.3,0.1

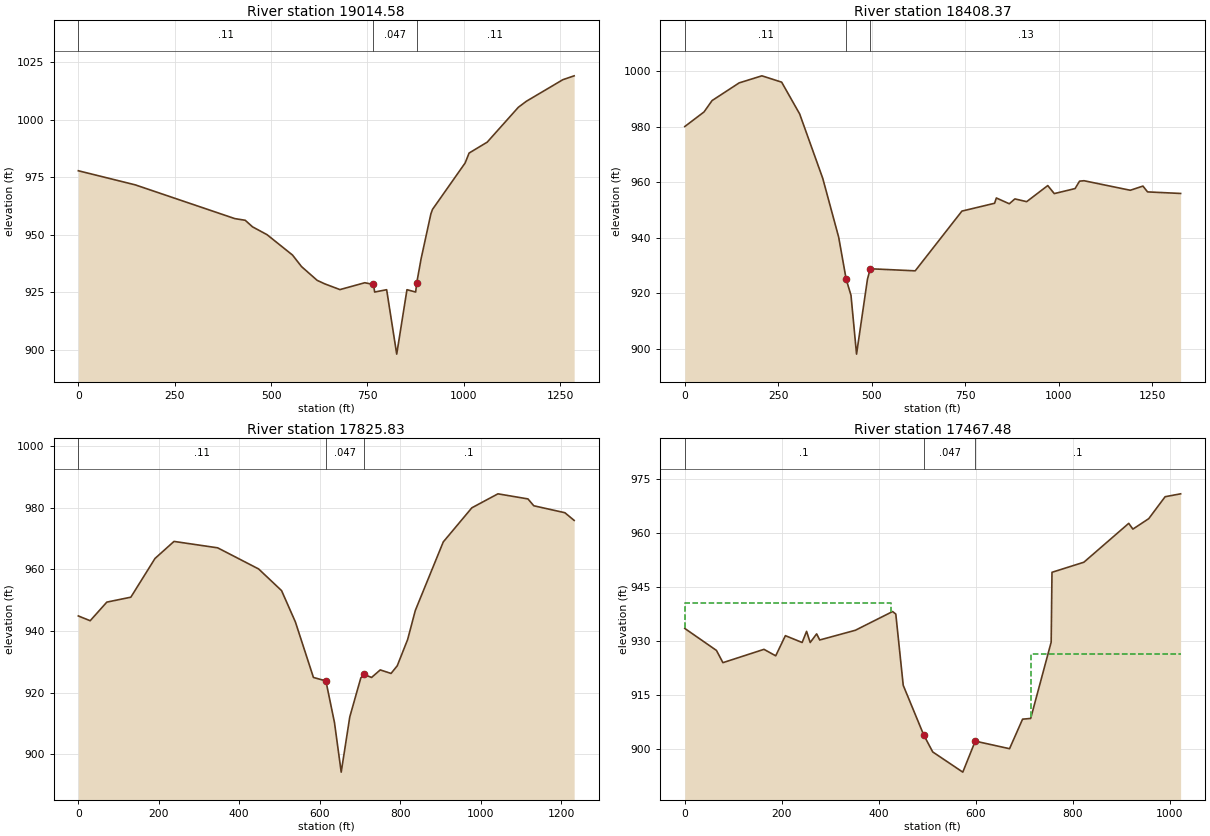
Type RM Length L Ch R = 1 ,19014.58,606.21,606.21,718.32
XS GIS Cut Line= 3
  1351443.149818   772642.870749  1351333.645818   772176.656989
  1351734.816506   771476.204124
#Sta/Elev= 30
       0  977.76  147.74  971.62  406.03  956.94  432.92  956.22   451.7  953.38
  489.58  949.95  555.53   941.1  579.09  936.05  619.51  930.09  639.96  928.51
  678.63  926.07  743.06  929.05  764.09  928.34  766.86  927.03   768.6  925.01
  799.75  926.02  825.84     898  852.42  926.02  875.02  925.02  877.63  928.86
  889.12  939.51   914.5  959.03  918.59  960.93 1003.32  981.14 1013.54  985.45
 1060.62  990.21 1141.25 1005.35 1162.19 1007.99 1256.81 1017.37  1286.1 1019.05
#Mann= 3 , 0 , 0
       0     .11       0  764.09    .047       0  877.63     .11       0
Bank Sta=764.09,877.63
Exp/Cntr=0.3,0.1

Type RM Length L Ch R = 1 ,18408.37,582.54,582.54,654.5
XS GIS Cut Line= 3
   1352013.42617   772632.707293  1351969.722234   771788.428508
   1352023.84857     771310.3087
#Sta/Elev= 30
       0  980.06   51.44  985.32   72.91  989.41  145.55   995.8  206.31  998.34
  259.13  996.06  307.33   984.6  369.08  961.38  411.74  940.15  431.78  924.99
  444.65  919.23  459.51     898  488.68  924.99  496.22  928.78  616.45  928.03
  741.46  949.57  828.84  952.39  833.59   954.3  868.16  952.21  883.19  953.97
  914.65  952.97   971.1  958.77  988.55  955.88 1044.22  957.69 1056.11  960.36
 1068.06  960.52 1191.93  957.08 1225.75  958.59 1238.13  956.49 1326.58  955.93
#Mann= 3 , 0 , 0
       0     .11       0  431.78    .047       0  496.22     .13       0
Bank Sta=431.78,496.22
Exp/Cntr=0.3,0.1

Type RM Length L Ch R = 1 ,17825.83,358.35,358.35,250.34
XS GIS Cut Line= 3
  1352624.860411   772578.402013  1352635.100795   772213.950685
  1352291.746426   771416.670044
#Sta/Elev= 30
       0  944.89   29.47  943.34   70.87  949.37  130.55  950.97  190.59  963.51
  237.82  969.04  346.44  966.96  448.31  960.11  505.31  953.09  539.72  942.91
   584.5  924.96  615.45  923.83  636.78  910.37  653.54  894.28  674.86  912.18
  702.29  924.82  710.37  925.93     729  924.96  750.58   927.4  777.45  926.26
  792.83  928.73  818.69  937.25  837.79  946.67  907.26  968.87  978.33  979.93
 1043.19  984.46 1117.79  982.81 1132.34  980.59 1209.58  978.34 1232.67  975.85
#Mann= 3 , 0 , 0
       0     .11       0  615.45    .047       0  710.37      .1       0
Bank Sta=615.45,710.37
Exp/Cntr=0.5,0.3

Type RM Length L Ch R = 1 ,17467.48,94.39,94.39,96.84
BEGIN DESCRIPTION:
Upstream xs of Bridge 37003-0070
END DESCRIPTION:
XS GIS Cut Line= 3
  1352675.350267   772571.976029  1352799.091963   772393.029341
  1352859.228411   771166.140508
#Sta/Elev= 30
       0   933.6  65.266   927.5   78.63   924.1 163.271   927.8 187.454     926
 207.394   931.6 241.972   929.7 251.094   932.8 258.589   929.7 271.883   932.1
 278.247   930.4 351.715   933.1 428.507   938.3 435.083   937.6 450.427   917.8
  492.62  904.03 511.238   899.3  573.23  893.69 598.919   902.3  669.63   900.2
   696.5   908.4 713.188   908.6 755.473   929.8  757.17   949.2 822.931     952
  915.42   962.8 923.976   961.2 956.645   964.1 990.444   970.21022.406     971
#Mann= 3 , 0 , 0
       0      .1       0  492.62    .047       0 598.919      .1       0
#XS Ineff= 2 , 0
       0   426.2  940.77 714.036       0   926.5
Permanent Ineff=
       F       F
Bank Sta=492.62,598.919
Skew Angle= 45
Exp/Cntr=0.5,0.3