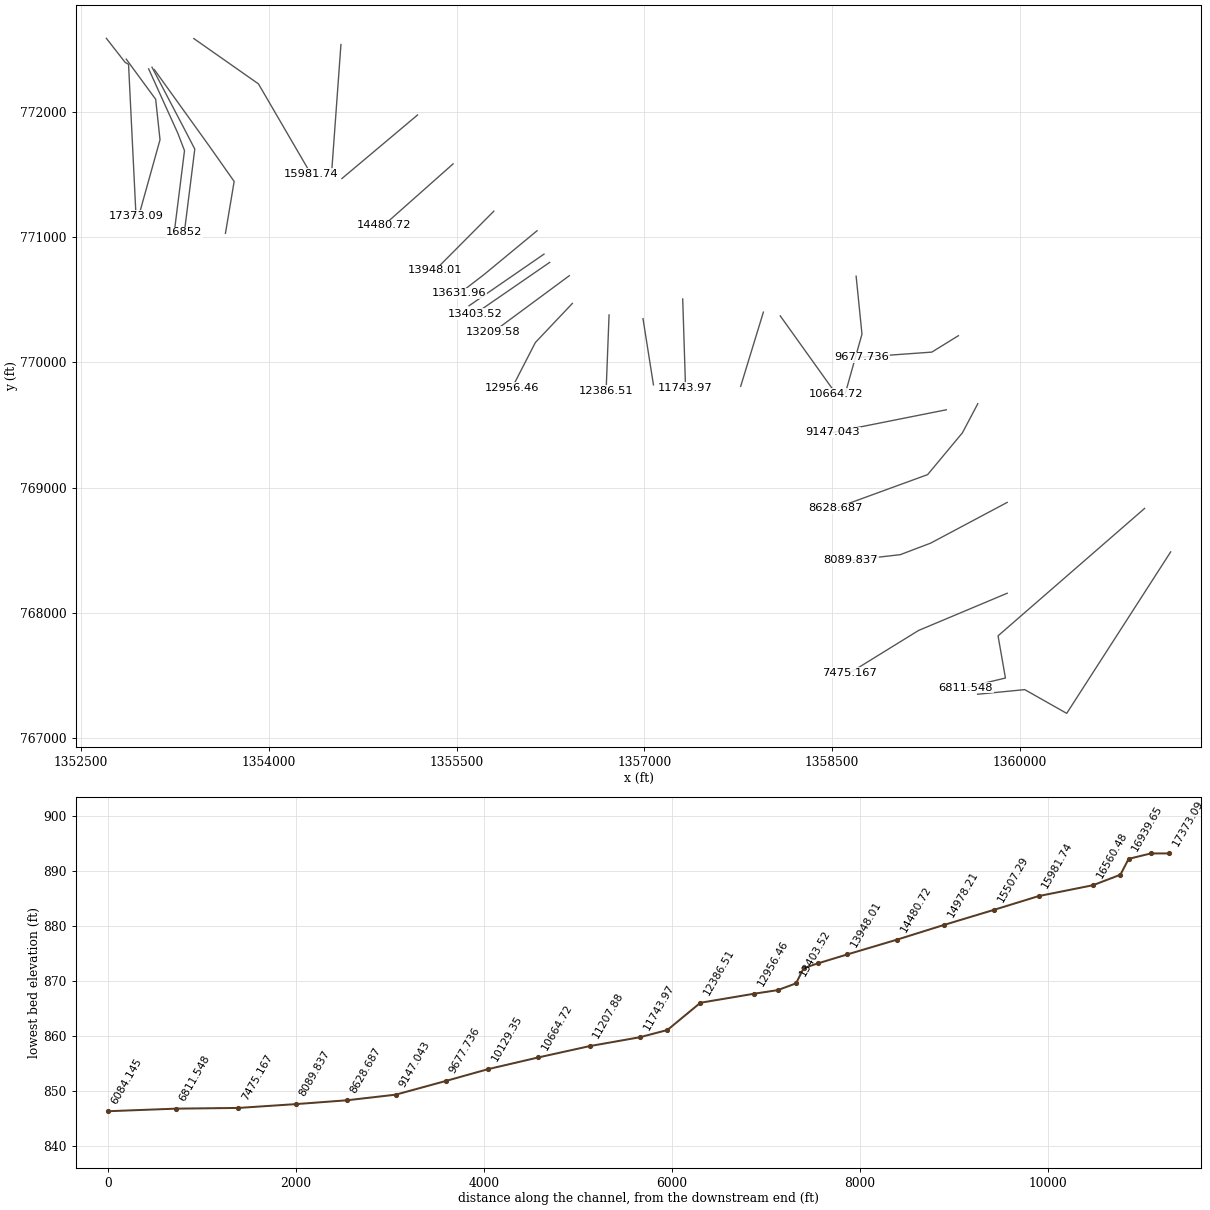
HEC-RAS study LLRiver.prj: LLRiver

--- LLRiver.g01 (geometry) --- (continued)

Type RM Length L Ch R = 3 ,17420.68,,,
BEGIN DESCRIPTION:
Bridge : 37003-0070 - NC-16
END DESCRIPTION:
Bridge Culvert--1,0,-1,-1, 0
Deck Dist Width WeirC Skew NumUp NumDn MinLoCord MaxHiCord MaxSubmerge Is_Ogee
26.8,40,2.6,45, 167, 168, , , 0.95, 0, 0,0,,
 -60.811 -56.922 -51.124 -45.891 -38.962  -34.86 -26.941 -23.829 -14.566 -12.587
  -2.192  -1.344   6.718    9.97  10.536  21.355  23.688  32.739  36.982  44.053
  50.063  55.296  63.003  66.397  75.802  77.499  83.439  87.611  89.308  97.651
 101.823 105.217 109.672 112.784 119.642 122.683 124.097 131.027 134.067  138.31
 143.684 152.099 159.028  167.16 173.665 175.645 182.434  186.04 194.242  196.01
 196.788 215.809 220.334 224.577 230.234 231.365 232.497 238.649 244.518 245.932
 248.619 251.871 253.427 259.791  267.64 268.347 276.832 278.105 287.297 290.974
 296.278 301.015 306.319 315.794  317.35 321.309 323.784 324.774 331.421 338.987
 339.411 341.038 348.604 349.664 351.291 358.432 363.311 367.837 370.665 386.646
 387.141 387.777 395.838 407.011  411.96 415.708 421.294 422.355 423.416 429.638
  435.79 436.709 438.336 447.599 695.086 695.086 706.046 707.177 711.279 715.168
 718.067 724.077 728.461 736.169 743.452 747.129 750.806 751.584 761.342 766.292
 769.403 774.635 781.282 788.212 789.485 794.788 799.526 801.152  802.99 809.142
  814.87 817.415 823.355 827.174 833.608 836.719 838.558 843.578 846.477 852.488
 861.751  862.67 864.933 869.458 871.226 893.076 894.207 894.844 902.198 909.622
 910.471 911.319 917.612 919.027 927.936 934.795 937.199  942.29 943.775 944.482
 955.584 959.473 963.362 968.171 969.514 970.999 973.545
     929   928.9   928.4   928.2   927.8   927.8   927.5   926.8   926.3   925.7
   922.7   922.6   920.3   919.4   919.3   918.1   918.3   918.9   919.2   919.8
   920.7   921.9   923.6   924.7   926.7   927.1   927.8   928.3   928.4   928.6
   928.3     928   928.1   927.9   928.2   928.2   928.2   928.2   928.2   928.3
   928.6   928.7   928.6   928.8   929.3   929.4   929.2   929.3     930   930.1
   930.1   930.3   930.6   930.6   930.9     931     931   931.3   931.4   931.5
   931.7   932.1     932     932   932.3   932.3   932.7   932.8   933.7   933.8
   933.8   933.9   934.2   934.7   934.8     935   935.1   935.1   935.7   935.8
   935.8   935.9   936.4   936.4   936.5   937.1   937.3   937.6     938   938.4
   938.4   938.5   939.1   939.9   939.9   939.8     940     940     940   940.4
   940.7   940.7   940.9     944     952     952   954.5   954.5   954.7     955
   955.1   955.4   955.6     956   956.5   956.8   957.2   957.2   957.2   957.5
   957.7   958.4   958.8   959.1   959.2   959.1   959.4   959.5   959.6     960
   960.3   960.4   960.6   960.9   961.2   961.4   961.5   961.7   961.8   962.1
     963   963.1   963.1   963.1   963.2   964.3   964.4   964.4   964.9   965.1
   965.1   965.1   965.4   965.5     966   966.6   966.9   966.9     967     967
   967.4   967.7   967.9   968.5   968.6   968.6   968.6
                                                                                
                                                                                
                                                                                
                                                                                
                                                                                
                                                                                
                                                                                
                                                                                
                                                                                
                                                                                
                             940     948
                                                                                
                                                                                
                                                                                
                                                                                
                                                                                
                                                        
   21.85  25.668  31.537  36.699  43.699    47.8   55.72  58.761  68.094  70.074
  80.469  81.317  89.378  92.631  93.126 104.015 106.349   115.4 119.572 126.714
 132.724 137.957 145.664 149.058 158.463  160.16 166.099 170.271 171.968 180.242
 184.484 187.878 192.262 195.374 202.233 205.344 206.687 213.617 216.658   220.9
 226.345 234.689 241.689 249.821 256.255 258.306 265.094 268.701 276.903   278.6
 279.378  298.47 302.925 307.167 312.895 314.026 315.158 321.309 327.178 328.522
  331.28 334.461 336.088 342.452 350.301 350.937 359.493 360.766 369.888 373.564
 378.939 383.605 388.979 398.384  399.94 403.899 406.374 407.435 414.011 421.577
 422.072 423.628 431.264 432.325 433.881 441.022 445.972 450.498 453.326 469.307
 469.731 470.367 478.428 489.601 494.551 498.369 503.955 504.945 506.076 512.299
  518.38 519.299 520.996 525.946 533.159 780.646 780.646 788.707 789.838  793.94
 797.758 800.728 806.738 811.122  818.83 826.113 829.719 833.396 834.245 844.003
 848.952 852.064 857.296 863.943 870.873 872.146 877.378 882.186 883.813 885.581
 891.803  897.46 900.006 905.945 909.834 916.269  919.38 921.219 926.239 929.068
 935.149 944.412  945.26 947.594 952.049 953.816 975.666 976.797 977.434 984.788
 992.283 993.131  993.981000.2031001.6871010.5261017.3851019.7891024.8811026.436
1027.1431038.1741042.1341045.9521050.7611052.175 1053.661056.205
     929   928.9   928.4   928.2   927.8   927.8   927.5   926.8   926.3   925.7
   922.7   922.6   920.3   919.4   919.3   918.1   918.3   918.9   919.2   919.8
   920.7   921.9   923.6   924.7   926.7   927.1   927.8   928.3   928.4   928.6
   928.3     928   928.1   927.9   928.2   928.2   928.2   928.2   928.2   928.3
   928.6   928.7   928.6   928.8   929.3   929.4   929.2   929.3     930   930.1
   930.1   930.3   930.6   930.6   930.9     931     931   931.3   931.4   931.5
   931.7   932.1     932     932   932.3   932.3   932.7   932.8   933.7   933.8
   933.8   933.9   934.2   934.7   934.8     935   935.1   935.1   935.7   935.8
   935.8   935.9   936.4   936.4   936.5   937.1   937.3   937.6     938   938.4
   938.4   938.5   939.1   939.9   939.9   939.8     940     940     940   940.4
   940.7   940.7   940.9   941.5     944     952     952   954.5   954.5   954.7
     955   955.1   955.4   955.6     956   956.5   956.8   957.2   957.2   957.2
   957.5   957.7   958.4   958.8   959.1   959.2   959.1   959.4   959.5   959.6
     960   960.3   960.4   960.6   960.9   961.2   961.4   961.5   961.7   961.8
   962.1     963   963.1   963.1   963.1   963.2   964.3   964.4   964.4   964.9
   965.1   965.1   965.1   965.4   965.5     966   966.6   966.9   966.9     967
     967   967.4   967.7   967.9   968.5   968.6   968.6   968.6
                                                                                
                                                                                
                                                                                
                                                                                
                                                                                
                                                                                
                                                                                
                                                                                
                                                                                
                                                                                
                                     940     948
                                                                                
                                                                                
                                                                                
                                                                                
                                                                                
                                                                
Pier Skew, UpSta & Num, DnSta & Num=  ,511.238, 2 ,596.798, 2 , 0 , 0 , 0 ,,
       3       3
   917.3     948
       3       3
   917.3     948
Pier Skew, UpSta & Num, DnSta & Num=  ,574.878, 2 ,660.438, 2 , 0 , 0 , 0 ,,
       3       3
   915.1     948
       3       3
   915.1     948
Pier Skew, UpSta & Num, DnSta & Num=  ,638.517, 2 ,724.077, 2 , 0 , 0 , 0 ,,
       3       3
     918     948
       3       3
     918     948
BR Coef=-1 , 1 , 0 ,, 0 ,,,0.8,0,1.2,0,
WSPro=,,,, 1 ,,,, 0 ,,,, 0 ,,,,-1 ,-1 ,-1 , 0 , 0 , 0 , 0 , 0
BC Design=,, 0 ,, 0 ,,,,,,

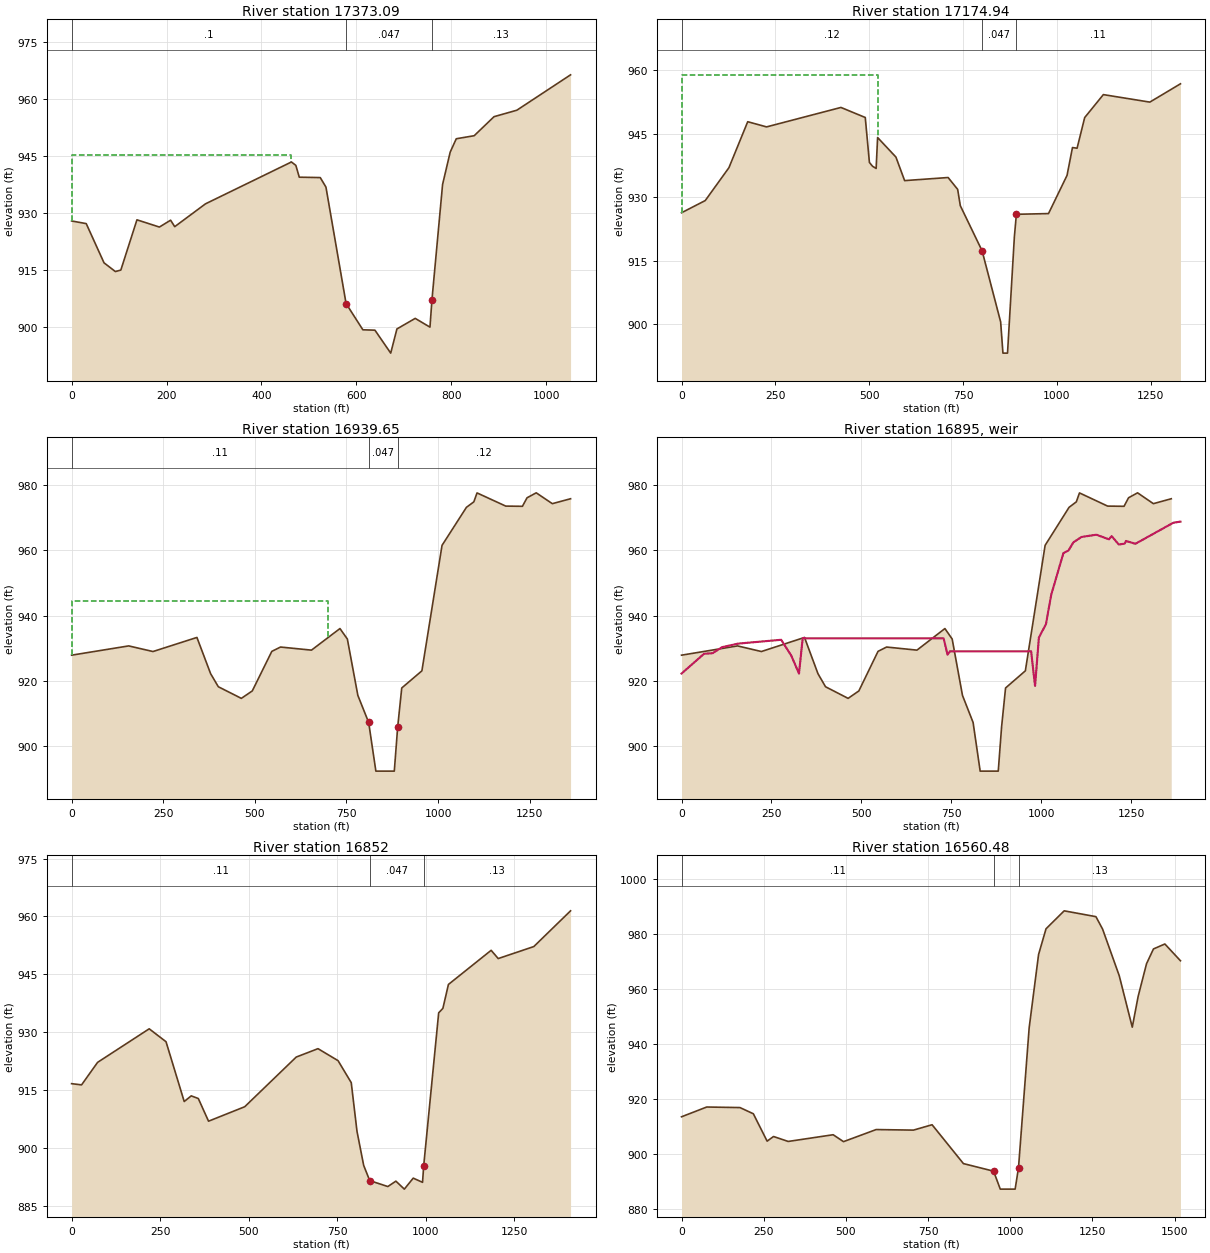
Type RM Length L Ch R = 1 ,17373.09,198.15,198.15,251.7
BEGIN DESCRIPTION:
Down stream xs of Bridge 37003-0070
END DESCRIPTION:
XS GIS Cut Line= 4
  1352702.389371   772588.499933  1352852.606971   772396.221405
  1352879.572859   772381.269981  1352939.108091    771170.52694
#Sta/Elev= 30
       0   927.9   30.83   927.2  68.307   916.9  92.277   914.6 103.733     915
 137.674   928.2 184.979   926.3 208.596   928.1 217.294   926.4 282.136   932.4
 463.296   943.4 472.559   942.5 479.772   939.4 523.966   939.3 535.987   936.8
 578.413   906.2 613.769   899.3 639.225   899.2  672.47  893.17  685.53  899.52
 724.077   902.3  755.19     900  759.41  907.24 781.777   937.5 797.829     946
 810.627   949.5 848.387   950.3 890.177   955.3  938.26     9571051.468   966.3
#Mann= 3 , 0 , 0
       0      .1       0 578.413    .047       0  759.41     .13       0
#XS Ineff= 2 , 0
       0  461.62  945.36 800.162       0     937
Permanent Ineff=
       F       F
Bank Sta=578.413,759.41
Skew Angle= 45
Exp/Cntr=0.5,0.3

Type RM Length L Ch R = 1 ,17174.94,235.29,235.29,192.59
XS GIS Cut Line= 4
  1352861.056763   772422.321757  1353096.209915   772101.711452
  1353130.926843   771778.576732  1352968.070139   771194.428508
#Sta/Elev= 30
       0  926.29   63.18  929.17   126.3  936.93  176.34  947.78  226.57  946.56
  424.64  951.15  489.44  948.78   500.5  938.17  508.81  937.27  518.41  936.75
   522.3  944.05  571.07  939.44   594.3  933.88  710.14  934.61  735.54  931.81
  742.62  927.96  800.67   917.3  850.05  900.53  856.15  893.16  868.34  893.16
  886.62  920.64  891.99  925.93  977.57   926.1 1026.87  935.11 1041.37  941.68
 1053.65  941.53 1073.91  948.76 1123.61  954.18 1247.46  952.41 1329.02  956.73
#Mann= 3 , 0 , 0
       0     .12       0  800.67    .047       0  891.99     .11       0
#XS Ineff= 2 , 0
          524.05  958.85
Permanent Ineff=
       F       F
Bank Sta=800.67,891.99
Exp/Cntr=0.5,0.3

Type RM Length L Ch R = 1 ,16939.65,87.65,87.65,100.92
XS GIS Cut Line= 4
  1353040.128635   772344.730205  1353273.466619    771829.65078
  1353326.498555   771691.581788  1353245.872251   771048.490587
#Sta/Elev= 30
       0  927.81  155.73  930.66  222.04  928.93  341.95  933.26   379.3  922.13
  400.34  918.11  463.12  914.54  492.98  916.82   546.3  928.98  570.05  930.31
  654.52  929.36  732.25  935.99  752.45  932.77  781.07  915.45  810.58  907.14
  830.25  892.18  880.52  892.18  889.79  905.78  900.84  917.73  955.85     923
 1010.79  961.56 1077.36  973.24 1097.54  974.93 1106.34  977.67 1184.62  973.62
 1230.18  973.56 1242.77  976.18 1267.82   977.7 1311.73  974.37  1361.5  975.88
#Mann= 3 , 0 , 0
       0     .11       0  810.58    .047       0  889.79     .12       0
#XS Ineff= 2 , 0
          700.76  944.43
Permanent Ineff=
       F       F
Bank Sta=810.58,889.79
Exp/Cntr=0.5,0.3

Type RM Length L Ch R = 5 ,16895   ,,,
BEGIN DESCRIPTION:
Millersville Dam
END DESCRIPTION:
IW Pilot Flow=0
#Inline Weir SE= 30
       0  922.16   62.74  928.25   86.21  928.41  112.52  930.27  156.95  931.36
  277.05  932.54  305.06  927.68  326.55  922.17  336.83     933  728.55     933
   739.6  927.95  746.25     929  971.85     929  982.85  918.37  993.51  933.24
 1013.03  937.32 1028.02  946.47 1061.54  959.15 1076.02  960.02 1089.54  962.52
  1112.2  964.14 1153.18  964.83 1188.46   963.4  1195.6  964.41 1215.55  961.82
 1231.82  962.08 1235.63  962.91 1261.83  962.04 1367.25  968.51 1387.07  968.85
IW Dist,WD,Coef,Skew,MaxSub,Min_El,Is_Ogee,SpillHt,DesHd
77,10,2.6,0,0.95,, 0 ,,,0,0,

Type RM Length L Ch R = 1 ,16852   ,291.52,291.52,165.78
XS GIS Cut Line= 4
  1353066.763771   772357.717341  1353327.253883   771861.149532
  1353408.686972    771704.04118  1353325.250811   771038.538587
#Sta/Elev= 30
       0  916.64   28.09  916.33   73.37  922.17  219.03  930.87  266.52  927.52
  317.85  912.01  337.63  913.48  357.66  912.79  386.51  906.91  488.66  910.66
  634.03  923.54  695.47  925.72  752.12  922.61  789.37   916.9  805.58  904.28
  824.41  895.45  841.51   891.5  892.62  889.96  915.37  891.36   939.2  889.29
   964.3  892.14   990.6  891.05  993.87  895.36 1036.14  935.01 1048.01  936.17
 1063.66  942.37 1184.25  951.23 1204.16  949.09 1304.69   952.2 1408.42  961.47
#Mann= 3 , 0 , 0
       0     .11       0  841.51    .047       0  993.87     .13       0
#XS Ineff= 2 , 0
       0  672.03     905               0
Permanent Ineff=
       F       F
Bank Sta=841.51,993.87
Exp/Cntr=0.5,0.3

Type RM Length L Ch R = 1 ,16560.48,578.74,578.74,597.21
XS GIS Cut Line= 4
  1353085.341563   772339.139421  1353528.956156   771721.626076
  1353723.075708    771445.61238  1353653.572348   771031.194587
#Sta/Elev= 30
       0  913.67   76.69  917.22  177.77  917.02  218.52  914.77  260.45  904.82
  279.95  906.51  324.56  904.71  461.33  907.15  492.89  904.64  592.15  909.03
  705.69  908.83  762.33  910.78  857.67  896.67  949.47  893.91  969.78  887.39
 1015.02  887.39 1025.23  895.15 1057.64  945.97 1086.34  972.65 1108.94  981.97
 1164.21   988.5 1260.78  986.38 1281.08  981.86 1331.74  964.92 1371.36  946.23
 1389.25  957.41 1414.78  969.29 1435.86  974.65 1470.55  976.45 1517.99  970.36
#Mann= 3 , 0 , 0
       0     .11       0  949.47    .047       0 1025.23     .13       0
#Block Obstruct= 2 , 0
          813.06  925.47
Bank Sta=949.47,1025.23
Exp/Cntr=0.3,0.1

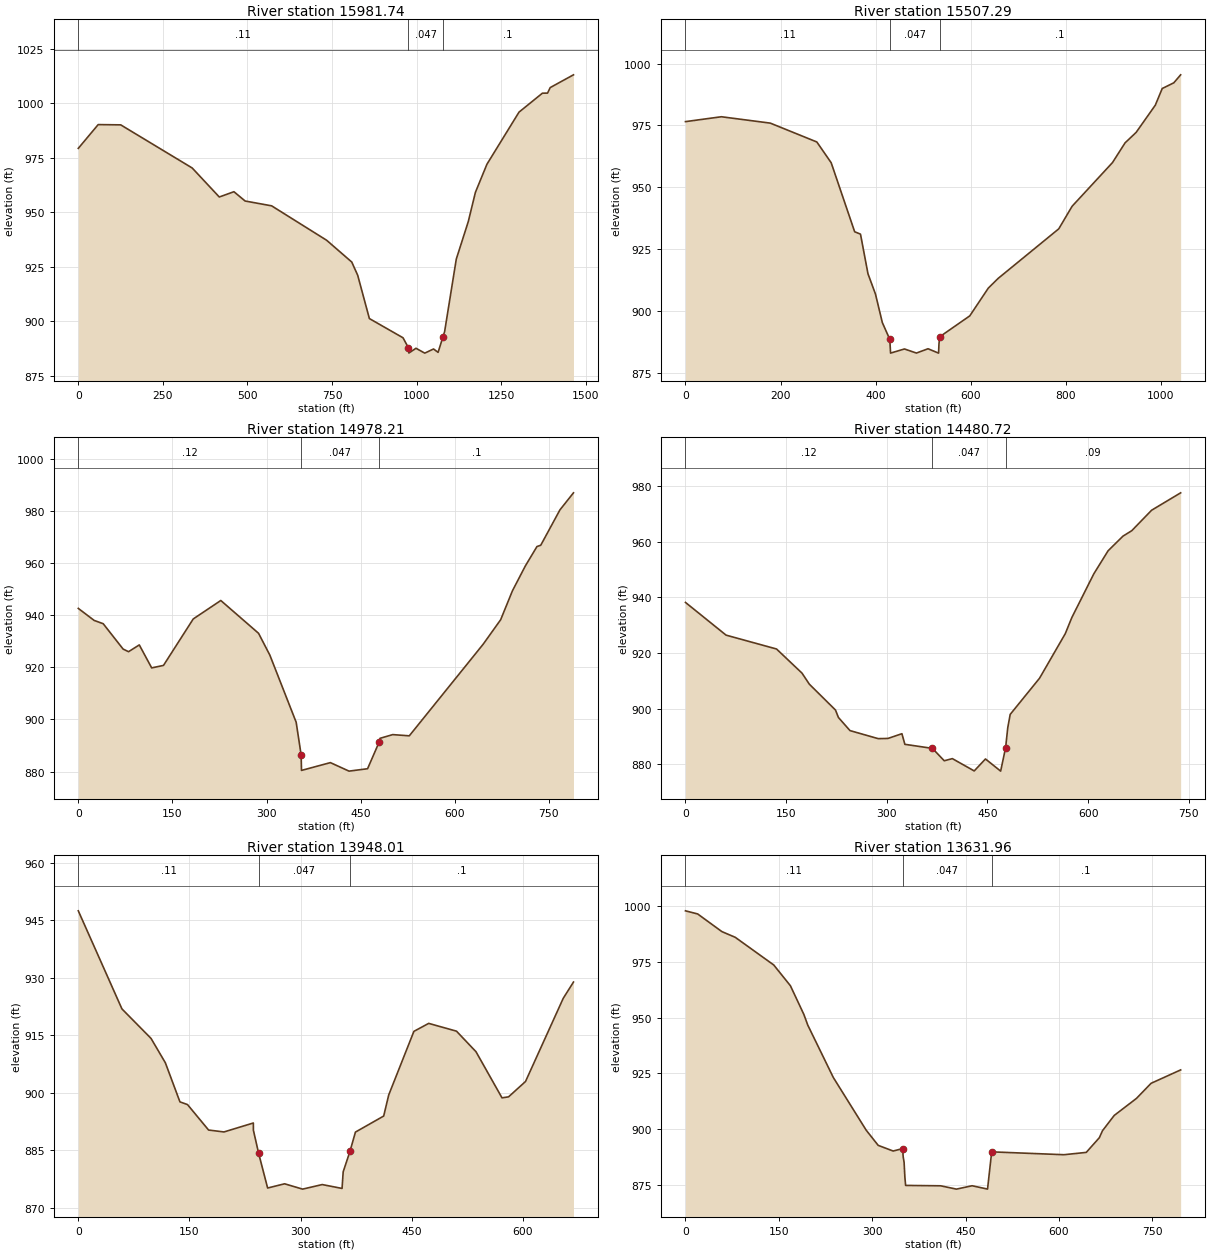
Type RM Length L Ch R = 1 ,15981.74,474.46,474.46,594.67
XS GIS Cut Line= 3
  1353400.912251   772586.717789  1353917.120252   772224.768605
   1354336.34278   771505.103196
#Sta/Elev= 30
       0  979.29   58.77  990.18  125.36  990.06  336.55  970.29  416.66  956.99
  459.93  959.41     493  955.15  571.29  952.94  733.86  937.16  808.14  927.17
  825.68  921.11  860.21  901.25  959.59  892.44  975.15  887.96  976.85  885.45
  997.94  887.63 1023.95  885.41 1049.76  887.31 1063.26  885.76 1077.36  892.73
 1082.52  895.25 1117.01  928.51 1152.56  945.77 1173.51  959.12 1207.58  972.01
 1302.42   995.9 1371.53 1004.58 1386.75 1004.62 1394.63 1007.16 1463.32    1013
#Mann= 3 , 0 , 0
       0     .11       0  975.15    .047       0 1077.36      .1       0
#Block Obstruct= 2 , 0
          793.91  943.78
Bank Sta=975.15,1077.36
Exp/Cntr=0.3,0.1

Type RM Length L Ch R = 1 ,15507.29,529.08,529.08,679.16
XS GIS Cut Line= 2
  1354575.926141   772538.957277  1354500.405245   771499.894748
#Sta/Elev= 30
       0  976.55   75.53  978.52  178.49  975.94  276.36  968.32  306.57  959.91
  355.93  932.01  368.21  931.04  383.96  915.01  399.69  906.82  414.18  895.26
  429.88  888.46  431.47  882.92  460.65  884.59  485.93  882.94  510.31  884.68
  532.48  882.91  533.32  886.65  534.77  889.51  598.07  897.97  637.13  909.21
  657.98  913.16  785.38  933.19  813.42  942.31  898.41  959.99  924.86  967.96
  948.11  972.19   988.5  983.21 1003.01  989.94 1027.38  992.25  1041.8  995.48
#Mann= 3 , 0 , 0
       0     .11       0  429.88    .047       0  534.77      .1       0
Bank Sta=429.88,534.77
Exp/Cntr=0.3,0.1

Type RM Length L Ch R = 1 ,14978.21,497.49,497.49,503.35
XS GIS Cut Line= 2
  1355187.905277   771976.457308  1354583.738621   771468.644828
#Sta/Elev= 30
       0  942.57   25.27  937.96   39.69   936.7   71.44  926.97    80.1  925.97
   97.21  928.57  116.95  919.76  135.78  920.71   183.2  938.52  227.13   945.6
  287.29  933.03  305.34  924.64  347.27  898.91  355.17   886.4  355.75  880.45
  401.78  883.44   431.5  880.18  461.06   881.1  479.77  891.46  480.95  892.76
  501.14  894.18  527.55  893.71  645.38  928.86  673.17  938.22  691.94  949.31
  712.37  958.78  731.03  966.28  737.09  966.79   767.7  980.36  789.23  986.88
#Mann= 3 , 0 , 0
       0     .12       0  355.17    .047       0  479.77      .1       0
#Block Obstruct= 2 , 0
           354.3  885.42
Bank Sta=355.17,479.77
Exp/Cntr=0.3,0.1

Type RM Length L Ch R = 1 ,14480.72,532.7,532.7,520.82
XS GIS Cut Line= 2
  1355471.759485   771585.832284  1354919.676157   771096.248924
#Sta/Elev= 30
       0  938.12   60.48  926.37   135.7  921.39  173.65  912.72  184.58  908.75
  223.56  899.46   227.9   896.8  245.13  892.08  287.13  889.19  301.71  889.26
  322.53  890.96   326.9  887.15  367.98  885.69  385.61  881.24  397.69  882.01
  430.27  877.59  447.02  881.89  469.67  877.52  477.04  885.94  480.26  893.14
  483.86  897.89  527.63   910.9  566.01  926.92  575.62  932.63  608.44  948.37
  629.76  956.67  651.96  961.93  665.04  963.89  694.62  971.24  737.89  977.49
#Mann= 3 , 0 , 0
       0     .12       0  367.98    .047       0  477.04     .09       0
Bank Sta=367.98,477.04
Exp/Cntr=0.3,0.1

Type RM Length L Ch R = 1 ,13948.01,316.06,316.06,335.26
XS GIS Cut Line= 2
  1355797.280254   771208.228188  1355325.926141   770734.269787
#Sta/Elev= 30
       0  947.43    58.9  921.84   98.22  914.13  117.55  907.77  137.21  897.58
  147.43  896.87  175.86  890.23  196.66  889.73  236.32  892.07  236.35   890.2
  243.45  884.14  255.58   875.1  278.51   876.2  302.78  874.81  329.29     876
  356.05  874.99  357.57  879.33  366.79   884.7  374.11  889.69  412.25  893.88
  419.04  899.38  453.03  915.98  473.02  918.06  510.51  916.03  536.84  910.67
  571.97  898.63  580.84  898.89  603.72   902.9  654.63   924.6  668.44  928.84
#Mann= 3 , 0 , 0
       0     .11       0  243.45    .047       0  366.79      .1       0
Bank Sta=243.45,366.79
Exp/Cntr=0.3,0.1

Type RM Length L Ch R = 1 ,13631.96,147.91,147.91,165.36
XS GIS Cut Line= 3
  1356142.283518   771051.494875  1355721.275646   770703.774811
  1355523.521789   770551.431003
#Sta/Elev= 30
       0   997.8   19.58   996.4   58.52  988.49   79.97  985.94  141.88  973.54
  168.61  964.25  190.37  951.32  196.51  946.62  237.57  923.15  290.33  899.59
  309.65  892.77  333.71  890.23  348.85  891.32  349.82  887.65  351.29  885.14
  352.56  878.39  353.76  874.83  409.92  874.66   435.4  873.17  460.58  874.68
  485.36  873.19  492.02  889.86  608.14  888.58  643.98  889.62     665  896.19
  670.07  899.32  688.89  906.16  724.73  913.81  748.09  920.55  795.67  926.56
#Mann= 3 , 0 , 0
       0     .11       0  348.85    .047       0  492.02      .1       0
Bank Sta=348.85,492.02
Exp/Cntr=0.5,0.3

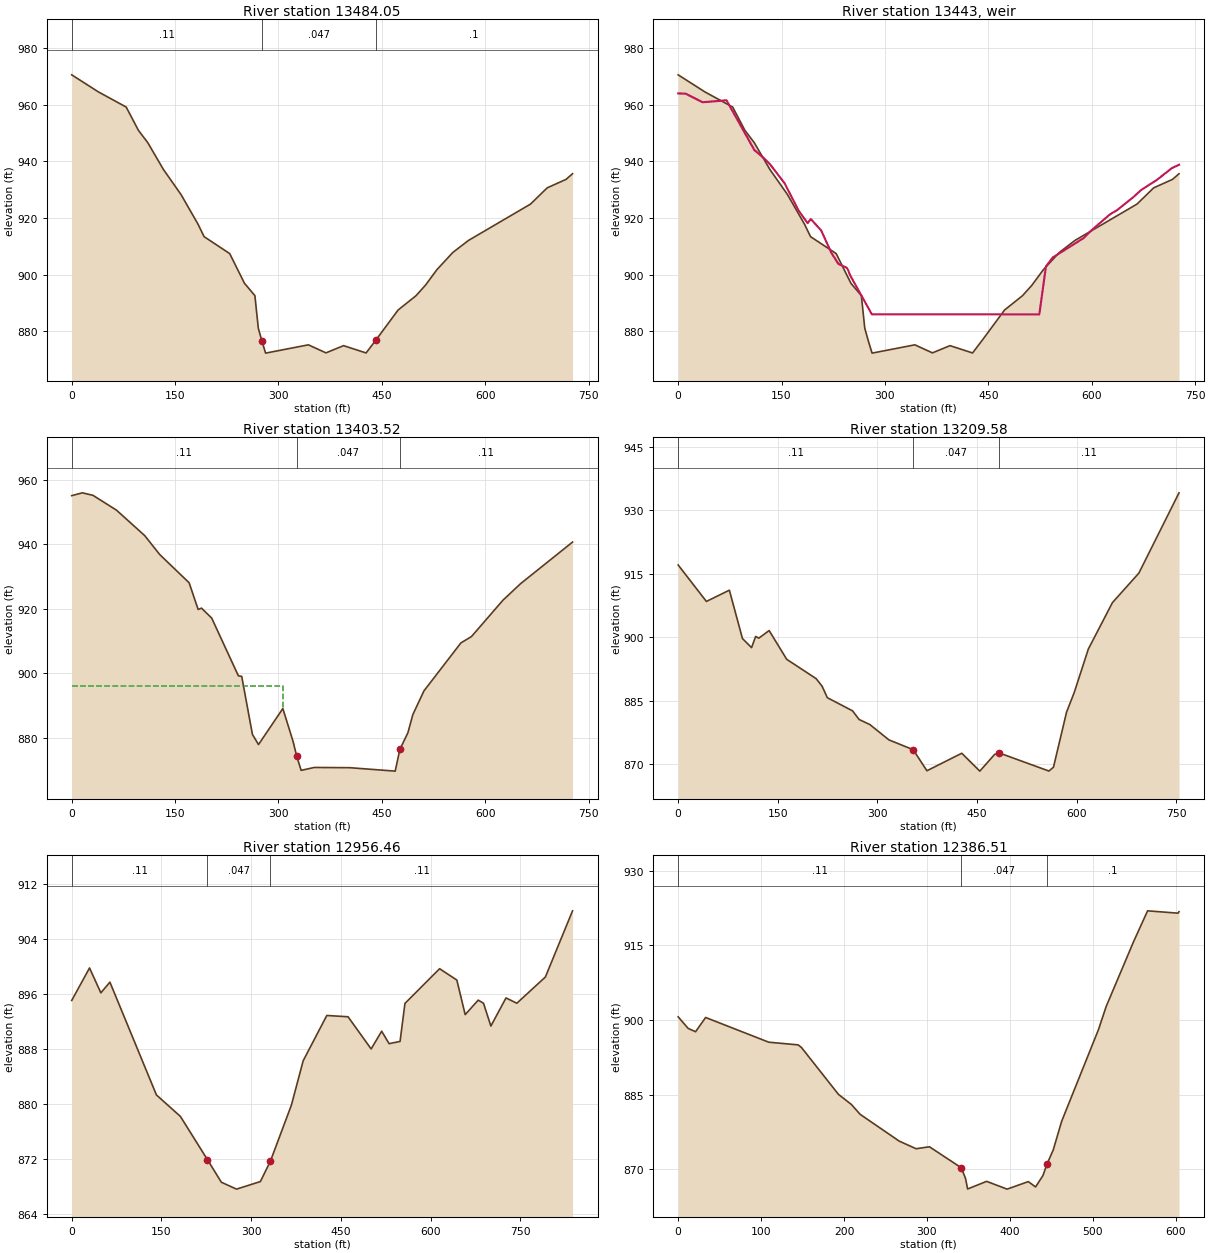
Type RM Length L Ch R = 1 ,13484.05,80.52,80.52,80.3
XS GIS Cut Line= 2
   1356197.82131   770865.005403  1355599.432702   770452.651867
#Sta/Elev= 30
       0  970.56   38.83  964.52   79.08  959.18   96.84  950.95  110.31  946.64
  133.21   937.1  158.62   928.3  183.38   917.8  192.09  913.43  229.27  907.45
  250.67  896.97  265.81  892.61  270.75  881.12  275.95  876.58  281.34  872.31
  343.43  875.24  368.93   872.4  394.45  874.95  427.15  872.37  441.35  876.91
  473.58  887.53  499.53  892.57  513.28  896.29  529.95  901.79  552.97  907.84
   575.6  912.08  665.75  924.93  689.94  930.66  717.28  933.65  726.71  935.65
#Mann= 3 , 0 , 0
       0     .11       0  275.95    .047       0  441.35      .1       0
Bank Sta=275.95,441.35
Exp/Cntr=0.5,0.3

Type RM Length L Ch R = 5 ,13443   ,,,
BEGIN DESCRIPTION:
DAM: 37003-0110 - North State Dam
END DESCRIPTION:
IW Pilot Flow=0
#Inline Weir SE= 30
       0     964   10.73  963.91   35.45  960.88   70.15  961.57  110.51  944.02
  124.01  941.23  133.77  938.82  154.39  932.29  174.59  922.68  187.85  918.18
  192.42  919.65  207.51  915.61  222.25  907.72  232.46   903.8  244.49  902.48
  246.43  901.68  249.66  899.72  281.05     886  524.01     886  533.61  902.89
  543.57  906.09  587.98  912.87  598.67  915.45  626.88  921.37  636.64  922.76
  659.83  927.26  671.58  929.86  694.99  933.54  716.47  937.64  726.71  938.81
IW Dist,WD,Coef,Skew,MaxSub,Min_El,Is_Ogee,SpillHt,DesHd
70,10,2.6,0,0.95,, 0 ,,,0,0,

Type RM Length L Ch R = 1 ,13403.52,193.94,193.94,190.03
XS GIS Cut Line= 2
  1356243.215486   770799.131483  1355644.826878   770386.777947
#Sta/Elev= 30
       0  955.15   15.36  956.03   30.88  955.25   64.94  950.65  105.93  942.74
  127.83  936.83  170.39  928.08  183.46  919.79  188.35   920.2   203.1  917.12
  241.83  899.18  246.68     899  262.25  880.95  271.04  877.81  306.34  889.01
   321.2  878.79  326.45  874.21  332.92  869.79  351.87   870.7  403.19  870.63
  469.37  869.56  476.15   876.3  487.86  881.51   494.9  887.08  511.09  894.49
  564.72   909.4  580.04  911.37  625.75  922.67  651.27   927.8  726.71  940.73
#Mann= 3 , 0 , 0
       0     .11       0  326.45    .047       0  476.15     .11       0
#XS Ineff= 2 , 0
          306.27  896.05
Permanent Ineff=
       F       F
Bank Sta=326.45,476.15
Exp/Cntr=0.5,0.3

Type RM Length L Ch R = 1 ,13209.58,253.12,253.12,214.49
XS GIS Cut Line= 2
  1356399.961726   770692.542171  1355793.150206   770244.299995
#Sta/Elev= 30
       0  917.09   42.51  908.47   77.11  911.13   96.87  899.68  110.57  897.54
  116.71  900.19  121.53  899.79  137.03  901.58  163.49  894.78   207.8  890.21
  216.78  888.42   224.7   885.7  262.66  882.59   272.6  880.54  288.71  879.35
  317.46  875.72  353.99   873.4  374.67  868.42   427.2  872.56  454.34  868.33
  476.59  872.27  483.61  872.63  558.45  868.35  565.32  869.27  585.02  882.28
  596.62  886.95   617.8   897.2  654.11  908.19     694  915.18  754.41  934.16
#Mann= 3 , 0 , 0
       0     .11       0  353.99    .047       0  483.61     .11       0
Bank Sta=353.99,483.61
Exp/Cntr=0.3,0.1

Type RM Length L Ch R = 1 ,12956.46,569.95,569.95,424.23
XS GIS Cut Line= 3
  1356424.497918   770471.350747  1356128.780542   770158.959579
   1355942.74931   769797.007578
#Sta/Elev= 30
       0  895.11   29.79  899.84    48.7  896.22   63.84  897.78  141.61  881.37
  181.65  878.25  226.94  871.95  250.15  868.67  275.47  867.67  315.36  868.77
   332.1  871.74   367.2  879.89  386.87  886.34  426.39  892.93  461.88  892.74
  500.49  888.06  518.07  890.64  530.52  888.83   548.8  889.15     557  894.68
  614.91  899.73  643.72  898.08   657.7  893.05  679.45  895.16  688.27  894.71
  700.62  891.39  725.89  895.48  744.01  894.71  791.69  898.52  837.12  908.15
#Mann= 3 , 0 , 0
       0     .11       0  226.94    .047       0   332.1     .11       0
Bank Sta=226.94,332.1
Exp/Cntr=0.3,0.1

Type RM Length L Ch R = 1 ,12386.51,350.84,350.84,309.95
XS GIS Cut Line= 2
  1356717.466623   770379.065563  1356694.029183   769775.549914
#Sta/Elev= 30
       0  900.63   12.02  898.31   20.98  897.64   33.12   900.5  109.22  895.54
  144.68     895   148.6  894.49   193.3  885.06  208.88  883.03  219.46  881.05
  266.58  875.67  286.97  874.14  302.98  874.54   341.4  870.32  346.58  868.15
  349.03  866.06  371.97  867.59  396.67  866.03  422.21  867.54     431  866.47
  439.82  868.74  444.93  871.12  452.33  873.92  462.39  879.63  506.96  898.11
  516.08  902.69  549.15  915.72  566.09  921.92  602.74  921.45  603.97  921.74
#Mann= 3 , 0 , 0
       0     .11       0   341.4    .047       0  444.93      .1       0
Bank Sta=341.4,444.93
Exp/Cntr=0.3,0.1

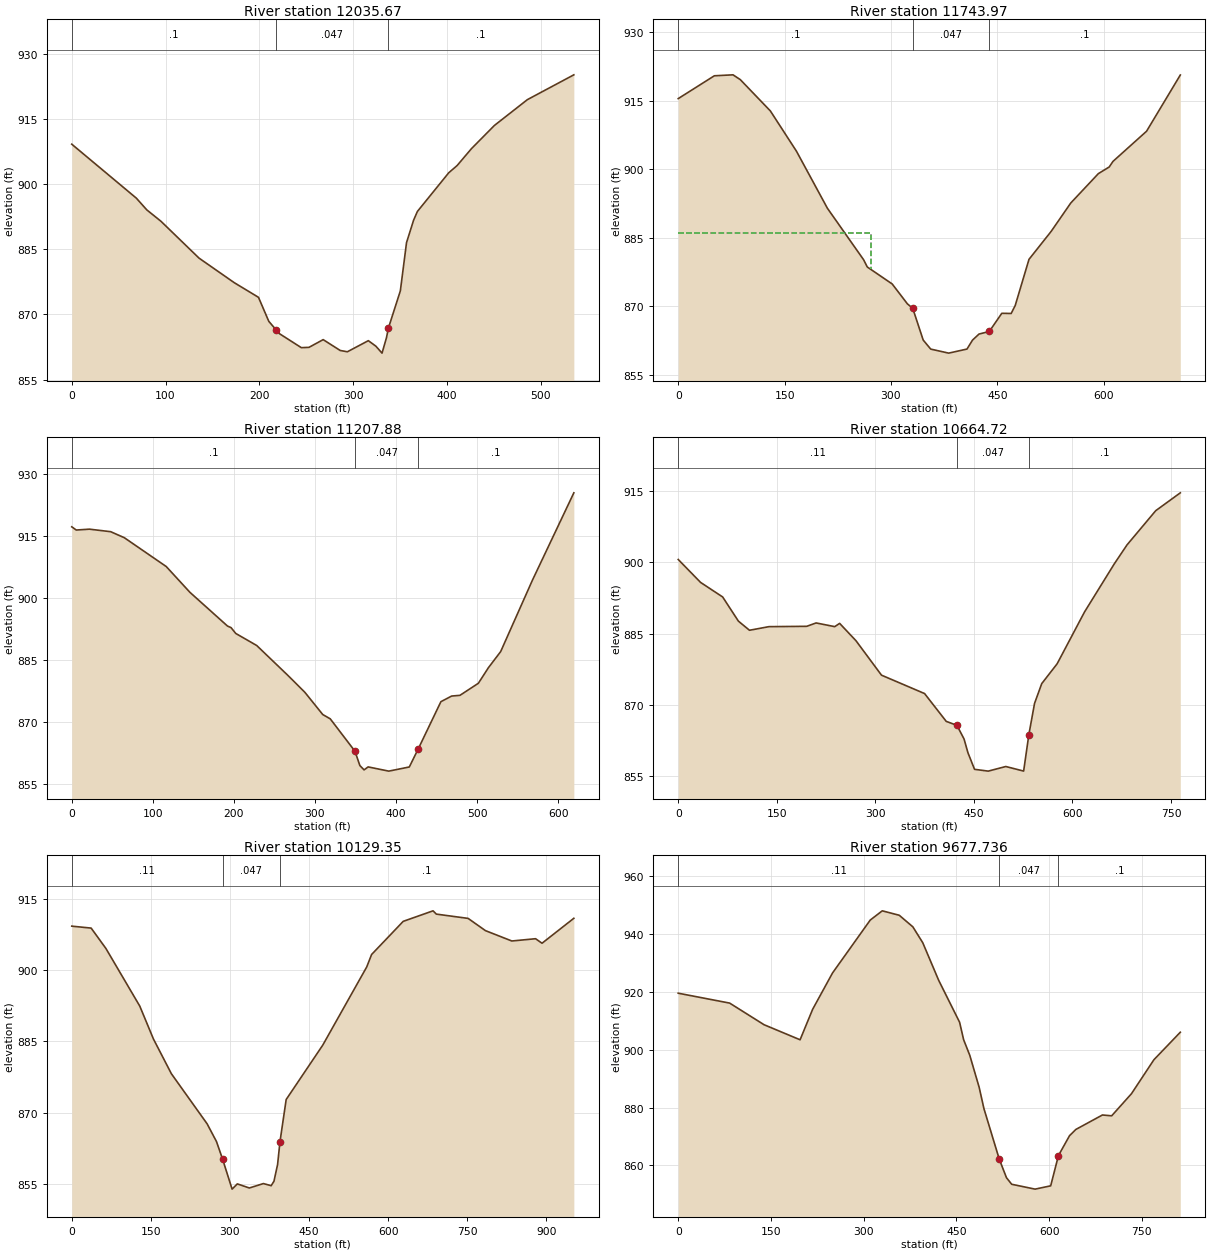
Type RM Length L Ch R = 1 ,12035.67,291.69,291.69,316.67
XS GIS Cut Line= 2
  1356988.462719   770349.768667  1357071.958911    769820.96009
#Sta/Elev= 30
       0  909.24   68.81  896.81      80   894.1   95.08  891.48  135.69  882.98
  173.25  877.32  199.11  873.94  210.11   868.4  217.89  866.45  220.91  865.64
  244.77  862.34  252.91  862.41  268.07  864.19  286.24  861.69  293.86  861.39
  316.23  863.95  324.27  862.68  330.82  861.08  335.53   864.6  337.64  866.86
  350.36  875.43  356.95  886.55  364.48  891.72  368.56  893.74  401.99  902.66
  410.88  904.31  426.13   908.2  450.62  913.55  485.82  919.51  535.36  925.23
#Mann= 3 , 0 , 0
       0      .1       0  217.89    .047       0  337.64      .1       0
Bank Sta=217.89,337.64
Exp/Cntr=0.3,0.1

Type RM Length L Ch R = 1 ,11743.97,536.1,536.1,601.8
XS GIS Cut Line= 2
  1357305.630335   770506.757083  1357328.306559   769798.987354
#Sta/Elev= 30
       0  915.43   50.92  920.42   77.24  920.63   87.53  919.58  129.96  912.73
  166.74  903.93   210.4  891.45  261.42   880.2  266.63  878.61  301.73   874.9
  323.25  870.54  330.74  869.57  345.49  862.63  356.11  860.65  381.46  859.77
  407.26  860.66  415.08  862.62  424.23  863.94   438.7   864.5  456.35  868.48
  469.58  868.44  475.27  870.18  494.72  880.28  525.96  886.39  553.64   892.6
  592.53  899.02  607.88  900.48  613.18   901.7  660.51  908.29  708.13  920.59
#Mann= 3 , 0 , 0
       0      .1       0  330.74    .047       0   438.7      .1       0
#XS Ineff= 2 , 0
           271.6  886.11
Permanent Ineff=
       F       F
Bank Sta=330.74,438.7
Exp/Cntr=0.3,0.1

Type RM Length L Ch R = 1 ,11207.88,543.16,543.16,357.06
XS GIS Cut Line= 2
   1357949.99936   770401.609051   1357768.70912   769809.268442
#Sta/Elev= 30
       0  917.18    5.53   916.4   21.77  916.61   48.01     916   64.81  914.55
  116.57  907.58  145.84  901.34  192.09  893.21  196.52  892.82   202.3  891.42
   228.2   888.5  267.02  881.21  287.57   877.2  309.64  871.83  318.93  870.78
   349.4  862.96  355.47  859.49  360.64  858.45  365.66  859.17   391.1  858.15
  416.44  859.15   427.3  863.45  455.44  874.93  468.71  876.29  478.93  876.46
  501.69  879.38  514.03  883.13  529.18  887.03  568.34  904.27  619.46  925.39
#Mann= 3 , 0 , 0
       0      .1       0   349.4    .047       0   427.3      .1       0
Bank Sta=349.4,427.3
Exp/Cntr=0.3,0.1

Type RM Length L Ch R = 1 ,10664.72,535.37,535.37,634.7
XS GIS Cut Line= 2
  1358084.681344   770371.768411   1358529.12576   769750.240602
#Sta/Elev= 30
       0   900.6   33.95  895.79   67.62  892.72   91.56  887.64  108.44  885.72
  138.12  886.48  195.59  886.55  209.83  887.26  238.16  886.48  245.63  887.17
   270.5  883.52  309.33  876.28   374.9  872.41  407.87  866.56  424.11  865.73
  434.97  862.86  440.93  859.95  450.95  856.48  471.72   856.1  498.51  857.07
  525.66  856.11  533.62  863.79  542.24  870.33   553.2   874.5  576.63  878.67
  618.37  889.58  663.56  899.67  682.93  903.66  726.64  910.86  764.09  914.62
#Mann= 3 , 0 , 0
       0     .11       0  424.11    .047       0  533.62      .1       0
Bank Sta=424.11,533.62
Exp/Cntr=0.3,0.1

Type RM Length L Ch R = 1 ,10129.35,451.61,451.61,776.79
XS GIS Cut Line= 3
  1358690.754176   770688.744155  1358737.459072   770225.935067
  1358605.514624   769757.185114
#Sta/Elev= 30
       0  909.23    36.8  908.82   64.86  904.52  128.97  892.43  154.96   885.5
   188.9  878.22  256.71  867.69  274.42  863.97  286.02  860.27  304.03  853.97
  313.97  855.07  336.76  854.21  363.44  855.14  378.14  854.69  383.44  855.63
  390.31  859.14  394.83  863.92  406.61   872.8  476.05  884.24  559.37  900.66
  568.59  903.27  628.59  910.24  685.13  912.45  691.32  911.76  751.62  910.86
  784.46  908.29  834.58  906.11  879.55  906.59   891.8  905.64  952.13  910.88
#Mann= 3 , 0 , 0
       0     .11       0  286.02    .047       0  394.83      .1       0
Bank Sta=286.02,394.83
Exp/Cntr=0.3,0.1

Type RM Length L Ch R = 1 ,9677.736,530.69,530.69,503.75
XS GIS Cut Line= 3
  1359507.673857   770213.555803  1359295.189377   770082.402011
  1358733.986816   770041.907291
#Sta/Elev= 30
       0  919.54   83.22  916.12  138.82  908.65  197.15  903.44  217.46  913.97
   249.7  926.55  310.63  944.82  330.12  948.02  357.58  946.49  379.62  942.48
  395.63     937  421.38  924.01  455.25   909.5  461.77  903.47  471.68   898.1
  486.92  886.99  494.68   879.6  519.37  862.21  531.11  855.75  539.55  853.49
  577.39  851.81  602.62  852.95  615.19  863.41  633.12  870.28  643.36  872.44
  686.34  877.44   701.3  877.15  733.35   884.8  769.65  896.54  812.36  906.05
#Mann= 3 , 0 , 0
       0     .11       0  519.37    .047       0  615.19      .1       0
Bank Sta=519.37,615.19
Exp/Cntr=0.3,0.1

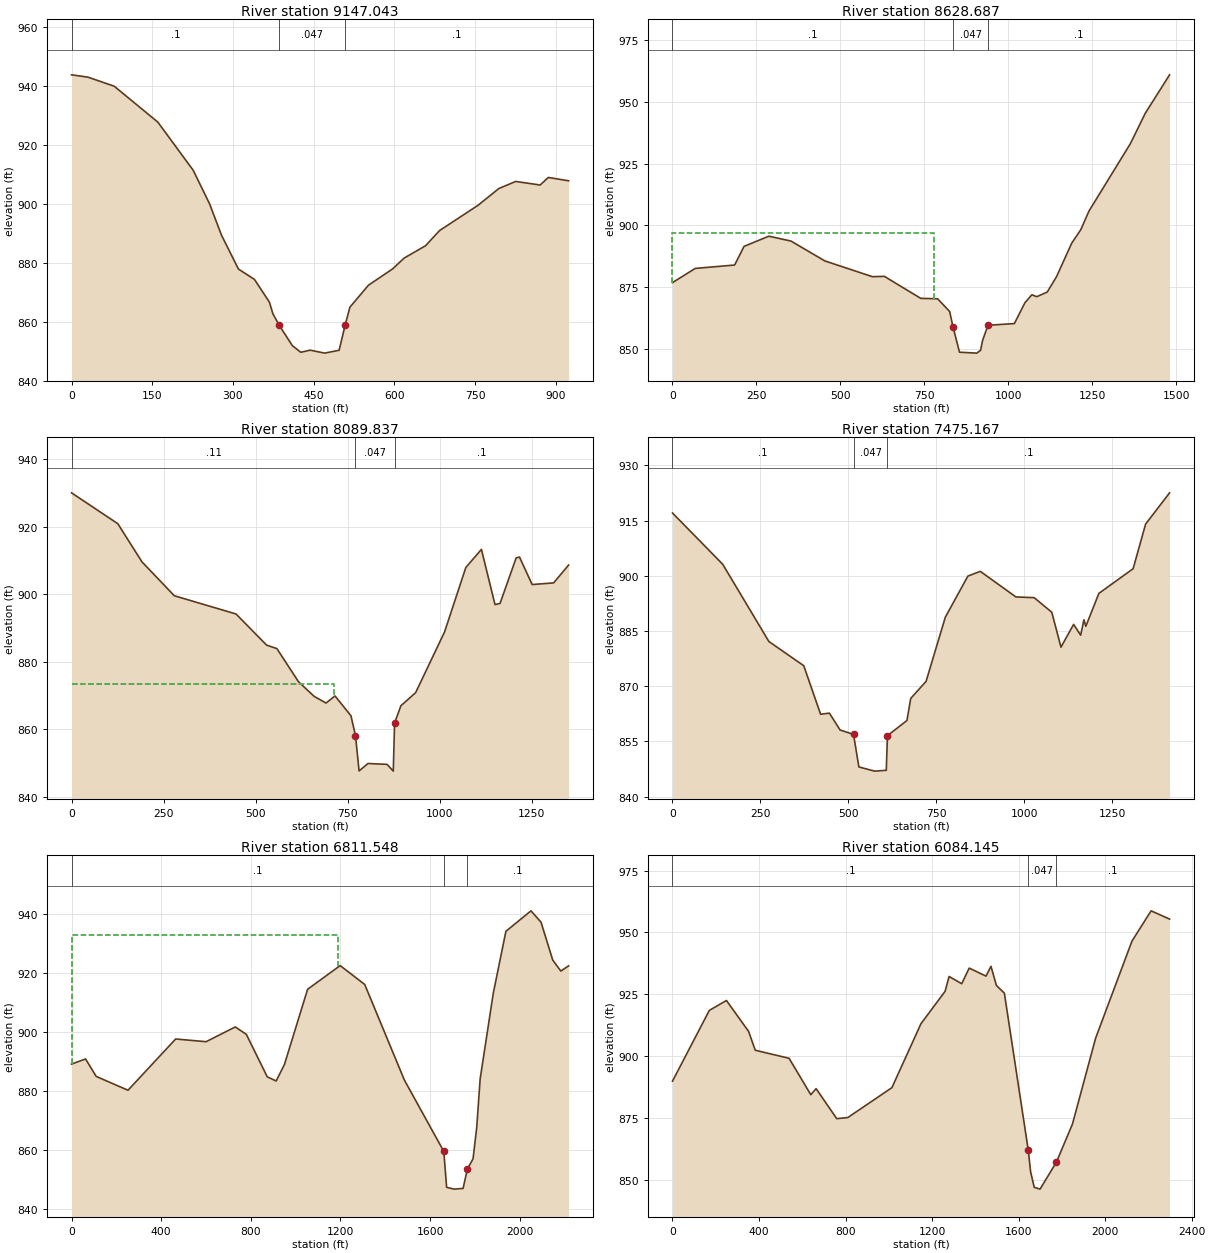
Type RM Length L Ch R = 1 ,9147.043,518.36,518.36,485.22
XS GIS Cut Line= 2
  1359411.070209    769621.76841  1358504.820096    769441.21289
#Sta/Elev= 30
       0  943.82   30.79  943.02   79.48  939.94  160.43  927.77  226.27   911.4
  256.68  900.01  278.71  889.41  310.29  877.87  340.04  874.37   367.9  866.64
  374.39  862.68  386.24  858.74  410.45  851.89  426.13  849.62  443.73  850.34
  470.62  849.33   497.5  850.31  508.68  858.87  517.55  864.94  551.89  872.37
  596.82  877.92  618.43  881.61  658.14  885.79  684.12  890.94  755.64  899.51
  794.38  905.22  825.76  907.62  871.12  906.41  886.38  908.98  924.06  907.84
#Mann= 3 , 0 , 0
       0      .1       0  386.24    .047       0  508.68      .1       0
Bank Sta=386.24,508.68
Exp/Cntr=0.3,0.1

Type RM Length L Ch R = 1 ,8628.687,538.85,538.85,526.86
XS GIS Cut Line= 4
  1359662.491905   769670.126938  1359539.647233   769437.790298
  1359261.911681   769103.973466  1358525.653504   768835.330393
#Sta/Elev= 30
       0  876.84   67.69  882.59  185.17  883.96  213.15  891.51  286.97  895.63
  352.87  893.67  453.73  885.63  595.46  879.25  631.26  879.37  739.44  870.48
  789.84   870.3   825.6  865.17  835.99  858.76  855.04  848.68  906.53  848.31
  917.79  849.45  923.66   853.4  939.79  859.58 1018.47  860.27 1049.86  868.69
  1070.6  871.93 1085.15  871.14 1116.35  873.03 1144.08  879.25 1189.12  892.76
 1216.37  898.26 1240.62  905.78 1364.14   933.1  1408.6  945.42  1480.8  960.93
#Mann= 3 , 0 , 0
       0      .1       0  835.99    .047       0  939.79      .1       0
#XS Ineff= 2 , 0
          778.24  896.88
Permanent Ineff=
       F       F
Bank Sta=835.99,939.79
Exp/Cntr=0.3,0.1

Type RM Length L Ch R = 1 ,8089.837,614.67,614.67,620.9
XS GIS Cut Line= 4
  1359897.165186   768881.985241  1359286.280193   768556.847705
  1359043.622401   768464.670297  1358647.688576   768418.981337
#Sta/Elev= 30
       0  930.01  125.75  920.87  191.24  909.59  279.22  899.54  446.91  894.14
  529.79  884.93  557.86  883.89  616.51  874.09     659  869.76  691.28  867.77
  715.66  869.88  758.94  864.02  771.32  858.16  781.08  847.68  805.26  849.88
  857.22  849.62  873.94  847.62   877.5  861.88   894.7  866.98  934.72  870.86
 1013.26  888.83 1071.05  907.91 1113.36  913.27 1150.26  896.92 1163.94  897.26
 1207.71  910.75 1216.86  910.99 1251.12  902.86 1309.53  903.35 1350.16  908.63
#Mann= 3 , 0 , 0
       0     .11       0  771.32    .047       0   877.5      .1       0
#XS Ineff= 2 , 0
          712.92  873.29
Permanent Ineff=
       F       F
Bank Sta=771.32,877.5
Exp/Cntr=0.3,0.1

Type RM Length L Ch R = 1 ,7475.167,663.62,663.62,470.65
XS GIS Cut Line= 3
  1359897.181186   768156.490713  1359189.609473   767859.257944
   1358640.20224   767520.147032
#Sta/Elev= 30
       0  917.04   142.8  903.11  274.04  882.13  373.17  875.56  421.08  862.37
  446.05  862.67  476.39   858.1  514.69   856.9  529.83  848.06   574.5  846.92
  607.75  847.14   611.1  856.55  666.52  860.67  677.32  866.68  720.88   871.3
   775.6  888.73  839.71   899.9  875.01  901.19  976.28  894.24 1028.18  894.04
 1078.28  890.08  1104.4   880.6 1140.33  886.78 1160.33  883.86  1169.6  888.02
  1175.1  886.27 1212.11   895.2 1309.51  901.91 1344.94  914.02  1413.1  922.52
#Mann= 3 , 0 , 0
       0      .1       0  514.69    .047       0   611.1      .1       0
Bank Sta=514.69,611.1
Exp/Cntr=0.3,0.1

Type RM Length L Ch R = 1 ,6811.548,727.4,727.4,859.36
XS GIS Cut Line= 4
  1360994.754947   768833.915609  1359824.264577   767816.212824
  1359883.292418    767479.40732  1359567.320193   767403.018456
#Sta/Elev= 30
       0   889.1   62.74  890.84  110.19  884.93  252.01  880.25  464.69   897.6
  600.58  896.68  730.75  901.68  780.16  899.15  873.37  884.81  913.08  883.38
  950.18  888.99 1053.45  914.42 1198.71  922.44 1308.32  916.06 1485.44  883.68
 1661.02  859.59 1673.84   847.4 1707.44  846.79 1747.28  847.04 1766.43   853.6
 1791.64  857.04 1808.25  867.79 1823.42   884.1 1881.85  913.02 1938.31  934.04
  2050.3  940.97 2095.13  937.11 2147.23  924.32  2183.4  920.59 2218.07  922.35
#Mann= 3 , 0 , 0
       0      .1       0 1661.02    .047       0 1766.43      .1       0
#XS Ineff= 2 , 0
         1188.79  932.75
Permanent Ineff=
       F       F
Bank Sta=1661.02,1766.43
Exp/Cntr=0.3,0.1

Type RM Length L Ch R = 1 ,6084.145,602.3,602.3,766.77
XS GIS Cut Line= 4
  1361203.056771   768486.746073  1360372.569474   767196.972888
  1360037.458562    767386.68988  1359660.763905   767349.750616
#Sta/Elev= 30
       0  889.93  170.33  918.53  249.44  922.52  351.82  910.02  382.58  902.42
  538.74  899.18  639.36  884.46  663.62  886.93  759.26  874.78  810.44  875.24
 1014.18  887.31 1148.48  913.13 1260.05  926.23 1278.46  932.22  1336.7  929.29
 1371.46   935.6 1449.19  932.37 1472.08  936.33 1497.22  928.59 1534.02  925.48
 1644.11  862.28 1655.39  853.28 1672.12  847.06 1698.86  846.32 1774.37  857.19
  1848.6  872.57 1956.03  907.36 2123.77  946.51 2212.24  958.74 2297.61   955.4
#Mann= 3 , 0 , 0
       0      .1       0 1644.11    .047       0 1774.37      .1       0
Bank Sta=1644.11,1774.37
Exp/Cntr=0.3,0.1