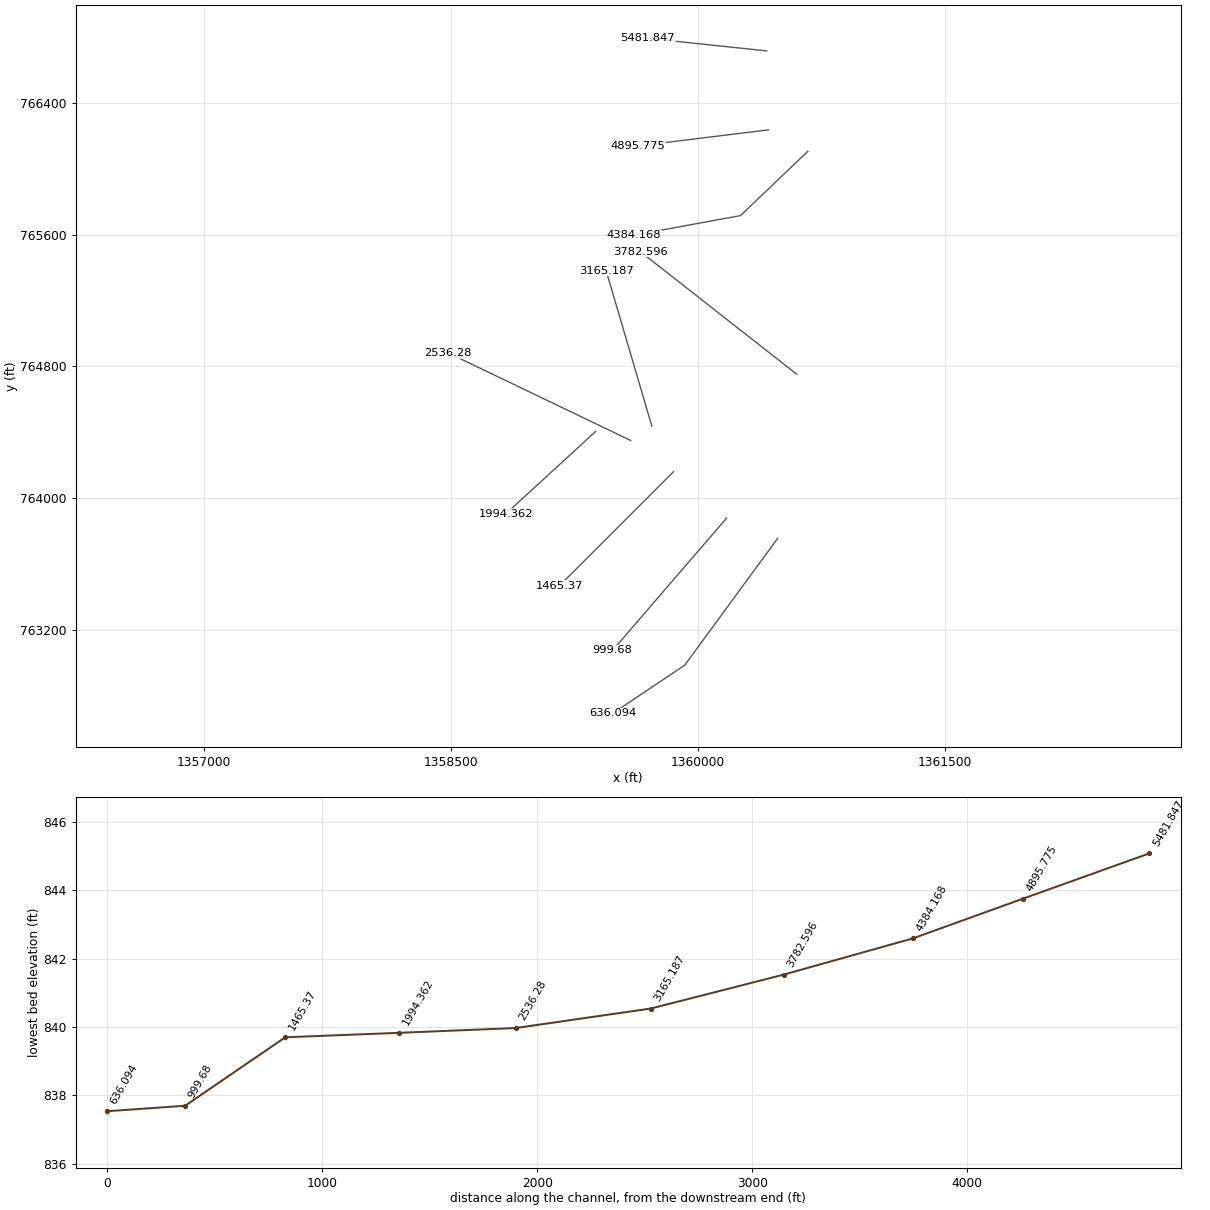
HEC-RAS study LLRiver.prj: LLRiver

--- LLRiver.g01 (geometry) --- (continued)

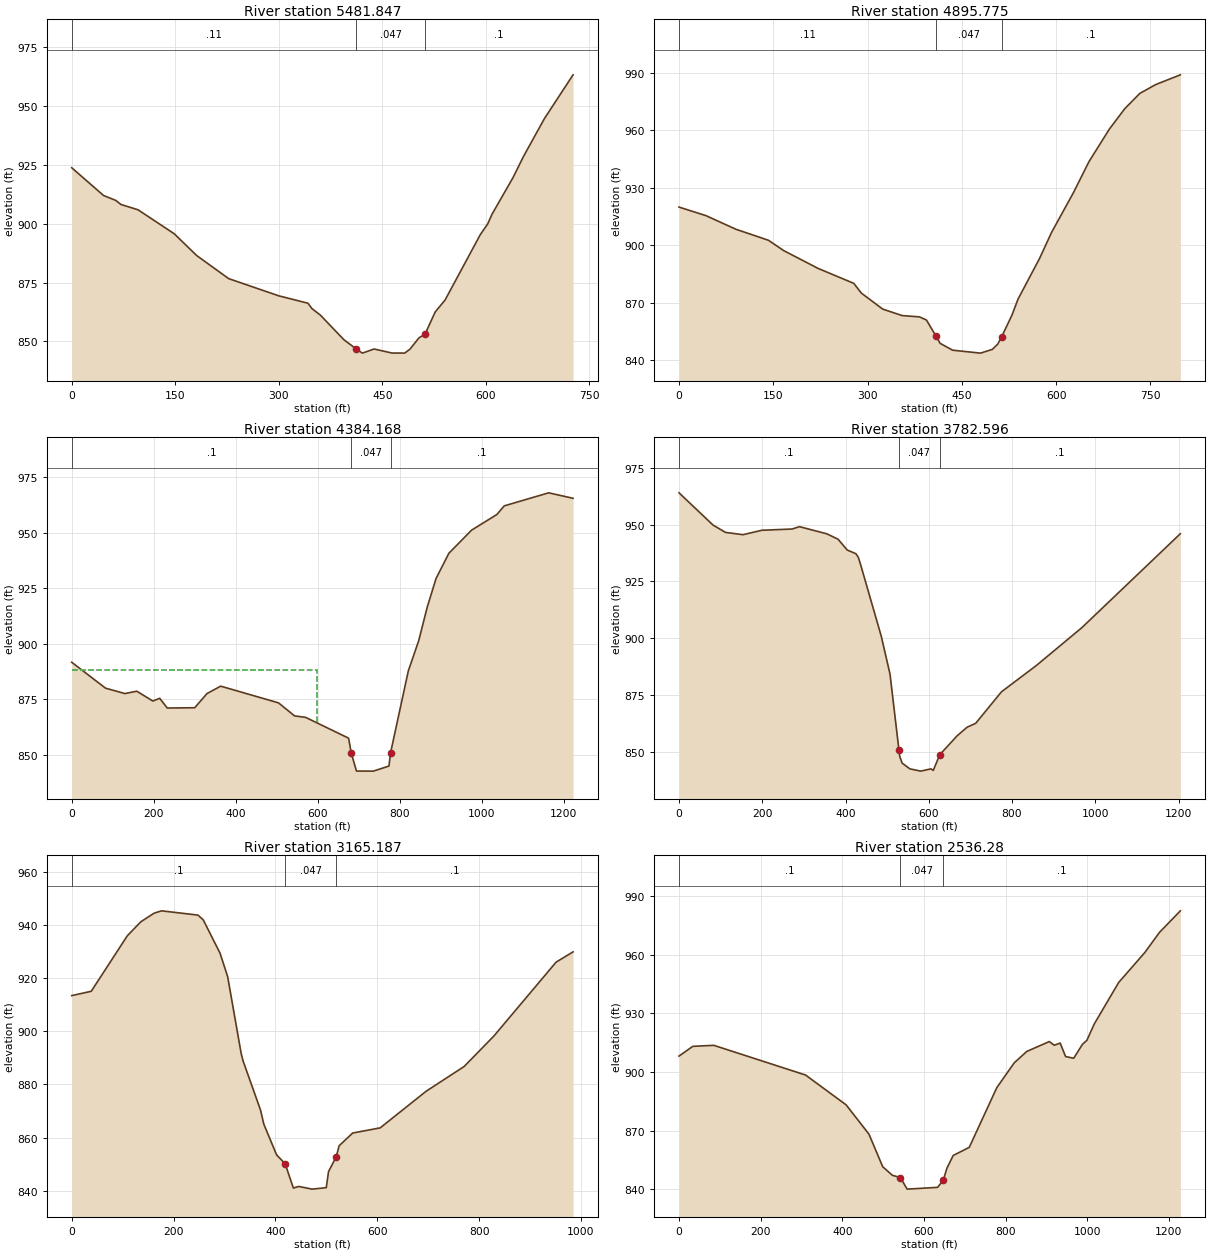
Type RM Length L Ch R = 1 ,5481.847,586.07,586.07,540.46
XS GIS Cut Line= 2
  1360418.014594   766715.518423  1359695.792385   766791.907287
#Sta/Elev= 30
       0  923.64   46.02  911.89   63.71  909.81   71.26  908.08   96.06  905.82
  148.56  895.65  180.94  886.45  227.39  876.64  299.87  869.36  342.25  866.22
  347.96  863.96   360.2  861.18  394.38  850.73  412.34  846.79  421.03  845.07
  438.03  846.82  463.96  845.11  482.43  845.09  489.88  846.72  503.16  851.57
  511.92  853.16  526.47  862.48  540.81  867.56  591.93  895.32  602.68  899.85
  608.75  903.88  639.39  919.53  654.44  928.42  684.67  944.42  726.25  963.02
#Mann= 3 , 0 , 0
       0     .11       0  412.34    .047       0  511.92      .1       0
Bank Sta=412.34,511.92
Exp/Cntr=0.3,0.1

Type RM Length L Ch R = 1 ,4895.775,511.61,511.61,480.1
XS GIS Cut Line= 2
  1360428.431234   766236.351831  1359636.764545   766139.129559
#Sta/Elev= 30
       0  919.98   42.68  915.54    90.5  908.41  142.29  902.66  166.66  897.25
   221.3  887.97     278  880.18  290.01  875.11  324.14  866.72  355.05  863.35
  382.59  862.67   393.7  861.02  408.86   852.6  415.46  848.85  435.35  845.28
  479.69  843.75  498.48   845.7  507.04  848.44  513.28  852.28  529.79  863.65
  539.31   871.9  573.71  893.24  592.73  906.77  627.69  927.62  652.21  943.69
  684.73  960.71  709.18  971.35  733.17  979.34  758.61  983.96  797.61  989.02
#Mann= 3 , 0 , 0
       0     .11       0  408.86    .047       0  513.28      .1       0
Bank Sta=408.86,513.28
Exp/Cntr=0.3,0.1

Type RM Length L Ch R = 1 ,4384.168,601.57,601.57,794.99
XS GIS Cut Line= 3
  1360667.672962   766106.714071   1360257.86509   765715.778902
  1359612.459009    765597.46287
#Sta/Elev= 30
       0  891.62   82.39  879.96  129.71  877.52  158.56  878.59  197.92  874.15
  214.47  875.39  233.03  871.01  299.91  871.14  329.93  877.53  363.27  880.86
  504.29  873.33  543.32  867.48  570.43   866.8  673.09  857.62  675.34  857.32
  681.64   850.7   694.4  842.62  735.58  842.59  773.61  844.88  777.49  850.83
  820.77  887.71  846.18  901.34  866.98  916.48  888.43  929.34  919.71  940.71
  975.07  951.12 1036.76  958.17 1054.69  962.05 1163.06  967.93 1222.53  965.47
#Mann= 3 , 0 , 0
       0      .1       0  681.64    .047       0  777.49      .1       0
#XS Ineff= 2 , 0
          598.69  888.07
Permanent Ineff=
       F       F
Bank Sta=681.64,777.49
Exp/Cntr=0.3,0.1

Type RM Length L Ch R = 1 ,3782.596,617.41,617.41,741.82
XS GIS Cut Line= 2
  1360598.570114   764753.712854  1359650.653441    765496.76847
#Sta/Elev= 30
       0  963.99   81.82  949.79  111.75  946.57  153.74  945.57     199  947.52
  271.46  948.06   289.5   949.1  355.15  945.95  382.03  943.58  404.22  938.81
  424.87  937.21  430.78  935.63  436.74   932.1  485.99  900.84  506.91  884.23
  528.23  851.02  530.24  848.06  535.99  845.06  554.64  842.53  580.52  841.53
  605.27  842.53  610.81  841.85  626.52  848.77  668.17  857.08  692.17  860.86
  712.77  862.57  774.71  876.44  858.44     888   967.5  904.61 1204.44     946
#Mann= 3 , 0 , 0
       0      .1       0  528.23    .047       0  626.52      .1       0
Bank Sta=528.23,626.52
Exp/Cntr=0.3,0.1

Type RM Length L Ch R = 1 ,3165.187,628.91,628.91,459.84
XS GIS Cut Line= 2
  1359720.097921   764437.740629  1359442.320129   765382.185174
#Sta/Elev= 30
       0  913.49   38.33  915.12  109.15  936.04  135.82  941.34  161.78  944.56
  176.33  945.45  247.89  943.84  258.33  942.02   291.2  929.51  306.23  920.61
  332.77  891.64  336.51  888.85  370.77  870.33  377.24  865.02   402.4  853.42
  418.97  850.16  435.23  840.95     446  841.55  472.07  840.54  499.81  841.09
  504.31  847.14  519.43  852.77  525.13   856.9  551.73  861.69   605.7  863.63
   695.9  877.43  770.66  886.78  829.25  898.31  951.11   926.1  984.45  929.98
#Mann= 3 , 0 , 0
       0      .1       0  418.97    .047       0  519.43      .1       0
Bank Sta=418.97,519.43
Exp/Cntr=0.3,0.1

Type RM Length L Ch R = 1 ,2536.28 ,541.92,541.92,300.28
XS GIS Cut Line= 2
  1359591.625729   764350.935125  1358483.986816   764882.185174
#Sta/Elev= 30
       0  908.17   33.75  913.16   85.27  913.68  310.06  898.46  409.39  883.18
  465.49  868.13  499.14  851.45  522.83  847.06  542.34  845.91  558.99  839.97
  633.58  840.88   647.5  844.52  656.58  850.77  671.92  857.24   711.2  861.38
  778.61  891.96  821.38  904.71  852.35  910.57  907.34  915.62  919.39  913.73
  933.95  914.83  947.27  907.93  967.12  907.06  988.66  914.22  999.39  916.24
 1017.38  924.59  1077.4  945.92 1141.26  961.22  1177.4   971.6 1228.45  982.63
#Mann= 3 , 0 , 0
       0      .1       0  542.34    .047       0   647.5      .1       0
Bank Sta=542.34,647.5
Exp/Cntr=0.3,0.1

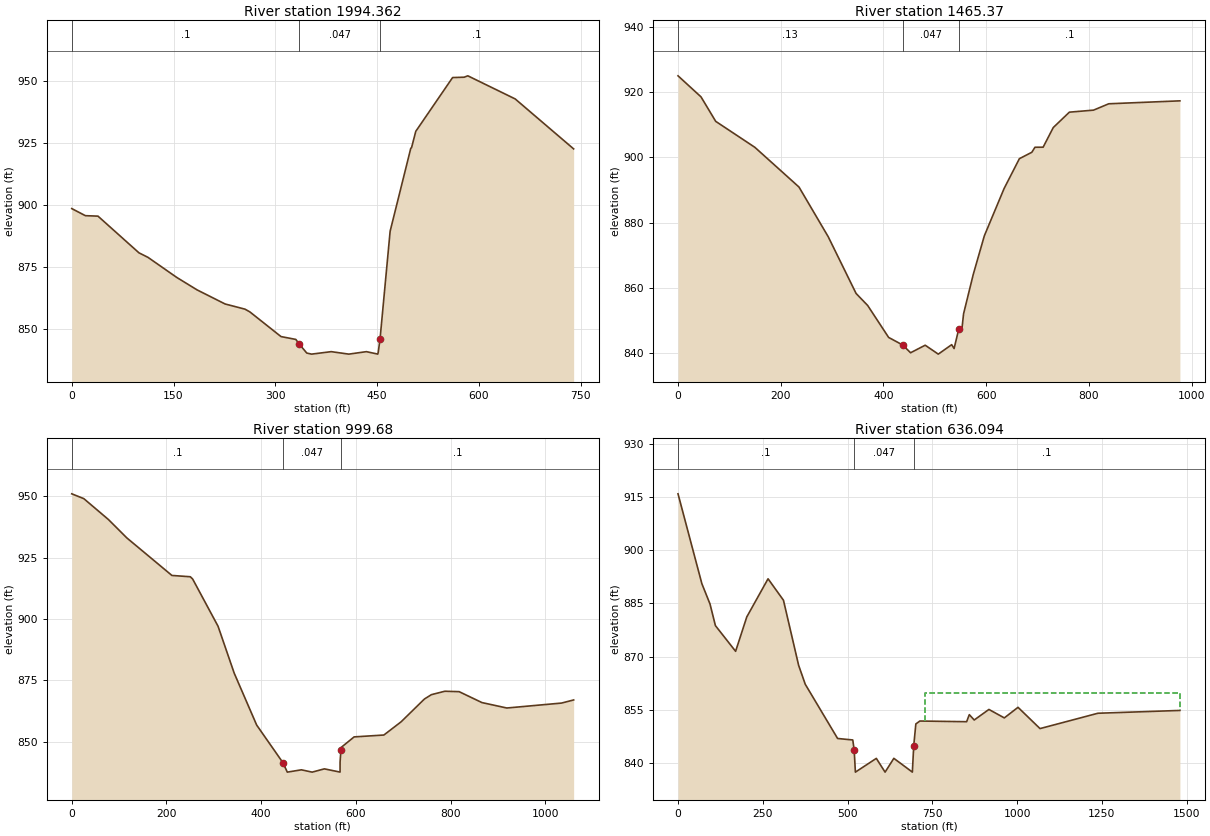
Type RM Length L Ch R = 1 ,1994.362,528.99,528.99,520.33
XS GIS Cut Line= 2
  1359379.820161   764406.490709  1358834.681345   763906.490709
#Sta/Elev= 30
       0  898.62   20.08  895.76   38.63  895.57   99.05  880.75  112.41  878.91
   154.7  870.82  184.76  865.77  225.99  860.09  255.37  857.99  262.49  856.89
   308.4  846.92  330.25  845.77  335.16  843.92  346.37  840.27  353.48  839.83
  382.45  840.83  408.35  839.83  434.25  840.83  451.04  839.84   451.8  840.73
  454.41  846.05  469.23  889.47  499.67  922.98   500.8  923.22  507.04  929.83
   561.3  951.55  578.27  951.69  583.77  952.25  653.53  942.92  739.71  922.73
#Mann= 3 , 0 , 0
       0      .1       0  335.16    .047       0  454.41      .1       0
Bank Sta=335.16,454.41
Exp/Cntr=0.3,0.1

Type RM Length L Ch R = 1 ,1465.37 ,465.69,465.69,450.86
XS GIS Cut Line= 2
  1359851.428738   764161.025493  1359160.456577   763470.053332
#Sta/Elev= 30
       0  925.02   44.75  918.57   73.41  911.06  149.55  903.11  235.56  890.92
  292.48  875.68   346.7   858.3  369.29  854.61  410.06  844.82  437.31  842.51
   452.8  840.12  481.25  842.43  506.75   839.7  532.82   842.6  537.54  841.41
  546.61  847.41  552.59  847.17  555.97  852.06   574.8  864.12   596.4  875.97
  634.88  890.47  664.65  899.62  688.87  901.58  694.97  903.12  710.88  903.14
  730.59  909.16  761.97  913.88  808.98   914.5  838.69  916.45  977.18  917.35
#Mann= 3 , 0 , 0
       0     .13       0  437.31    .047       0  546.61      .1       0
Bank Sta=437.31,546.61
Exp/Cntr=0.3,0.1

Type RM Length L Ch R = 1 ,999.68  ,363.59,363.59,347.78
XS GIS Cut Line= 2
  1360173.526402   763879.123541  1359481.386881   763076.292308
#Sta/Elev= 30
       0   950.9   25.47  948.94   77.38  940.46   116.5  932.94  211.54   917.7
   250.4  917.17   255.4  916.23     309  897.03  343.09  877.96  390.55  856.84
  446.12  841.51  455.26   837.7  484.96  838.64  507.72   837.7  533.57  839.03
  566.67  837.71   566.7  841.83  568.52  846.71  569.44  847.81  596.36  852.03
  659.18  852.79  695.62  858.17   744.9  867.45  759.73  869.22  787.91   870.6
  818.12  870.43   866.3  865.99   918.9  863.78 1034.48  865.79    1060  867.06
#Mann= 3 , 0 , 0
       0      .1       0  446.12    .047       0  568.52      .1       0
Bank Sta=446.12,568.52
Exp/Cntr=0.3,0.1

Type RM Length L Ch R = 1 ,636.094 ,636.09,636.09,477.71
XS GIS Cut Line= 3
   1360483.77421   763756.533205  1359919.946498   762987.221588
  1359482.691713   762694.197076
#Sta/Elev= 30
       0  915.86   70.37  890.56   94.28  884.88   110.3  878.77  169.84  871.54
   202.8  881.22  265.52  891.95  310.95  885.92  355.67  867.61  375.29  862.26
  470.63  847.01  515.38  846.59  519.56  843.76  523.09  837.54  584.83  841.41
  610.65  837.54  636.52  841.42  691.12  837.55   695.2     845  701.39   851.1
  713.22  851.92   851.2  851.73  859.05  853.72  873.53  852.21  916.91  855.18
  962.35   852.8 1002.75  855.78 1067.61  849.79 1238.35  854.11 1480.16   854.9
#Mann= 3 , 0 , 0
       0      .1       0  519.56    .047       0   695.2      .1       0
#XS Ineff= 2 , 0
                          727.68          859.78
Permanent Ineff=
       F       F
Bank Sta=519.56,695.2
Exp/Cntr=0.3,0.1

Chan Stop Cuts=-1
Use User Specified Reach Order=0
User Specified Reach Order=LLRiver         ,Main