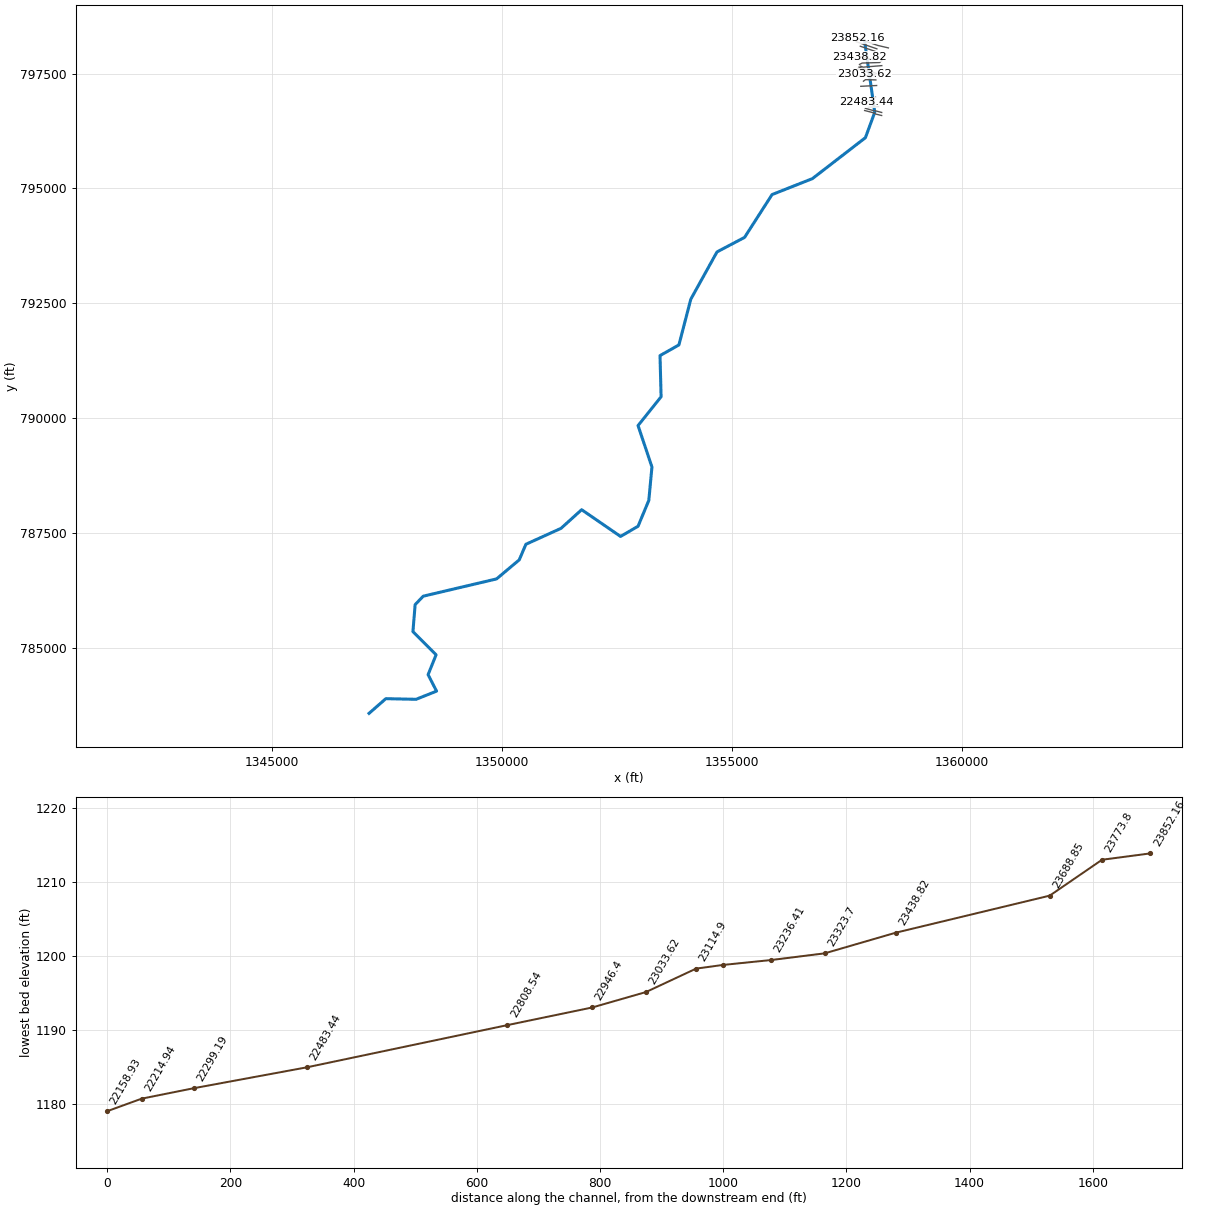
--- StirewaitCr.prj (project) ---

Proj Title=StirewaitCr
Current Plan=p01
Default Exp/Contr=0.3,0.1
English Units
Geom File=g01
Flow File=f01
Plan File=p01
Y Axis Title=Elevation
X Axis Title(PF)=Main Channel Distance
X Axis Title(XS)=Station
BEGIN DESCRIPTION:
END DESCRIPTION:
DSS Export Rating Curves= 0
DSS Export Rating Curve Sorted= 0
DSS Export Volume Flow Curves= 0
DXF OffsetX= 0
DXF OffsetY= 0
DXF ScaleX= 1
DXF ScaleY= 10

--- StirewaitCr.p01 (plan) ---

Plan Title=StirewaitCr
Program Version=3.12
Short Identifier=100YR
Geom File=g01
Flow File=f01
Subcritical Flow
K Sum by GR= 0
Std Step Tol= 0.01
Critical Tol= 0.01
Num of Std Step Trials= 20
Max Error Tol= 0.3
Flow Tol Ratio= 0.001
Split Flow NTrial= 30
Split Flow Tol= 0.02
Split Flow Ratio= 0.02
Log Output Level= 0
Friction Slope Method= 1
Unsteady Friction Slope Method= 2
Unsteady Bridges Friction Slope Method= 1
Calc Critical at every XS
Parabolic Critical Depth
Global Vel Dist= 0 , 0 , 0
Global Log Level= 0
CheckData=True
Encroach Param=-1 ,0,0, 2
Encroach River=StirewaitCr
Encroach Reach=Main
Encroach Node=23852.16
       1     515   575.1
Encroach Node=23773.8
       1  288.12   299.1
Encroach Node=23688.85
       1   212.5239.1602
Encroach Node=23438.82
       1     240     300
Encroach Node=23323.7
       1     330     390
Encroach Node=23236.41
       1     295     390
Encroach Node=23158.7
       1     181     223
Encroach Node=23114.9
       1  181.65  194.18
Encroach Node=23033.62
       1     126142.5497
Encroach Node=22946.4
       1  186.61209.9078
Encroach Node=22808.54
       1193.1572211.9661
Encroach Node=22483.44
       1      69 106.925
Encroach Node=22299.19
       1  80.205132.9037
Encroach Node=22214.94
       1     140     180
Encroach Node=22158.93
       1     141     183
Encroach Node=22076.09
       1  96.255     140
Encroach Node=21746.69
       1150.4653176.7344
Encroach Node=21450.46
       1   118.7   158.5
Encroach Node=21155.09
       1     107     137
Encroach Node=20859.89
       1    95.5   139.5
Encroach Node=20544.57
       1     133     175
Encroach Node=20182.94
       1     180     260
Encroach Node=20065.12
       1     280     370
Encroach Node=19995.85
       1     215     315
Encroach Node=19806.84
       1137.0127     181
Encroach Node=19497.54
       1131.7465204.4151
Encroach Node=19205.76
       1     170     280
Encroach Node=18896.82
       1      80     150
Encroach Node=18672.85
       1 110.399     268
Encroach Node=18562.79
       1      64180.1414
Encroach Node=18469.27
       1     159     415
Encroach Node=18404.04
       1     158     220
Encroach Node=18302.79
       1     138   237.8
Encroach Node=17915.28
       1     200     330
Encroach Node=17809.36
       1     230     295
Encroach Node=17726.03
       1   184.2   218.5
Encroach Node=17614.63
       1     127     165
Encroach Node=17271.02
       1     400502.3746
Encroach Node=16942.91
       1252.3971     330
Encroach Node=16788.53
       1     270     363
Encroach Node=16730.66
       1     235  483.04
Encroach Node=16649.53
       1     370     445
Encroach Node=16580.73
       1 335.085     475
Encroach Node=16356.99
       1349.4151502.5458
Encroach Node=15884.74
       1     350     500
Encroach Node=15682.25
       1374.2497547.7028
Encroach Node=15587.31
       1     430     525
Encroach Node=15300.99
       1     485     560
Encroach Node=15231.15
       1     255     291
Encroach Node=14977.3
       1     150     375
Encroach Node=14671.17
       1     215     300
Encroach Node=14320.87
       1188.7797     245
Encroach Node=14072.4
       1232.3835     280
Encroach Node=13837.04
       1296.7652  391.35
Encroach Node=13335.84
       1     260     368
Encroach Node=12930.02
       1     225     420
Encroach Node=12618.11
       1231.8926     325
Encroach Node=12258.2
       1     320     403
Encroach Node=11998.14
       1     300   434.8
Encroach Node=11712.17
       1     320     430
Encroach Node=11403.65
       1     160286.6929
Encroach Node=11109.33
       1     182     264
Encroach Node=10779.52
       1      95     215
Encroach Node=10710.57
       1      40     156
Encroach Node=10640.7
       1     140     208
Encroach Node=10570.78
       1     128     172
Encroach Node=10487.61
       1     125     213
Encroach Node=10333.22
       1     135     214
Encroach Node=10057.66
       1     310     430
Encroach Node=9744.597
       1     220     290
Encroach Node=9401.387
       1124.9473     180
Encroach Node=8845.506
       1     140     233
Encroach Node=8548.978
       1     156     188
Encroach Node=8284.072
       1151.2659200.3693
Encroach Node=7951.217
       1 153.957     220
Encroach Node=7649.766
       1128.6315     163
Encroach Node=7315.373
       1242.6358340.9473
Encroach Node=7023.172
       1     270     378
Encroach Node=6744.781
       1     278     350
Encroach Node=6454.157
       1     190     320
Encroach Node=6053.273
       1     158     290
Encroach Node=5818.415
       1     130     260
Encroach Node=5508.673
       1     260     390
Encroach Node=5272.761
       1     180     300
Encroach Node=4862.696
       1     280     420
Encroach Node=4647.255
       1     245     390
Encroach Node=4499.289
       1     215     355
Encroach Node=4346.578
       1     195     325
Encroach Node=4290.365
       1      60     190
Encroach Node=4217.646
       1     120     210
Encroach Node=4170.108
       1     110     200
Encroach Node=4069.006
       1 209.048     276
Encroach Node=3757.351
       1194.2167     247
Encroach Node=3470.736
       1     105     163
Encroach Node=3172.98
       1     220     283
Encroach Node=2697.878
       1     350     417
Encroach Node=2404.915
       1     195     265
Encroach Node=2121.609
       1     215     280
Encroach Node=1794.844
       1 187.594     230
Encroach Node=1515.103
       1     110     167
Encroach Node=1193.743
       1     117     158
Encroach Node=892.667
       1     150     230
Encroach Node=698.799
       1     130     250
Encroach Node=292.188
       1     180     298
Computation Interval=1HOUR
Output Interval=1HOUR
Run HTab= 0
Run UNet= 0
Run PostProcess= 0
UNET Theta= 1
UNET Theta Warmup= 1
UNET ZTol= 0.02
UNET ZSATol= 0.05
UNET MxIter= 20
UNET MaxInSteps= 0
UNET DtIC= 0
UNET DtMin= 0
UNET MaxCRTS= 20
UNET WFStab= 2
UNET SFStab= 1
UNET WFX= 1
UNET SFX= 1
UNET DSS MLevel= 4
UNET DZMax Abort= 100
UNET Convert EG Bridges=-1
UNET Use Existing IB Tables=-1
UNET Froude Reduction=False
UNET Froude Limit= 1
UNET Froude Power= 10
Instantaneous Interval=1HOUR
Write IC File= 0
Echo Input=False
Echo Output=False
Write Detailed= 0
Detailed Automatic Start=False, 10

--- StirewaitCr.f01 (steady flow) ---

Flow Title=StirewaitCr
Program Version=3.12
Number of Profiles= 2
Profile Names=P100yr,FW
River Rch & RM=StirewaitCr,Main            ,23852.16
     484     484
River Rch & RM=StirewaitCr,Main            ,22483.44
     581     581
River Rch & RM=StirewaitCr,Main            ,21155.09
     659     659
River Rch & RM=StirewaitCr,Main            ,19497.54
     823     823
River Rch & RM=StirewaitCr,Main            ,18302.79
     988     988
River Rch & RM=StirewaitCr,Main            ,17271.02
    1160    1160
River Rch & RM=StirewaitCr,Main            ,15884.74
    1290    1290
River Rch & RM=StirewaitCr,Main            ,13335.84
    1470    1470
River Rch & RM=StirewaitCr,Main            ,10057.66
    1650    1650
River Rch & RM=StirewaitCr,Main            ,7023.172
    2130    2130
River Rch & RM=StirewaitCr,Main            ,2121.609
    2380    2380
Boundary for River Rch & Prof#=StirewaitCr,Main            , 1
Up Type= 0
Dn Type= 3
Dn Slope=0.001
DSS Import GetInterval= 0
DSS Import GetPeak= 0
DSS Import FillOption= 0

--- StirewaitCr.g01 (geometry) ---

Geom Title=StirewaitCr
Program Version=3.12

River Reach=StirewaitCr     ,Main
Reach XY= 30
  1357885.615289   798217.134368  1358108.603157   796658.693256
  1357905.127009   796104.181838   1356752.61304   795214.167703
  1355873.471676   794866.238953  1355275.998302   793935.060825
  1354675.913406   793619.287198  1354105.869437   792590.101571
  1353847.501928   791595.749226   1353436.41726   791363.031504
  1353459.500137   790466.998091  1352958.129241    789840.94089
  1353260.500065   788940.250958   1353192.49829   788213.378926
  1352958.129241   787650.248537  1352577.750092   787428.560749
  1351730.953189   788010.219986  1351282.750567   787604.881253
  1350517.854358   787258.093699  1350373.135444   786918.379354
  1349879.467238   786504.455178  1348284.503146   786128.498508
   1348108.12937   785944.559458  1348060.247143   785358.810969
  1348563.861688   784853.036268  1348389.897337   784421.387206
   1348574.25008   784062.558024  1348128.380002   783884.939116
  1347470.750826   783898.750816  1347105.129648   783578.812175

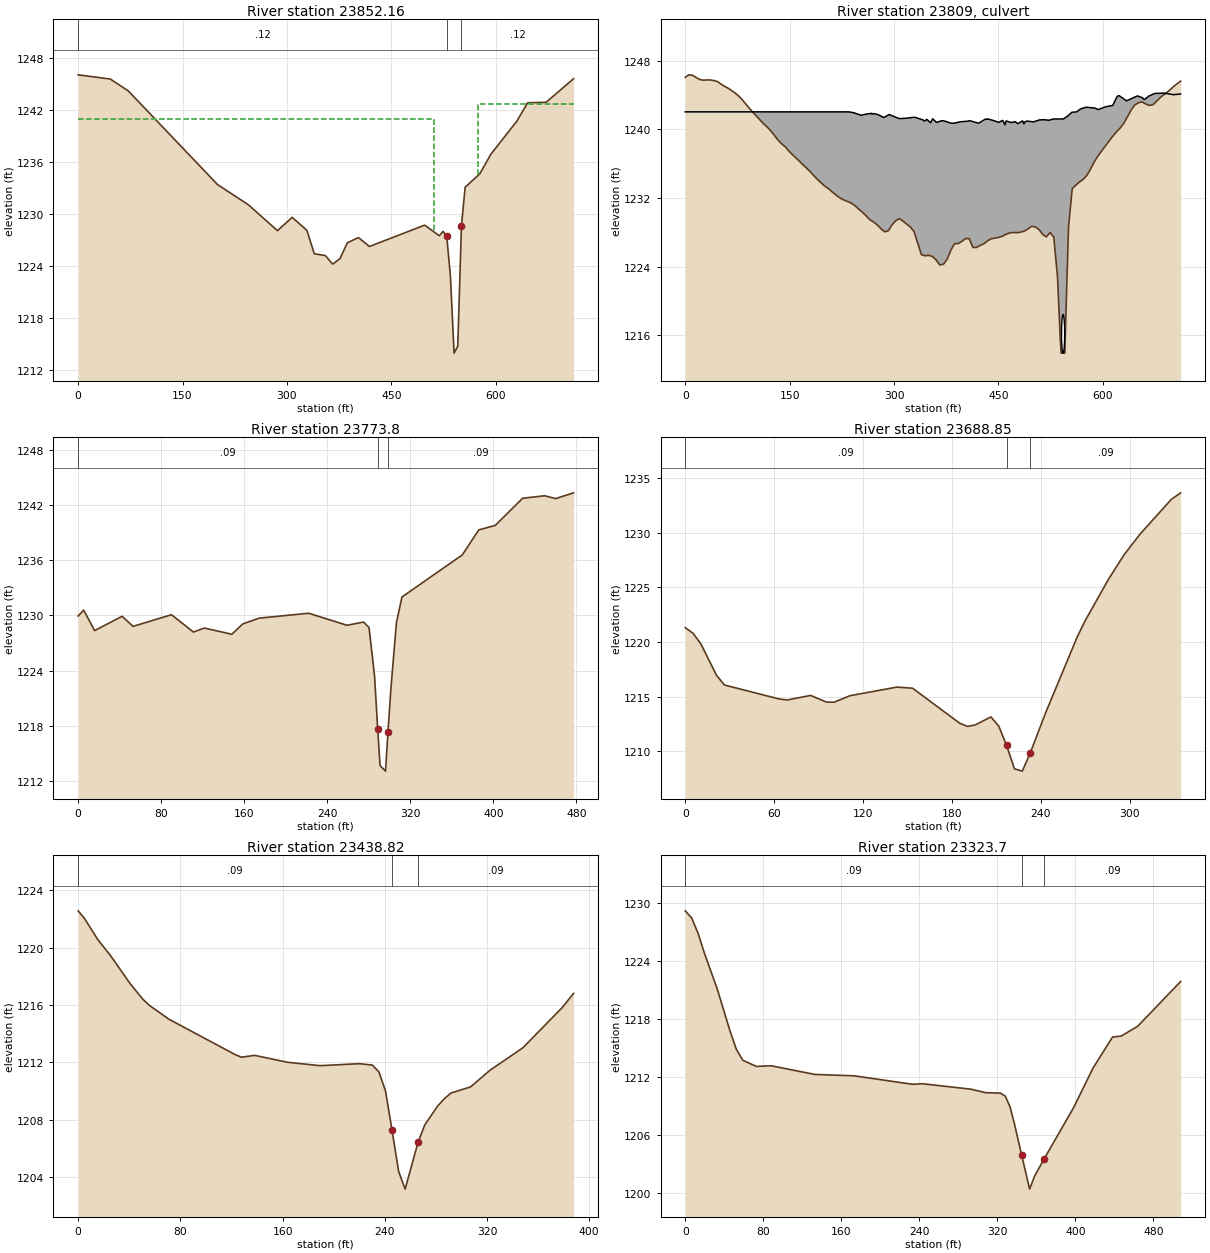
Type RM Length L Ch R = 1 ,23852.16,79.03,78.36,36.23
XS GIS Cut Line= 3
  1358404.826228   798057.989128  1358172.250906   798112.402162
  1357724.881585   798266.259352
#Sta/Elev= 30
       0 1246.08   46.23 1245.59   71.89 1244.23  200.28 1233.39  244.15 1231.08
  286.45 1228.06   307.6  1229.6  328.75 1228.09  339.32 1225.39  355.18 1225.18
  365.76 1224.19  376.33 1224.84  386.91 1226.66  402.77 1227.26  418.63 1226.23
  497.94  1228.7  519.09 1227.47  524.38 1227.98  529.67 1227.42  534.96 1222.82
  540.24  1213.9  545.53  1214.7  550.82  1228.6  556.11 1233.08  577.26 1234.64
  593.12  1236.9  630.14 1240.69  645.99 1242.85  672.44  1242.9  711.95 1245.63
#Mann= 3 , 0 , 0
       0     .12       0  529.67    .055       0  550.82     .12       0
#XS Ineff= 2 , 0
       0  510.75    1241  575.23       0  1242.7
Permanent Ineff=
       F       F
Bank Sta=529.67,550.82
Exp/Cntr=0.5,0.3

Type RM Length L Ch R = 2 ,23809   ,,,
BEGIN DESCRIPTION:
37003-0001 (Rail Road X-ing)
END DESCRIPTION:
Bridge Culvert--1,0,-1,-1, 0
Deck Dist Width WeirC Skew NumUp NumDn MinLoCord MaxHiCord MaxSubmerge Is_Ogee
30,15,2.6,0, 94, 94, , , 0.95, 0, 0,0,,
       0  234.58   241.5  242.07  242.14  253.11  254.86     262  267.35  268.39
  270.16  277.03  281.05  285.29  292.93  293.51  305.58  308.23  316.74  318.63
  329.64   330.1  341.88  343.74  347.19   352.6  355.48   361.1  368.27   370.9
   381.5   385.3  393.31  395.97  406.13  408.69  419.26  421.81  431.31  432.84
  433.25  434.67  446.84  449.88  456.27  459.53  461.08  468.74  474.14  477.84
   484.8  486.59  487.55  490.76   500.6  508.36  515.24   522.8  528.82  535.93
  537.77   539.1  540.24  542.13  542.79   543.4  549.85  555.53  562.34  567.88
  575.79  580.32  588.26  593.69  603.59  607.39  614.35  620.73  623.35  634.07
   634.4  647.52  649.81  656.85  659.44  660.28  666.29  673.85  675.28  687.99
  688.17  701.77  702.04  711.86
 1242.05 1242.05 1241.96 1241.94 1241.95 1241.64 1241.71 1241.81 1241.88 1241.78
 1241.85 1241.73 1241.56 1241.39 1241.73 1241.72 1241.32 1241.26  1241.3 1241.32
 1241.42 1241.42  1241.1 1240.97 1241.17 1240.78 1241.24 1240.82 1241.01 1241.02
 1240.74 1240.72 1240.85  1240.9 1240.96 1241.02 1240.78 1240.73 1241.21 1241.16
 1241.18 1241.23 1240.94 1240.82 1241.05 1240.53 1240.99  1240.8 1240.91 1240.67
    1241 1240.66 1240.83 1240.98 1240.88  1241.1 1241.14 1241.07 1241.22 1241.22
 1241.22 1241.22 1241.22 1241.22 1241.22 1241.22 1241.58    1242 1242.05 1242.38
 1242.59 1242.56  1242.5 1242.32 1242.63  1242.7  1242.8 1243.86 1243.95 1243.34
 1243.34 1243.83 1243.91  1243.7  1243.5 1243.51 1243.89 1244.17  1244.2 1244.24
 1244.24 1244.05 1244.06 1244.13
                                                                                
                                                                                
                                                                                
                                                                                
                                                                                
                                                                                
                                                                                
                                                                                
                                                                                
                                
     -10   -3.08   -2.51   -2.44    8.53   10.28   17.42   22.77   23.81   25.58
   32.45   36.47   40.71   48.35   48.93      61   63.65   72.16   74.05   85.06
   85.52    97.3   99.16  102.61  108.02   110.9  116.52  123.69  126.32  136.92
  140.72  148.73  151.39  161.55  164.11  174.68  177.23  186.73  188.26  188.67
  190.09  202.26   205.3  211.69  214.95   216.5  224.16  229.56  233.26  240.22
  242.01  242.97  246.18  256.02  263.78  270.66  278.22  284.24  291.35  293.19
  294.52  295.66  297.55  298.21  298.82  305.27  310.95  317.76   323.3  331.21
  335.74  343.68  349.11  359.01  362.81  369.77  376.15  378.77  389.49  389.82
  402.94  405.23  412.27  414.86   415.7  421.71  429.27   430.7  443.41  443.59
  457.19  457.46  467.28    1000
 1242.05 1241.96 1241.94 1241.95 1241.64 1241.71 1241.81 1241.88 1241.78 1241.85
 1241.73 1241.56 1241.39 1241.73 1241.72 1241.32 1241.26  1241.3 1241.32 1241.42
 1241.42  1241.1 1240.97 1241.17 1240.78 1241.24 1240.82 1241.01 1241.02 1240.74
 1240.72 1240.85  1240.9 1240.96 1241.02 1240.78 1240.73 1241.21 1241.16 1241.18
 1241.23 1240.94 1240.82 1241.05 1240.53 1240.99  1240.8 1240.91 1240.67    1241
 1240.66 1240.83 1240.98 1240.88  1241.1 1241.14 1241.07 1241.22 1241.22 1241.22
 1241.22 1241.22 1241.22 1241.22 1241.22 1241.58    1242 1242.05 1242.38 1242.59
 1242.56  1242.5 1242.32 1242.63  1242.7  1242.8 1243.86 1243.95 1243.34 1243.34
 1243.83 1243.91  1243.7  1243.5 1243.51 1243.89 1244.17  1244.2 1244.24 1244.24
 1244.05 1244.06 1244.13 1244.13
                                                                                
                                                                                
                                                                                
                                                                                
                                                                                
                                                                                
                                                                                
                                                                                
                                                                                
                                
BR Coef=-1 , 0 , 0 ,, 0 ,,,0.8,-1,,0,
WSPro=,,,, 1 ,,,, 0 ,,,, 0 ,,,,-1 ,-1 ,-1 , 0 , 0 , 0 , 0 , 0
Culvert=1,4.5,,60,0.012,0.5,1,1,1,1213.9,543,1213.04,293.32,Culvert #1  , 0 ,7.5
Culvert Bottom n=0.012
BR U #Sta/Elev= 130
       0 1246.08    5.14 1246.37   10.27 1246.32   15.41 1246.08   20.54 1245.83
   25.69 1245.75   30.81 1245.77   35.96 1245.77   41.08  1245.7   46.23 1245.59
   51.35 1245.29    56.5 1245.03   61.62 1244.81   66.77 1244.53   71.89 1244.23
   77.04 1243.88   82.16 1243.44   87.31 1242.93   92.43 1242.44   97.58 1241.96
  112.97 1240.63  118.12 1240.25  123.24  1239.8  128.39 1239.28  133.51 1238.74
  138.65 1238.31  143.78 1237.96  148.92 1237.48  154.05 1237.05  159.19 1236.67
  164.32 1236.27  169.46 1235.85  174.59 1235.47  179.73 1235.05  184.86 1234.59
     190 1234.17  200.28 1233.39   205.4 1233.11  210.55 1232.75  215.67 1232.41
  220.82 1232.09  225.94 1231.84  231.09 1231.67  236.21 1231.49  238.86 1231.38
  244.15 1231.08  254.72 1230.32  260.01 1229.91   265.3 1229.46  270.59  1229.2
  275.87 1228.86  281.16 1228.42  286.45 1228.06  291.74 1228.16  297.02 1228.85
  302.31 1229.33   307.6  1229.6  312.89  1229.3  318.17 1228.95  323.46 1228.61
  328.75 1228.09  334.04 1226.72  339.32 1225.39  344.61 1225.26   349.9 1225.31
  355.18 1225.18  360.47 1224.78  365.76 1224.19  371.05 1224.26  376.33 1224.84
  381.62 1225.89  386.91 1226.66   392.2 1226.68  397.48 1226.93  402.77 1227.26
  408.06 1227.26  413.35 1226.23  418.63 1226.23  423.92 1226.47  429.21 1226.66
   434.5    1227  439.78 1227.24  450.36  1227.4  455.65 1227.53  460.93 1227.76
  466.23 1227.92  471.51 1227.98  476.79 1227.95  482.08 1228.01  487.38 1228.14
  492.66  1228.4  497.94  1228.7  503.23 1228.61  508.52 1228.31  513.81 1227.73
  519.09 1227.47  524.38 1227.98  529.67 1227.42  534.96 1222.82     539  1215.5
  540.24  1213.9  545.53  1213.9     546  1215.5  550.82  1228.6  556.11 1233.08
   561.4  1233.5  566.68 1233.87  571.97 1234.18  577.26 1234.64  582.55 1235.39
  587.83 1236.23  593.12  1236.9  603.69 1238.06  614.27 1239.19  619.56 1239.69
  624.84 1240.14  630.14 1240.69  635.42 1241.48  640.71 1242.25  645.99 1242.85
  651.29 1243.11  656.57 1243.21  661.86 1242.96  667.14  1242.8  672.44  1242.9
  677.72 1243.31  683.01 1243.74  693.58 1244.41  704.16 1245.16  711.95 1245.63
BR U #Mann= 3
       0      .1  534.96    .055  550.82      .1
BR U Banks=539,546
BR D #Sta/Elev= 87
       0 1229.94    5.29 1230.58   10.56 1229.64   15.86 1228.35   21.15 1228.46
   26.44 1229.18   31.71 1229.39   37.01 1229.69    42.3 1229.91   47.58 1229.32
   52.86 1228.81   58.16 1229.03   63.45 1229.16   68.74 1229.41   74.01 1229.64
   79.31 1229.75    84.6 1230.05   89.89 1230.08   95.16 1229.83  100.46 1229.21
  105.75 1228.39  111.04 1228.19  116.31 1228.63  121.61 1228.63  132.19 1228.54
  137.46 1228.25  142.76 1227.98  148.05 1227.95  153.34  1228.5  158.61 1229.08
  163.91 1229.31   169.2 1229.49  174.48 1229.71  185.06 1229.64  190.35 1229.63
  195.63 1229.72  200.92    1230  206.21 1229.98   211.5 1229.87  216.77 1229.95
  222.07 1230.24  227.36 1230.21  232.65 1230.07  237.92 1229.81  243.22 1229.52
  248.51 1229.31   253.8  1229.2  259.07 1228.93  264.37 1228.89  274.95 1229.28
  280.22 1228.69  285.52 1223.43   289.5    1215  290.81 1213.04  296.09 1213.04
     297    1215  301.37 1222.14  306.67 1229.25  311.96 1232.01  317.24 1232.49
  322.52 1232.83  333.11 1233.61  338.39 1233.98  343.67 1234.51  348.97 1235.12
  354.26 1235.35  359.54 1235.78  364.82 1236.31  370.12  1236.6  375.41 1237.33
   380.7 1238.46  385.97 1239.32  391.27 1239.59  396.56 1239.73  401.83 1239.81
  407.12 1240.33  412.42 1240.83  417.71 1241.39  422.98 1242.26  428.27 1242.77
  433.57 1242.96  444.13 1243.02  449.42 1243.04  454.72 1242.93  460.01 1242.73
  465.28 1242.82  477.28 1243.36
BR D #Mann= 3
       0      .1  285.52    .055  301.37      .1
BR D Banks=289.5,297
BC Design=,, 0 ,, 0 ,,,,,,

Type RM Length L Ch R = 1 ,23773.8 ,83.07,84.95,82.69
XS GIS Cut Line= 2
   1358154.72146   798037.807414   1357703.38964   798193.027362
#Sta/Elev= 30
       0 1229.94    5.29 1230.58   15.86 1228.35    42.3 1229.91   52.86 1228.81
   89.89 1230.08  111.04 1228.19  121.61 1228.63  148.05 1227.95  158.61 1229.08
  174.48 1229.71  222.07 1230.24  259.07 1228.93  274.95 1229.28  280.22 1228.69
  285.52 1223.43  288.59 1217.59  290.81 1213.66  296.09 1213.04  298.49 1217.33
  301.37 1222.14  306.67 1229.25  311.96 1232.01  370.12  1236.6  385.97 1239.32
  401.83 1239.81  428.27 1242.77  449.42 1243.04  460.01 1242.73  477.28 1243.36
#Mann= 3 , 0 , 0
       0     .09       0  288.59    .055       0  298.49     .09       0
#XS Ineff= 2 , 0
       0   266.1    1218   320.6       0    1218
Permanent Ineff=
       F       F
Bank Sta=288.59,298.49
Exp/Cntr=0.5,0.3

Type RM Length L Ch R = 1 ,23688.85,236.41,250.03,248.92
XS GIS Cut Line= 2
  1358110.145474   797985.271461  1357794.133568   798094.323421
#Sta/Elev= 30
       0 1221.31     5.3 1220.79   10.59 1219.81   21.17 1216.93   26.46 1216.06
   63.47 1214.78   68.76 1214.69   84.63 1215.11   95.22  1214.5  100.51 1214.49
  111.09 1215.08  142.81 1215.87  153.39 1215.77  185.14 1212.57  190.43 1212.27
  195.71 1212.41  206.28 1213.14  211.57  1212.3  216.86 1210.53  222.15 1208.39
  227.44 1208.18  232.73 1209.82  243.31 1213.56  264.48 1220.45  269.77 1221.92
  285.62 1225.74   296.2 1227.99  306.78 1229.85  327.94 1233.04  334.31 1233.65
#Mann= 3 , 0 , 0
       0     .09       0  216.86    .055       0  232.73     .09       0
Bank Sta=216.86,232.73
Exp/Cntr=0.3,0.1

Type RM Length L Ch R = 1 ,23438.82,106.28,115.12,122.46
XS GIS Cut Line= 3
  1358162.794769   797821.007113  1358072.143462   797805.241685
  1357783.438818   797869.288785
#Sta/Elev= 30
       0 1222.57    5.08 1222.02   15.23 1220.58   25.38 1219.44   40.59  1217.5
   50.74 1216.39   55.83 1215.97   71.04 1215.01  122.73 1212.55  127.85 1212.36
  138.11 1212.49   163.7 1212.01  189.31 1211.77  220.04 1211.91  230.28 1211.81
  235.42 1211.33  240.54    1210  245.66 1207.27  250.77 1204.41  255.89 1203.16
  266.13 1206.46  271.27 1207.64   281.5 1208.97  286.62 1209.47  291.74 1209.86
  307.12 1210.29  322.47 1211.46  348.08 1213.02  378.81 1215.82  387.73 1216.81
#Mann= 3 , 0 , 0
       0     .09       0  245.66    .055       0  266.13     .09       0
Bank Sta=245.66,266.13
Exp/Cntr=0.3,0.1

Type RM Length L Ch R = 1 ,23323.7 ,85.72,87.29,88.81
XS GIS Cut Line= 5
  1358261.575126   797780.484989  1358213.539789   797739.839743
  1357835.415512    797728.75463  1357791.075198   797705.352822
  1357776.295108   797697.962777
#Sta/Elev= 30
       0  1229.2    6.56 1228.46   13.11 1226.87   19.66  1224.8   32.75 1221.12
   45.85 1216.76    52.4 1214.85   58.95 1213.72   72.93 1213.08   87.93 1213.15
  132.95 1212.25  172.97 1212.11     233 1211.23     243 1211.29  293.02 1210.72
  308.03 1210.36  323.05 1210.32  328.04 1210.01  333.04 1208.87  338.04  1206.9
  344.83  1203.9  353.05 1200.37  358.05 1201.71  368.07 1203.53  398.07  1208.8
  418.09 1212.92   438.1 1216.13  446.86 1216.22  463.83 1217.24  507.87 1221.88
#Mann= 3 , 0 , 0
       0     .09       0  344.83    .055       0  368.07     .09       0
Bank Sta=344.83,368.07
Exp/Cntr=0.3,0.1

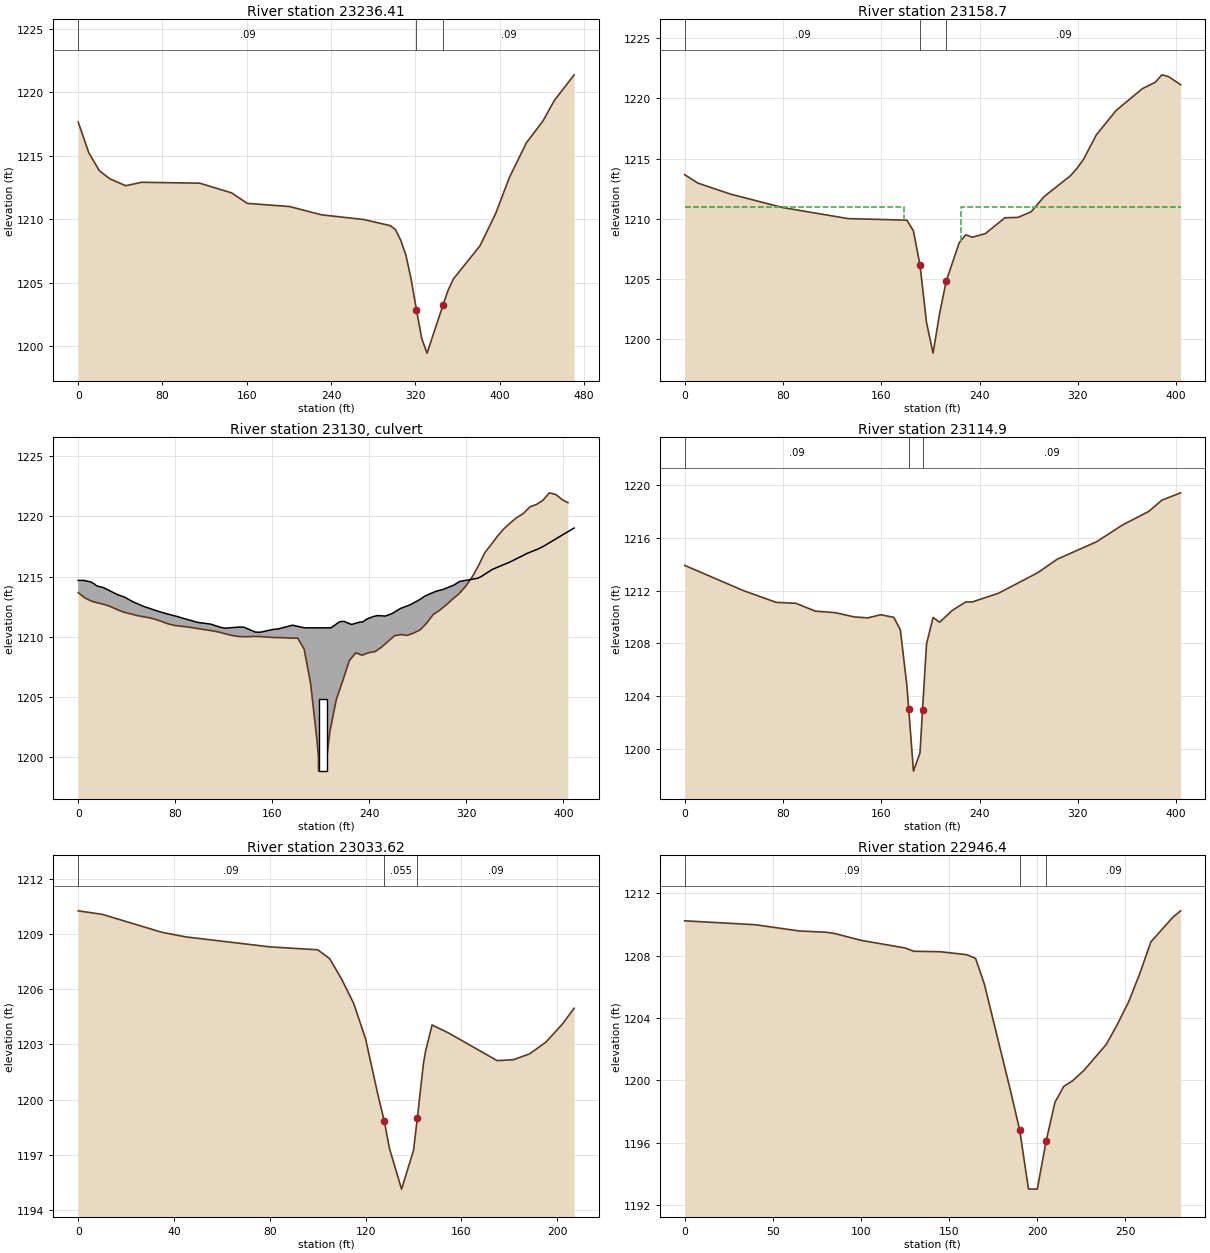
Type RM Length L Ch R = 1 ,23236.41,92.94,77.71,61.71
XS GIS Cut Line= 3
  1358261.739923   797672.427169  1357858.982118   797639.171968
  1357796.166692   797661.342102
#Sta/Elev= 30
       0 1217.65   10.03 1215.24   20.07 1213.82    30.1 1213.18   45.15 1212.64
    60.2 1212.91  115.39 1212.84  145.49 1212.08  160.54 1211.25  200.68    1211
  230.78 1210.35  270.92 1209.98     296  1209.5  301.02  1209.2  306.04 1208.37
  311.06 1207.17  316.07 1205.25  321.09 1202.86  326.12 1200.59  331.12 1199.46
  346.17 1203.22  351.19 1204.43  356.21 1205.31  381.29  1207.9  396.34 1210.47
  409.44 1213.32  425.34 1216.01  441.25 1217.75  451.85 1219.34  470.74 1221.37
#Mann= 3 , 0 , 0
       0     .09       0  321.09    .055       0  346.17     .09       0
Bank Sta=321.09,346.17
Exp/Cntr=0.5,0.3

Type RM Length L Ch R = 1 ,23158.7 ,41.4,43.8,45.67
XS GIS Cut Line= 2
  1358145.035845   797501.208357  1357765.679894    797639.15595
#Sta/Elev= 30
       0 1213.66   10.64 1212.96   37.24 1212.04    79.8 1210.92  133.02    1210
  180.89 1209.87  186.21 1208.97  191.53 1206.13  196.85 1201.34  202.17  1198.8
  207.49  1202.1  212.81 1204.78  223.45 1207.99  228.77 1208.65  234.09 1208.45
  244.73 1208.75   260.7 1210.07  271.35  1210.1  281.99 1210.57  292.63 1211.84
   313.9 1213.56  319.22 1214.17  324.54 1214.92  335.18 1216.99  351.14    1219
  372.42 1220.81  383.06 1221.35  388.38 1221.97   393.7 1221.83  403.66 1221.15
#Mann= 3 , 0 , 0
       0     .09       0  191.53    .055       0  212.81     .09       0
#XS Ineff= 2 , 0
       0   178.8    1211   224.8       0    1211
Permanent Ineff=
       F       F
Bank Sta=191.53,212.81
Exp/Cntr=0.5,0.3

Type RM Length L Ch R = 2 ,23130   ,,,
BEGIN DESCRIPTION:
37003-0034 Culvert X-ing (SR #90)
END DESCRIPTION:
Bridge Culvert--1,0,-1,-1, 0
Deck Dist Width WeirC Skew NumUp NumDn MinLoCord MaxHiCord MaxSubmerge Is_Ogee
20,20,2.6,0, 75, 73, , , 0.95, 0, 0,0,,
       0    5.16    5.32   10.48   13.53   15.28   20.47   32.52   38.64   44.83
   53.85   59.04    66.5   72.22   81.77   85.89   93.04   98.03  108.34  109.04
  110.35  117.36  121.09  133.36  136.65  145.88   149.8  160.84   164.8  174.45
  176.47  186.61  190.91  199.48  200.52  202.17  202.88  204.88  208.31  215.51
  219.03  225.28  232.23  234.52  238.22  243.57  246.82  253.17  258.98  265.76
  273.47  281.51  285.89  294.75  300.82  309.49  314.48     322  328.98  331.91
  340.54  340.99  341.15  342.21  355.38  357.91  367.39  369.85  378.75  381.24
  381.91  384.56  395.46  400.93  408.82
 1214.68 1214.68 1214.66 1214.55 1214.37 1214.22 1214.09 1213.49 1213.27 1212.91
 1212.52 1212.34 1212.09 1211.92 1211.67 1211.54 1211.34 1211.19 1211.05 1211.05
    1211 1210.77  1210.7  1210.8 1210.78 1210.38 1210.36  1210.6 1210.64 1210.89
 1210.95 1210.73 1210.73 1210.73 1210.73 1210.73 1210.73 1210.73 1210.73 1211.24
 1211.27 1211.01 1211.21 1211.22 1211.48 1211.68 1211.75 1211.71 1211.93 1212.35
 1212.64 1213.08 1213.38 1213.77 1213.93 1214.28 1214.59 1214.73 1214.85 1214.98
 1215.54 1215.57 1215.58 1215.63 1216.19 1216.31 1216.79 1216.92 1217.28  1217.4
 1217.43 1217.58 1218.24 1218.57 1219.04
                                                                                
                                                                                
                                                                                
                                                                                
                                                                                
                                                                                
                                                                                
                                        
  -10.81  -10.65   -5.49   -2.44    -.69     4.5   16.55   22.67   28.86   37.88
   43.07   50.53   56.25    65.8   69.92   77.07   82.06   92.37   93.07   94.38
  101.39  105.12  117.39  120.68  129.91  133.83  144.87  148.83  158.48   160.5
  170.64  174.94  183.51  184.55   186.2  186.91  188.91  192.34  199.54  203.06
  209.31  216.26  218.55  222.25   227.6  230.85   237.2  243.01  249.79   257.5
  265.54  269.92  278.78  284.85  293.52  298.51  306.03  313.01  315.94  324.57
  325.02  325.18  326.24  339.41  341.94  351.42  353.88  362.78  365.27  365.94
  368.59  379.49  384.96
 1214.68 1214.66 1214.55 1214.37 1214.22 1214.09 1213.49 1213.27 1212.91 1212.52
 1212.34 1212.09 1211.92 1211.67 1211.54 1211.34 1211.19 1211.05 1211.05    1211
 1210.77  1210.7  1210.8 1210.78 1210.38 1210.36  1210.6 1210.64 1210.89 1210.95
 1210.73 1210.73 1210.73 1210.73 1210.73 1210.73 1210.73 1210.73 1211.24 1211.27
 1211.01 1211.21 1211.22 1211.48 1211.68 1211.75 1211.71 1211.93 1212.35 1212.64
 1213.08 1213.38 1213.77 1213.93 1214.28 1214.59 1214.73 1214.85 1214.98 1215.54
 1215.57 1215.58 1215.63 1216.19 1216.31 1216.79 1216.92 1217.28  1217.4 1217.43
 1217.58 1218.24 1218.57
                                                                                
                                                                                
                                                                                
                                                                                
                                                                                
                                                                                
                                                                                
                        
BR Coef=-1 , 0 , 0 ,, 0 ,,,0.8,-1,,0,
WSPro=,,,, 1 ,,,, 0 ,,,, 0 ,,,,-1 ,-1 ,-1 , 0 , 0 , 0 , 0 , 0
Culvert=2,6,6,30,0.013,0.4,1,8,1,1198.8,201.83,1198.7,189.13,Culvert #1  , 0 ,0
Culvert Bottom n=0.013
BR U #Sta/Elev= 72
       0 1213.66    5.32 1213.23   10.64 1212.96   15.96 1212.81   21.28 1212.68
    26.6  1212.5   31.92 1212.26   37.24 1212.04   47.88 1211.77    53.2 1211.66
   58.52 1211.57   63.84 1211.43   74.48 1211.05    79.8 1210.92   90.46  1210.8
  111.74 1210.46  117.06 1210.35  122.38  1210.2   127.7 1210.08  133.02    1210
  138.34 1209.99  143.66 1210.01  148.97 1210.01  159.61 1209.93  170.25  1209.9
  175.57 1209.87  180.89 1209.87  186.21 1208.97  191.53 1206.13  196.85 1201.34
     198    1200   198.1  1198.8  202.17  1198.8   204.9  1198.8     205    1200
  207.49  1202.1  212.81 1204.78  218.13 1206.34  223.45 1207.99  228.77 1208.65
  234.09 1208.45  239.41 1208.66  244.73 1208.75  250.05 1209.12   260.7 1210.07
  266.03 1210.17  271.35  1210.1  276.66  1210.3  281.99 1210.57  287.31 1211.13
  292.63 1211.84  297.95 1212.19  303.27 1212.63  308.58 1213.12   313.9 1213.56
  319.22 1214.17  324.54 1214.92  329.86 1215.89  335.18 1216.99   340.5 1217.67
  345.82 1218.39  351.14    1219  356.46 1219.49  361.78 1219.93   367.1 1220.26
  372.42 1220.81  377.74    1221  383.06 1221.35  388.38 1221.97   393.7 1221.83
  399.02  1221.4  403.66 1221.15
BR U #Mann= 3
       0      .1  191.53    .055  212.81      .1
BR U Banks=198,205
BR D #Sta/Elev= 71
       0 1213.93    5.32 1213.62   10.64 1213.45   26.59 1212.82   31.91 1212.66
   37.23 1212.46   42.55 1212.22   47.87 1212.01   58.51 1211.72   63.83 1211.53
   69.15  1211.3   74.47 1211.12   79.79 1211.03   85.12 1211.06   90.45 1211.05
   95.77 1210.86  101.08 1210.61  106.41 1210.45  111.73 1210.41  117.05 1210.41
  122.37 1210.34  127.69  1210.2  133.01 1210.09  138.33 1210.01  143.65 1209.95
  148.97 1209.94  154.29 1210.09  159.61 1210.18  164.93  1210.1  170.25 1209.98
  175.56 1209.02  180.88 1204.79     185    1201   186.2  1198.7  192.13  1198.7
     193    1201  196.84 1207.96  202.16 1209.97  207.48 1209.61   212.8 1210.14
  218.12 1210.53  223.44  1210.9  228.76 1211.15  234.08 1211.15  244.72 1211.49
  250.04 1211.61  255.37 1211.81   260.7  1212.1  266.02 1212.42  271.34 1212.66
  276.65 1212.95  281.98 1213.15   287.3 1213.37  303.26  1214.4  308.58 1214.64
   313.9 1214.76  319.22 1214.97  324.54 1215.23  329.86 1215.46  335.17 1215.72
  340.49 1216.02  345.81 1216.37  356.45    1217  367.09 1217.53  372.41 1217.74
  377.73 1218.03  383.05 1218.47  388.37 1218.88  393.69 1219.07  399.01 1219.24
  403.65 1219.44
BR D #Mann= 3
       0      .1  180.88    .055  196.84      .1
BR D Banks=185,193
BC Design=,, 0 ,, 0 ,,,,,,

Type RM Length L Ch R = 1 ,23114.9 ,69.96,81.28,69.85
XS GIS Cut Line= 2
  1358121.164138   797466.407859  1357741.808187   797604.355452
#Sta/Elev= 30
       0 1213.93   47.87 1212.01   74.47 1211.12   90.45 1211.05  106.41 1210.45
  122.37 1210.34  138.33 1210.01  148.97 1209.94  159.61 1210.18  170.25 1209.98
  175.56 1209.02  180.88 1204.79  182.36 1203.01   186.2  1198.3  191.52 1199.68
  193.59 1202.96  196.84 1207.96  202.16 1209.97  207.48 1209.61  218.12 1210.53
  228.76 1211.15  234.08 1211.15  255.37 1211.81   287.3 1213.37  303.26  1214.4
  335.17 1215.72  356.45    1217  377.73 1218.03  388.37 1218.88  403.65 1219.44
#Mann= 3 , 0 , 0
       0     .09       0  182.36    .055       0  193.59     .09       0
#XS Ineff= 2 , 0
       0     166  1206.4     212       0  1206.4
Permanent Ineff=
       F       F
Bank Sta=182.36,193.59
Exp/Cntr=0.5,0.3

Type RM Length L Ch R = 1 ,23033.62,88.54,87.22,109.26
XS GIS Cut Line= 3
  1358066.287864   797456.079165  1357918.529253   797453.873794
  1357878.391858   797497.539784
#Sta/Elev= 26
       0 1210.27      10 1210.08      35  1209.1   45.02 1208.85   80.01 1208.31
  100.01 1208.15  105.01 1207.67  110.01 1206.55  115.01 1205.24  120.01  1203.3
  125.01 1200.34  127.77 1198.85     130 1197.33  135.02 1195.13  140.02 1197.24
  141.61    1199  144.12 1201.92  145.02 1202.62  147.78 1204.06  154.57 1203.63
  174.94 1202.12  181.74 1202.17  188.52 1202.49  195.32 1203.13  202.11  1204.1
  207.09 1204.97
#Mann= 3 , 0 , 0
       0     .09       0  127.77    .055       0  141.61     .09       0
Bank Sta=127.77,141.61
Exp/Cntr=0.3,0.1

Type RM Length L Ch R = 1 ,22946.4 ,135.49,137.86,139.18
XS GIS Cut Line= 3
  1358132.883342   797361.320865  1357906.404132   797367.822661
  1357863.058796   797334.230042
#Sta/Elev= 28
       0 1210.23   40.02 1209.98   65.03 1209.58   80.02  1209.5   85.04 1209.42
  100.04 1208.98  125.05 1208.49  130.04 1208.28  145.06 1208.25  160.07 1208.06
  165.07 1207.82  170.07 1206.17  185.08 1199.25  190.08 1196.83  195.08 1193.05
  200.08 1193.04  205.07  1196.1  210.09  1198.6  215.09 1199.62  220.09 1199.98
  226.56 1200.65  239.22 1202.31  245.55  1203.6  251.88 1205.03   258.2 1206.84
  264.53 1208.88  277.18 1210.48  281.41 1210.87
#Mann= 3 , 0 , 0
       0     .09       0  190.08    .055       0  205.07     .09       0
Bank Sta=190.08,205.07
Exp/Cntr=0.3,0.1

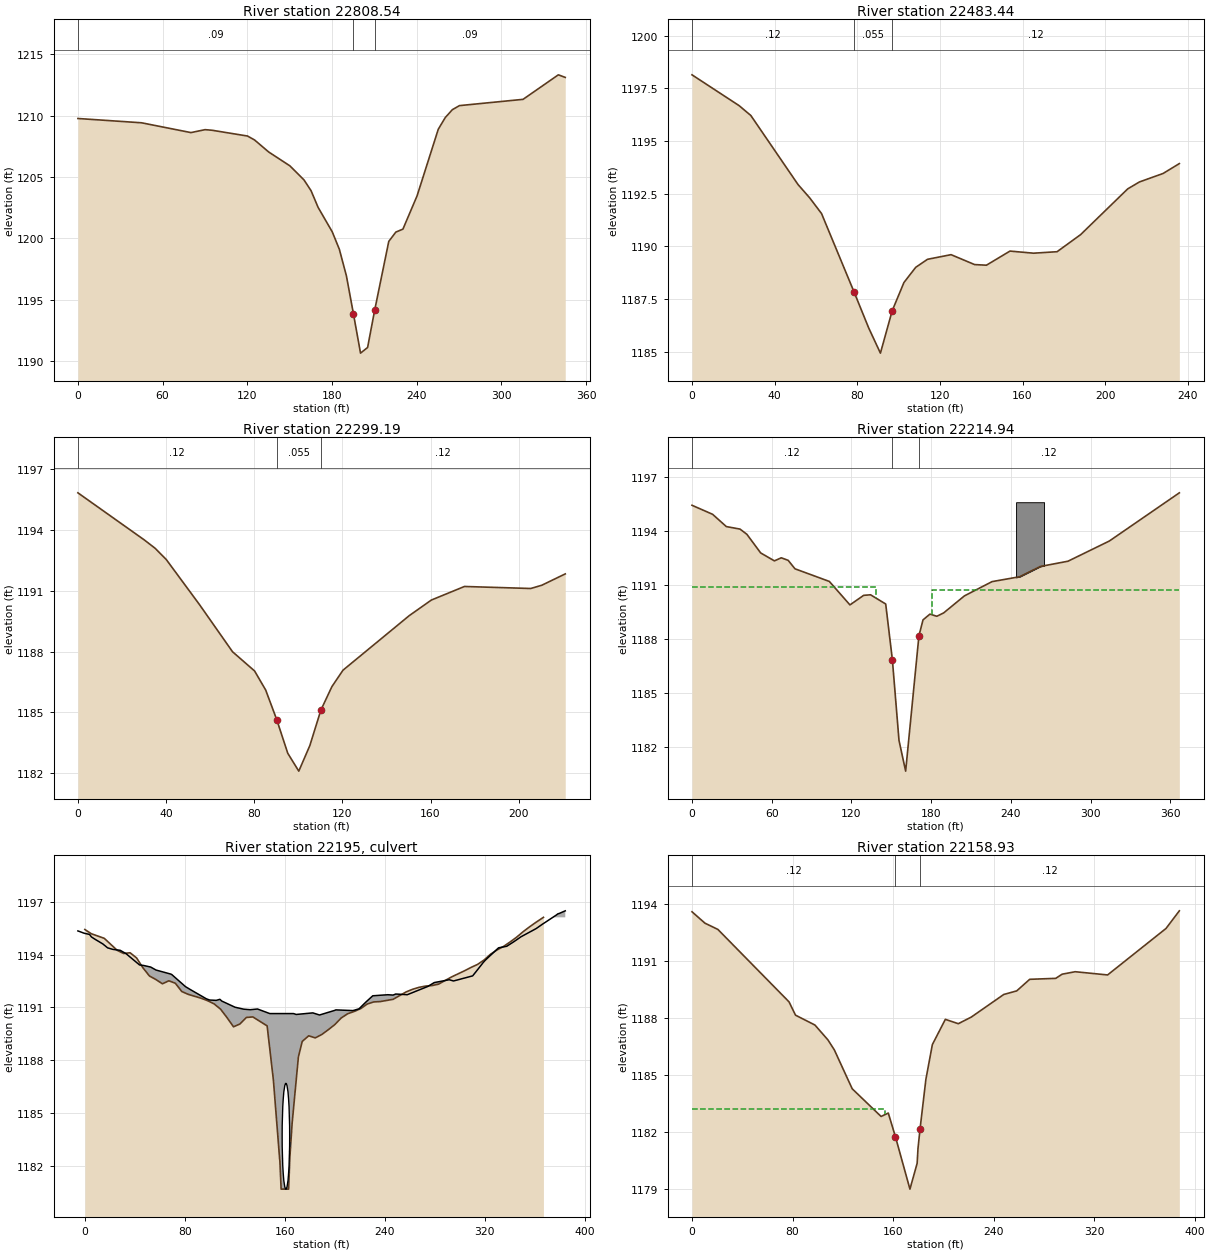
Type RM Length L Ch R = 1 ,22808.54,310.67,325.1,338.04
XS GIS Cut Line= 2
  1358149.492689    797239.77959  1357804.623613   797222.536153
#Sta/Elev= 30
       0 1209.78   45.06 1209.43    80.1 1208.63    90.1 1208.87   95.12 1208.82
  120.15 1208.35  125.16 1208.03  135.17 1207.05  150.19 1205.92   160.2 1204.77
  165.21 1203.89   170.2 1202.53  180.21 1200.54  185.23 1199.12  190.24 1196.95
  195.23 1193.85  200.25 1190.65  205.26 1191.11  210.25 1194.14  220.26 1199.76
  225.28 1200.52  230.29 1200.76   240.3 1203.47  255.32  1208.9  260.31 1209.86
  265.33  1210.5  270.34 1210.83  315.38 1211.34  340.41 1213.34   345.3 1213.13
#Mann= 3 , 0 , 0
       0     .09       0  195.23    .055       0  210.25     .09       0
Bank Sta=195.23,210.25
Exp/Cntr=0.3,0.1

Type RM Length L Ch R = 1 ,22483.44,196.87,184.25,169.97
XS GIS Cut Line= 2
  1358127.322508   796983.591143  1357920.401072   796870.277032
#Sta/Elev= 24
       0 1198.14   22.79 1196.68   28.49 1196.21    51.3 1192.94   57.01  1192.3
   62.71 1191.56   78.41 1187.85   85.51 1186.14   91.21 1184.94   96.91 1186.95
   102.6 1188.29   108.3 1189.01     114 1189.39   125.4 1189.61  136.81 1189.14
  142.51 1189.11  153.92 1189.78  165.32 1189.68  176.72 1189.75  188.11 1190.56
  210.91 1192.73  216.61 1193.06  228.02 1193.46  235.91 1193.93
#Mann= 3 , 0 , 0
       0     .12       0   78.41    .055       0   96.91     .12       0
Bank Sta=78.41,96.91
Exp/Cntr=0.3,0.1

Type RM Length L Ch R = 1 ,22299.19,91.1,84.25,77.08
XS GIS Cut Line= 2
  1358191.295149   796780.627269  1357970.674004   796765.669903
#Sta/Elev= 21
       0 1195.83   30.08 1193.51   35.08 1193.09   40.09 1192.54   55.14 1190.32
   70.16 1187.99   80.18 1187.04   85.21  1186.1   90.22 1184.64   95.23 1182.98
  100.23  1182.1  105.24 1183.36  110.25 1185.11  115.26 1186.27  120.29 1187.08
  150.34 1189.77  160.38 1190.54   175.4 1191.21  205.47 1191.11  210.48 1191.27
  221.14 1191.83
#Mann= 3 , 0 , 0
       0     .12       0   90.22    .055       0  110.25     .12       0
Bank Sta=90.22,110.25
Exp/Cntr=0.5,0.3

Type RM Length L Ch R = 1 ,22214.94,66.47,56.01,49.87
XS GIS Cut Line= 4
  1358259.321232   796653.275287  1358118.283278   796690.289771
  1358090.203297    796690.92796  1357904.492639   796743.258789
#Sta/Elev= 30
       0 1195.42   15.51 1194.92   25.85 1194.24   36.18  1194.1   41.34 1193.81
   51.69 1192.78   62.03 1192.34    67.2 1192.51   72.37 1192.37   77.54  1191.9
  103.39  1191.2  118.89  1189.9  129.23 1190.43   134.4 1190.46  145.81 1189.95
  150.82 1186.87  155.82 1182.39  160.82 1180.69  170.82 1188.19   173.9 1189.07
   179.1 1189.39  184.29 1189.27  189.49 1189.46  205.07  1190.4  225.85 1191.19
  246.63 1191.46  262.21 1192.03  282.99 1192.32  314.16 1193.44  366.84 1196.11
#Mann= 3 , 0 , 0
       0     .12       0  150.82    .055       0  170.82     .12       0
#XS Ineff= 2 , 0
       0   138.8  1190.9     181       0  1190.7
Permanent Ineff=
       F       F
#Block Obstruct= 1 ,-1
  243.94     265 1195.59
Bank Sta=150.82,170.82
Exp/Cntr=0.5,0.3

Type RM Length L Ch R = 2 ,22195   ,,,
BEGIN DESCRIPTION:
37003-0036 Culvert X-ing (1st Avenue Dr.)
END DESCRIPTION:
Bridge Culvert--1,0,-1,-1, 0
Deck Dist Width WeirC Skew NumUp NumDn MinLoCord MaxHiCord MaxSubmerge Is_Ogee
15,25,2.6,0, 67, 68, , , 0.95, 0, 0,0,,
   -5.57    -.62    3.75    5.24    7.81    14.4   18.17   22.51   28.26   32.94
   43.73   46.97   52.64   56.94    68.8   69.59   80.47   83.96   97.14   99.74
  105.07  108.05  109.54  120.15   127.1  132.28   138.1  147.96  157.28  157.82
  159.01  160.82  162.85  163.82  167.01  169.01  182.35   187.7  199.82  200.79
  214.49  219.33  224.74  230.31  242.37  246.58  248.68  257.93  261.04  274.38
  279.52  291.47  294.96  310.23  313.49   318.7   320.5   330.9  337.53  343.45
  348.95  360.96  365.81  376.92  378.61  379.13   384.3
 1195.34 1195.21 1195.14    1195 1194.88  1194.6 1194.38 1194.29 1194.24 1194.05
 1193.41 1193.38 1193.29 1193.12 1192.89 1192.86 1192.18 1192.03 1191.49 1191.42
  1191.4 1191.46 1191.36 1191.01  1190.9 1190.87 1190.91 1190.65 1190.65 1190.65
 1190.65 1190.65 1190.65 1190.65 1190.65  1190.6 1190.69 1190.57 1190.83 1190.86
 1190.82 1190.92  1191.3 1191.66 1191.72  1191.7 1191.76 1191.72 1191.81 1192.19
 1192.41 1192.57  1192.5 1192.79 1193.08 1193.55 1193.69 1194.38 1194.47 1194.74
 1195.01 1195.47 1195.71 1196.23 1196.32 1196.32 1196.48
                                                                                
                                                                                
                                                                                
                                                                                
                                                                                
                                                                                
                                                        
       0    6.57   11.52   15.89   17.38   19.95   26.54   30.31   34.65    40.4
   45.08   55.87   59.11   64.78   69.08   80.94   81.73   92.61    96.1  109.28
  111.88  117.21  120.19  121.68  132.29  139.24  144.42  150.24   160.1  169.42
  169.96  171.15  172.96  174.99  175.96  179.15  181.15  194.49  199.84  211.96
  212.93  226.63  231.47  236.88  242.45  254.51  258.72  260.82  270.07  273.18
  286.52  291.66  303.61   307.1  322.37  325.63  330.84  332.64  343.04  349.67
  355.59  361.09   373.1  377.95  389.06  390.75  391.27  396.44
 1195.34 1195.34 1195.21 1195.14    1195 1194.88  1194.6 1194.38 1194.29 1194.24
 1194.05 1193.41 1193.38 1193.29 1193.12 1192.89 1192.86 1192.18 1192.03 1191.49
 1191.42  1191.4 1191.46 1191.36 1191.01  1190.9 1190.87 1190.91 1190.65 1190.65
 1190.65 1190.65 1190.65 1190.65 1190.65 1190.65  1190.6 1190.69 1190.57 1190.83
 1190.86 1190.82 1190.92  1191.3 1191.66 1191.72  1191.7 1191.76 1191.72 1191.81
 1192.19 1192.41 1192.57  1192.5 1192.79 1193.08 1193.55 1193.69 1194.38 1194.47
 1194.74 1195.01 1195.47 1195.71 1196.23 1196.32 1196.32 1196.48
                                                                                
                                                                                
                                                                                
                                                                                
                                                                                
                                                                                
                                                                
BR Coef=-1 , 0 , 0 ,, 0 ,,,0.8,-1,,0,
WSPro=,,,, 1 ,,,, 0 ,,,, 0 ,,,,-1 ,-1 ,-1 , 0 , 0 , 0 , 0 , 0
Culvert=1,6,,50,0.027,0.9,1,2,3,1180.69,160.82,1178.99,173.28,Culvert #1  , 0 ,2.5
Culvert Bottom n=0.027
BR U #Sta/Elev= 68
       0 1195.42    5.17 1195.18   15.51 1194.92   25.85 1194.24   31.02 1194.06
   36.18  1194.1   41.34 1193.81   46.52 1193.24   51.69 1192.78   56.86 1192.58
   62.03 1192.34    67.2 1192.51   72.37 1192.37   77.54  1191.9   82.71 1191.74
   93.05 1191.52   98.22 1191.38  103.39  1191.2  108.55  1190.9  113.73 1190.42
  118.89  1189.9  124.06 1190.06  129.23 1190.43   134.4 1190.46  145.81 1189.95
  150.82 1186.87  155.82 1182.39     156 1182.29     157 1180.69  160.82 1180.69
     163 1180.69     164  1182.5  165.82 1184.43  170.82 1188.19   173.9 1189.07
   179.1 1189.39  184.29 1189.27  189.49 1189.46  194.68 1189.73  199.88 1190.02
  205.07  1190.4  210.26 1190.64  215.46 1190.77  220.66 1190.93  225.85 1191.19
  231.05 1191.31  236.24 1191.33  246.63 1191.46  257.02 1191.88  262.21 1192.03
  267.41 1192.14   272.6 1192.21   277.8 1192.24  282.99 1192.32  293.38 1192.73
  303.77 1193.08  308.96 1193.27  314.16 1193.44  319.35 1193.69  324.55 1194.02
  329.74 1194.26  334.94 1194.46  340.13 1194.71  345.33 1194.98  350.52 1195.29
  355.72 1195.57  360.91 1195.83  366.84 1196.11
BR U #Mann= 3
       0      .1  150.82    .055  165.82      .1
BR U Banks=156,164
BR D #Sta/Elev= 74
       0 1193.61    5.13  1193.3   10.29 1193.01   15.43 1192.84   20.58 1192.68
   25.71 1192.34      36  1191.6   46.29 1190.93   51.45 1190.57   56.58  1190.2
   61.74 1189.86   66.88  1189.5   72.03 1189.22   77.17 1188.86    82.3 1188.16
   87.46 1187.95    92.6 1187.86   97.75 1187.64  102.88 1187.23  108.04 1186.86
  113.17 1186.33  118.33  1185.6  123.46 1184.76  127.38 1184.28  133.13 1183.86
  138.85 1183.49  144.59 1183.23  150.34 1182.82  156.07    1183   161.8 1181.74
  167.55 1180.29     169  1180.2     170 1178.99  173.28 1178.99     177 1178.99
   177.5 1180.35  179.01 1180.35  185.97 1184.78  191.12 1186.61  196.29 1187.29
  201.44 1187.94   206.6 1187.81  211.76 1187.71  216.92  1187.9  222.08 1188.06
  227.23 1188.33   232.4 1188.63  247.87 1189.25  253.03 1189.32  258.19 1189.44
  263.36 1189.74  268.52 1190.05  273.68  1190.1     284 1190.09  289.16  1190.1
  294.32 1190.32  299.48 1190.41  304.64 1190.45   309.8 1190.42  314.96 1190.34
  320.12 1190.32  325.28 1190.32  330.44 1190.28   335.6 1190.48  340.76 1190.77
  345.92 1191.02  351.08 1191.33  356.24 1191.69   361.4    1192  366.56 1192.24
  371.72 1192.44  376.88 1192.73  382.04  1193.2  387.49 1193.66
BR D #Mann= 3
       0      .1  167.55    .055  179.01      .1
BR D Banks=169,177.5
BC Design=,, 0 ,, 0 ,,,,,,

Type RM Length L Ch R = 1 ,22158.93,71.76,82.84,87.8
XS GIS Cut Line= 4
  1358258.044854   796587.542632  1358134.237765   796617.537133
  1358083.183313   796646.255303  1357887.899963   796696.033377
#Sta/Elev= 30
       0 1193.61   10.29 1193.01   20.58 1192.68   77.17 1188.86    82.3 1188.16
   97.75 1187.64  108.04 1186.86  113.17 1186.33  127.38 1184.28  150.34 1182.82
  156.07    1183   161.8 1181.74  173.28 1178.99  179.01 1180.35   179.7 1181.14
  181.35 1182.18  185.97 1184.78  191.12 1186.61  201.44 1187.94  211.76 1187.71
  222.08 1188.06  247.87 1189.25  258.19 1189.44  268.52 1190.05  289.16  1190.1
  294.32 1190.32  304.64 1190.45  330.44 1190.28  376.88 1192.73  387.49 1193.66
#Mann= 3 , 0 , 0
       0     .12       0   161.8    .055       0  181.35     .12       0
#XS Ineff= 2 , 0
       0   153.7 1183.21               0
Permanent Ineff=
       F       F
Bank Sta=161.8,181.35
Exp/Cntr=0.5,0.3