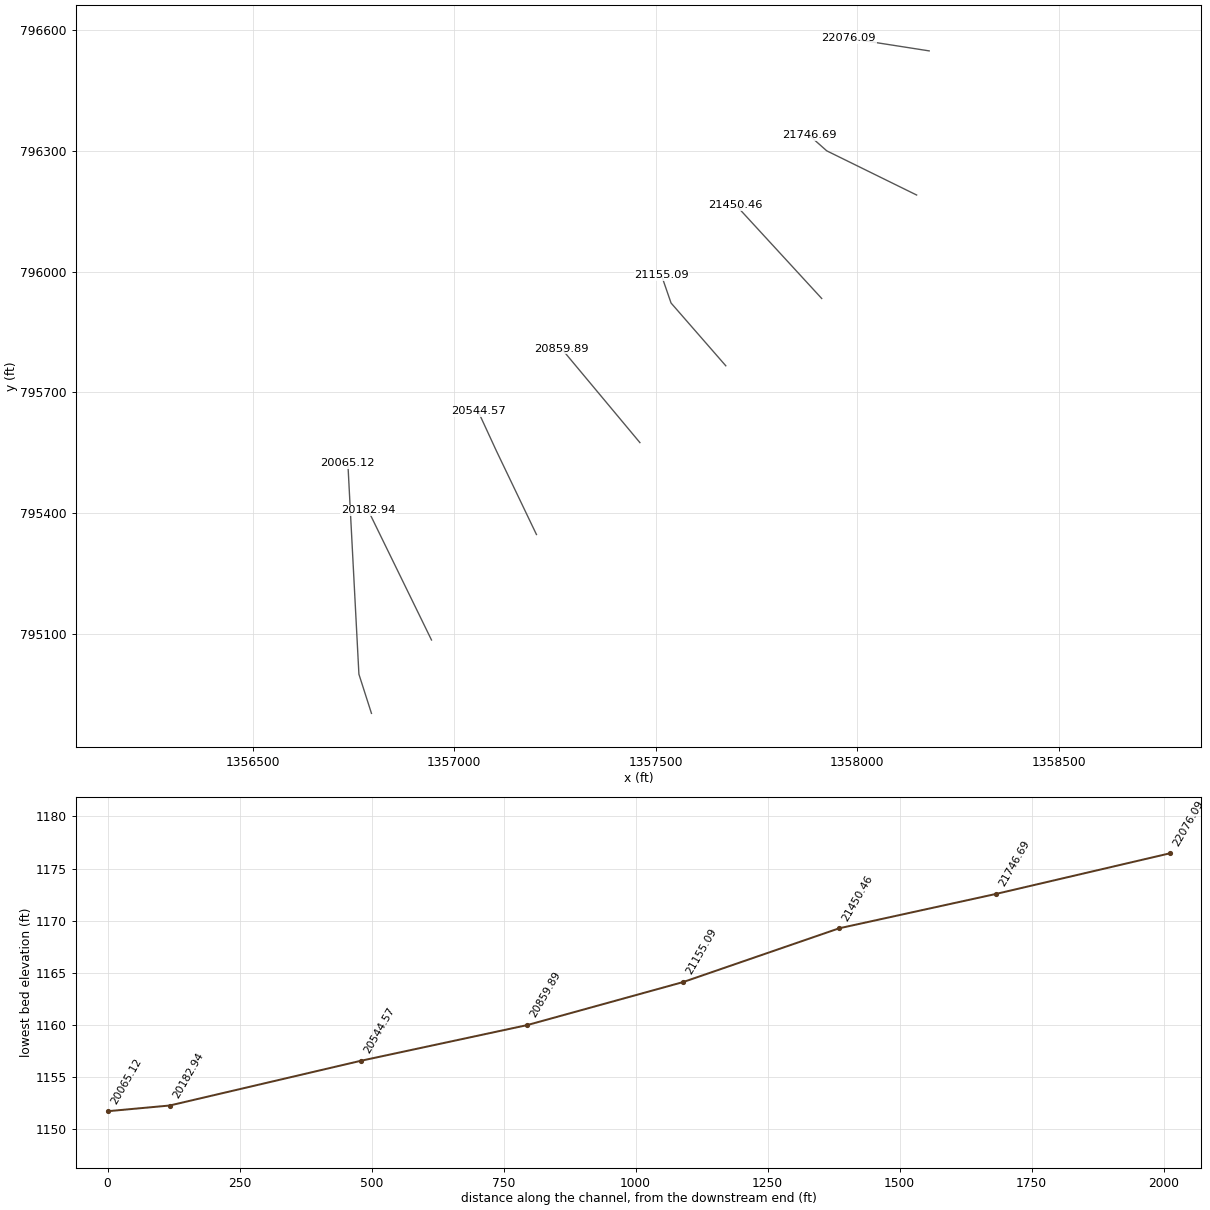
HEC-RAS study StirewaitCr.prj: StirewaitCr

--- StirewaitCr.g01 (geometry) --- (continued)

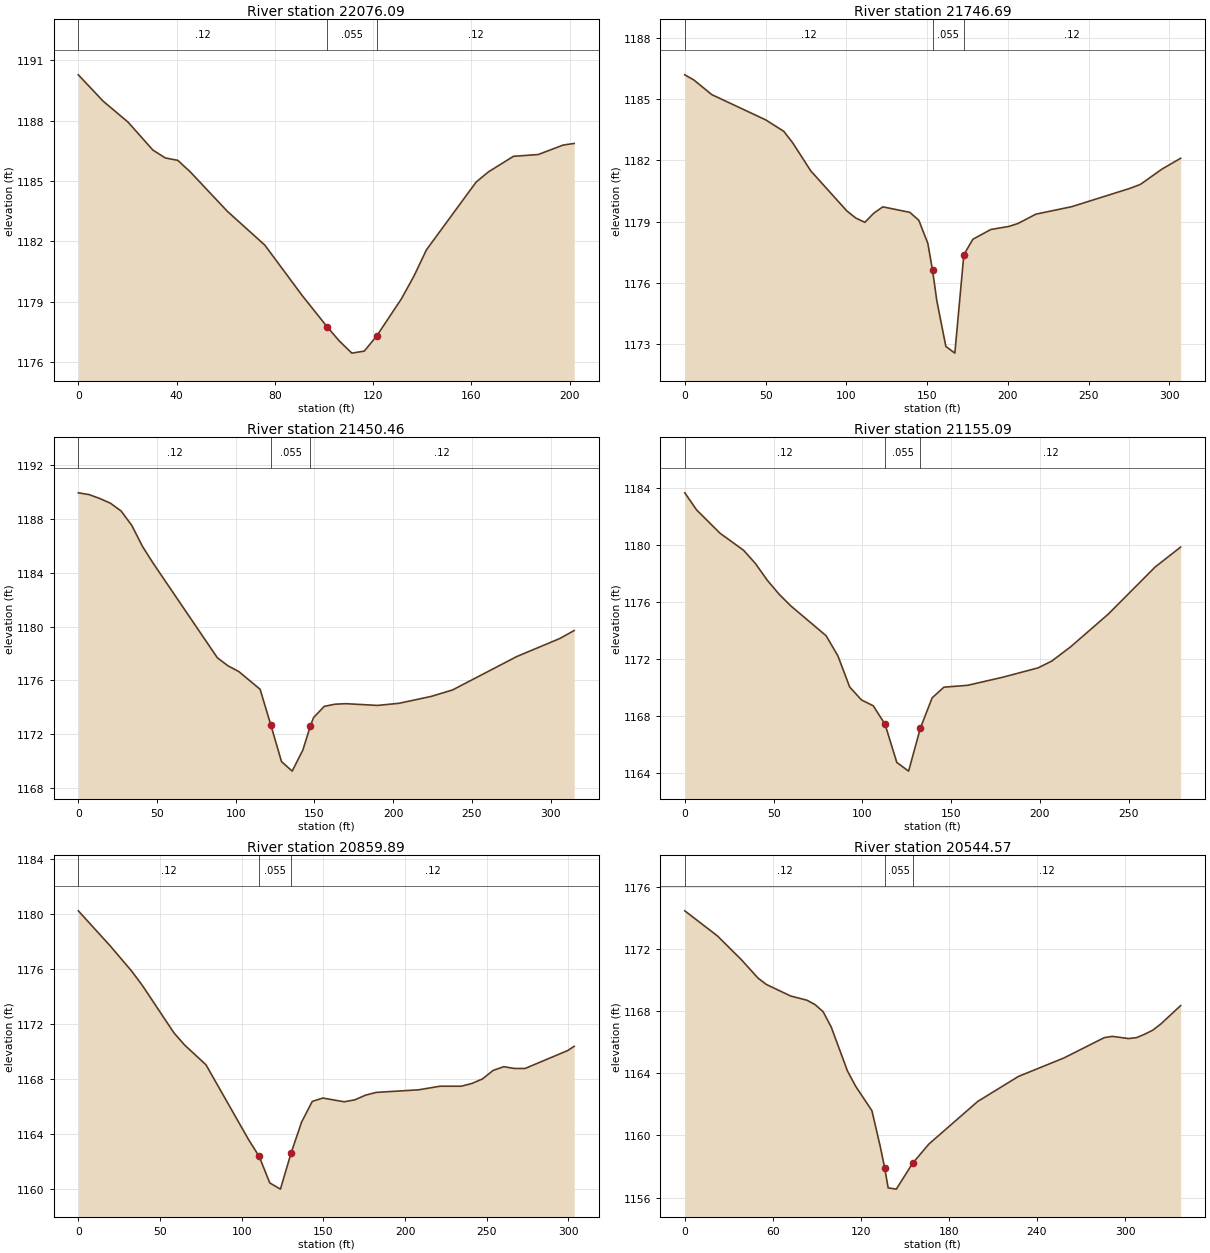
Type RM Length L Ch R = 1 ,22076.09,337.97,329.4,318.54
XS GIS Cut Line= 2
  1358178.830654   796547.541676  1357979.399146   796578.702844
#Sta/Elev= 24
       0 1190.28   10.12 1188.97   20.24 1187.93   30.36 1186.54   35.41 1186.15
   40.49 1186.03   45.55 1185.46   60.73 1183.49   75.91 1181.82   91.09 1179.32
  101.21 1177.77  106.27 1177.05  111.34 1176.45   116.4 1176.55  121.46  1177.3
  131.58 1179.16  136.64 1180.28   141.7 1181.58  161.94 1184.95     167 1185.46
  177.12 1186.23  187.25 1186.32  197.37 1186.79  201.85 1186.87
#Mann= 3 , 0 , 0
       0     .12       0  101.21    .055       0  121.46     .12       0
Bank Sta=101.21,121.46
Exp/Cntr=0.3,0.1

Type RM Length L Ch R = 1 ,21746.69,307.27,296.23,284.93
XS GIS Cut Line= 3
  1358147.669485   796189.811361  1357924.555469   796299.498669
  1357880.929805   796338.138544
#Sta/Elev= 30
       0 1186.19    5.57 1185.94   16.71 1185.22   50.14 1183.98   61.29 1183.42
   66.86 1182.85      78 1181.48  100.29 1179.52  105.86 1179.17  111.43 1178.96
     117 1179.41  122.58 1179.72  139.29 1179.45  144.86 1179.06  150.43 1177.93
  153.37  1176.6  156.01 1175.11  161.58 1172.88  167.15 1172.55  172.72 1177.37
  178.29 1178.13  189.43 1178.61  200.58 1178.76  206.15  1178.9  217.29 1179.36
  239.58 1179.73  275.34 1180.62  282.01 1180.82  295.36 1181.57   306.9  1182.1
#Mann= 3 , 0 , 0
       0     .12       0  153.37    .055       0  172.72     .12       0
Bank Sta=153.37,172.72
Exp/Cntr=0.3,0.1

Type RM Length L Ch R = 1 ,21450.46,295.58,295.37,292.93
XS GIS Cut Line= 2
  1357912.090974   795933.043259  1357698.948536   796164.882417
#Sta/Elev= 28
       0 1189.93    6.79  1189.8   13.58 1189.51   20.38 1189.16   27.17 1188.58
   33.96 1187.51   40.75 1185.95   47.54  1184.7    88.3 1177.68   95.09 1177.08
  101.88 1176.66  115.46 1175.34  122.25 1172.69  129.05 1169.97  135.83 1169.26
  142.63 1170.83   147.4 1172.62  149.42 1173.24  156.21 1174.07     163 1174.23
   169.8 1174.27  190.17 1174.14  203.76  1174.3  224.13 1174.81  237.72 1175.29
  278.47 1177.77  305.63  1179.1  314.93  1179.7
#Mann= 3 , 0 , 0
       0     .12       0  122.25    .055       0   147.4     .12       0
Bank Sta=122.25,147.4
Exp/Cntr=0.3,0.1

Type RM Length L Ch R = 1 ,21155.09,294.02,295.2,292.59
XS GIS Cut Line= 3
  1357674.019591   795766.019309  1357538.156857   795921.825199
  1357514.474348   795990.379807
#Sta/Elev= 27
       0 1183.69    6.63 1182.49    19.9 1180.84   33.17 1179.64    39.8 1178.71
   46.44 1177.54   53.07 1176.56   59.71 1175.73   79.61 1173.63   86.24 1172.21
   92.88 1170.02   99.51 1169.11  106.14  1168.7  112.78  1167.4  119.41 1164.71
  126.05  1164.1  132.68 1167.13  139.31 1169.26  145.95 1170.01  159.22 1170.14
  179.12 1170.71  199.02 1171.37  206.72 1171.85   217.3 1172.85  238.47 1175.15
  264.92 1178.47  279.25 1179.87
#Mann= 3 , 0 , 0
       0     .12       0  112.78    .055       0  132.68     .12       0
Bank Sta=112.78,132.68
Exp/Cntr=0.3,0.1

Type RM Length L Ch R = 1 ,20859.89,322.55,315.32,307.39
XS GIS Cut Line= 2
  1357460.877153   795575.312944  1357266.431388   795808.398538
#Sta/Elev= 30
       0  1180.2   19.53 1177.65   32.57 1175.83   39.07  1174.8    58.6 1171.32
   65.11 1170.44   78.15 1169.01  104.18 1163.58  110.69 1162.35  117.22 1160.42
  123.73 1159.97  130.24 1162.59  136.74 1164.86  143.25 1166.35  149.76 1166.59
  162.79 1166.32  169.31 1166.46  175.82  1166.8  182.32    1167  208.37 1167.19
   221.4 1167.45  234.41 1167.45  240.92 1167.65  247.43 1167.98  253.95  1168.6
  260.47 1168.87  266.98 1168.74  273.49 1168.74  299.52 1170.04  303.55 1170.35
#Mann= 3 , 0 , 0
       0     .12       0  110.69    .055       0  130.24     .12       0
Bank Sta=110.69,130.24
Exp/Cntr=0.3,0.1

Type RM Length L Ch R = 1 ,20544.57,360.17,361.63,361.54
XS GIS Cut Line= 3
  1357204.109051   795347.213093  1357104.393274   795555.369789
  1357059.521175   795652.592648
#Sta/Elev= 30
       0 1174.45   22.19 1172.84   38.81 1171.28   49.91 1170.12   55.44 1169.72
   72.07 1168.97   83.16  1168.7   88.72 1168.42   94.25 1167.96   99.79 1166.97
  110.88 1164.14  116.44 1163.16  127.51 1161.59  133.06 1159.34  136.19 1157.92
   138.6 1156.62  144.15 1156.54  155.23  1158.2  166.32 1159.44  199.59 1162.18
  227.31 1163.79  258.34 1164.98  285.88 1166.29  291.38 1166.37   302.4 1166.23
   307.9 1166.29  313.41 1166.51  318.92 1166.77  324.42 1167.17  337.89 1168.35
#Mann= 3 , 0 , 0
       0     .12       0  136.19    .055       0  155.23     .12       0
Bank Sta=136.19,155.23
Exp/Cntr=0.3,0.1

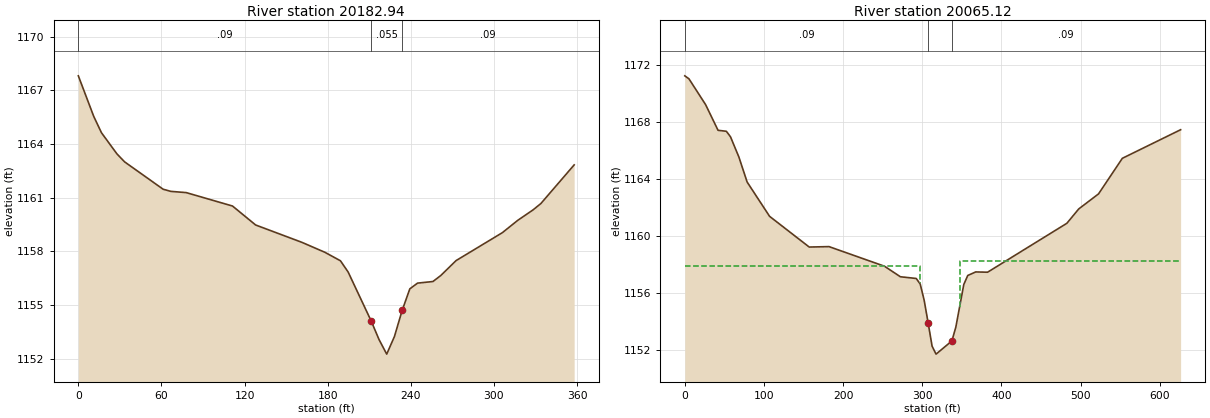
Type RM Length L Ch R = 1 ,20182.94,130.01,117.82,103.29
XS GIS Cut Line= 2
  1356943.601596   795085.459202   1356786.54927   795407.042559
#Sta/Elev= 29
       0 1167.81   11.13 1165.54   16.69 1164.63   27.82 1163.45   33.39    1163
   61.21 1161.47   66.77 1161.35    77.9 1161.28  111.29 1160.53  127.98 1159.47
  161.37  1158.5  178.06 1157.94  189.19 1157.47  194.75 1156.84  211.45 1154.09
  217.01 1153.07  222.58 1152.25  228.14 1153.23  233.72 1154.69  239.27  1155.9
  244.83 1156.22  255.96 1156.31  261.53 1156.64  272.66 1157.48  306.04 1159.04
  317.17 1159.73   328.3 1160.32  333.86 1160.67  357.88 1162.83
#Mann= 3 , 0 , 0
       0     .09       0  211.45    .055       0  233.72     .09       0
Bank Sta=211.45,233.72
Exp/Cntr=0.5,0.3

Type RM Length L Ch R = 1 ,20065.12,73.13,69.26,71.54
XS GIS Cut Line= 3
  1356794.617783   794903.315137  1356763.456568   795000.537996
  1356736.034753   795524.045778
#Sta/Elev= 30
       0 1171.27    5.24 1171.06   26.24 1169.25   41.99 1167.44   52.51 1167.37
   57.76 1166.98   68.26 1165.57   78.76  1163.8   107.1 1161.39  157.17 1159.23
  182.19 1159.26   252.3 1157.88  272.33 1157.14  292.35 1157.02  297.36 1156.63
  302.37 1155.49  307.37  1153.9  312.38 1152.26  317.39  1151.7  337.41 1152.63
  342.41 1153.61  352.43  1156.6  357.43 1157.23  367.46 1157.48  382.48 1157.46
  482.61  1160.9  497.63 1161.91  522.67 1162.97  552.71 1165.47  626.32 1167.48
#Mann= 3 , 0 , 0
       0     .09       0  307.37    .055       0  337.41     .09       0
#XS Ineff= 2 , 0
       0   296.8 1157.93     347       0 1158.22
Permanent Ineff=
       F       F
Bank Sta=307.37,337.41
Exp/Cntr=0.5,0.3