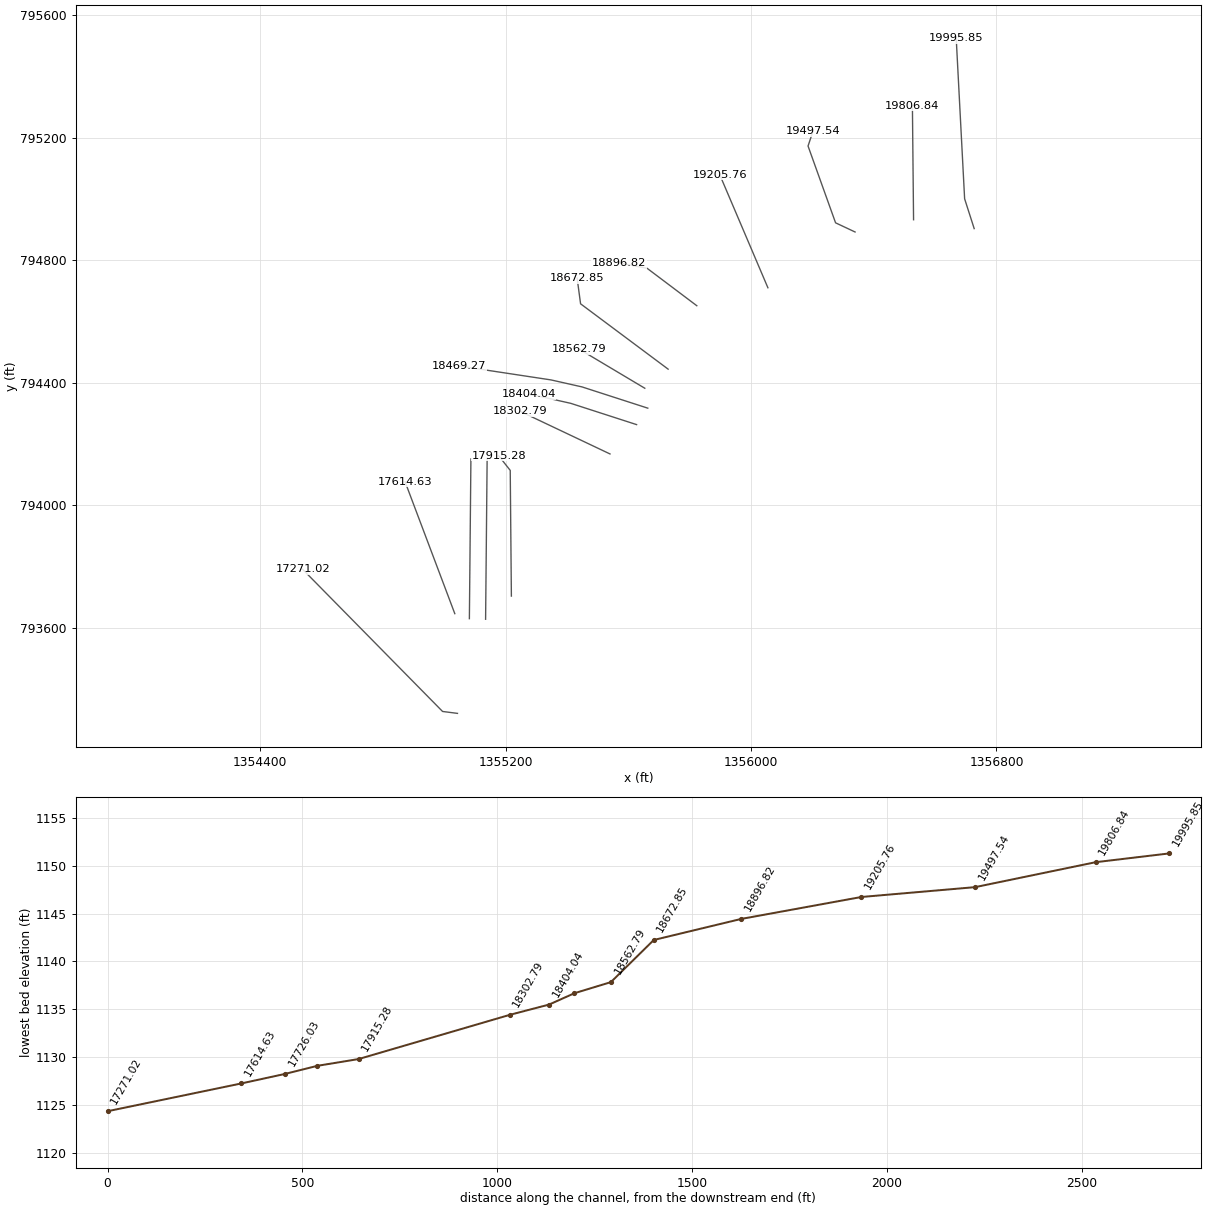
HEC-RAS study StirewaitCr.prj: StirewaitCr

--- StirewaitCr.g01 (geometry) --- (continued)

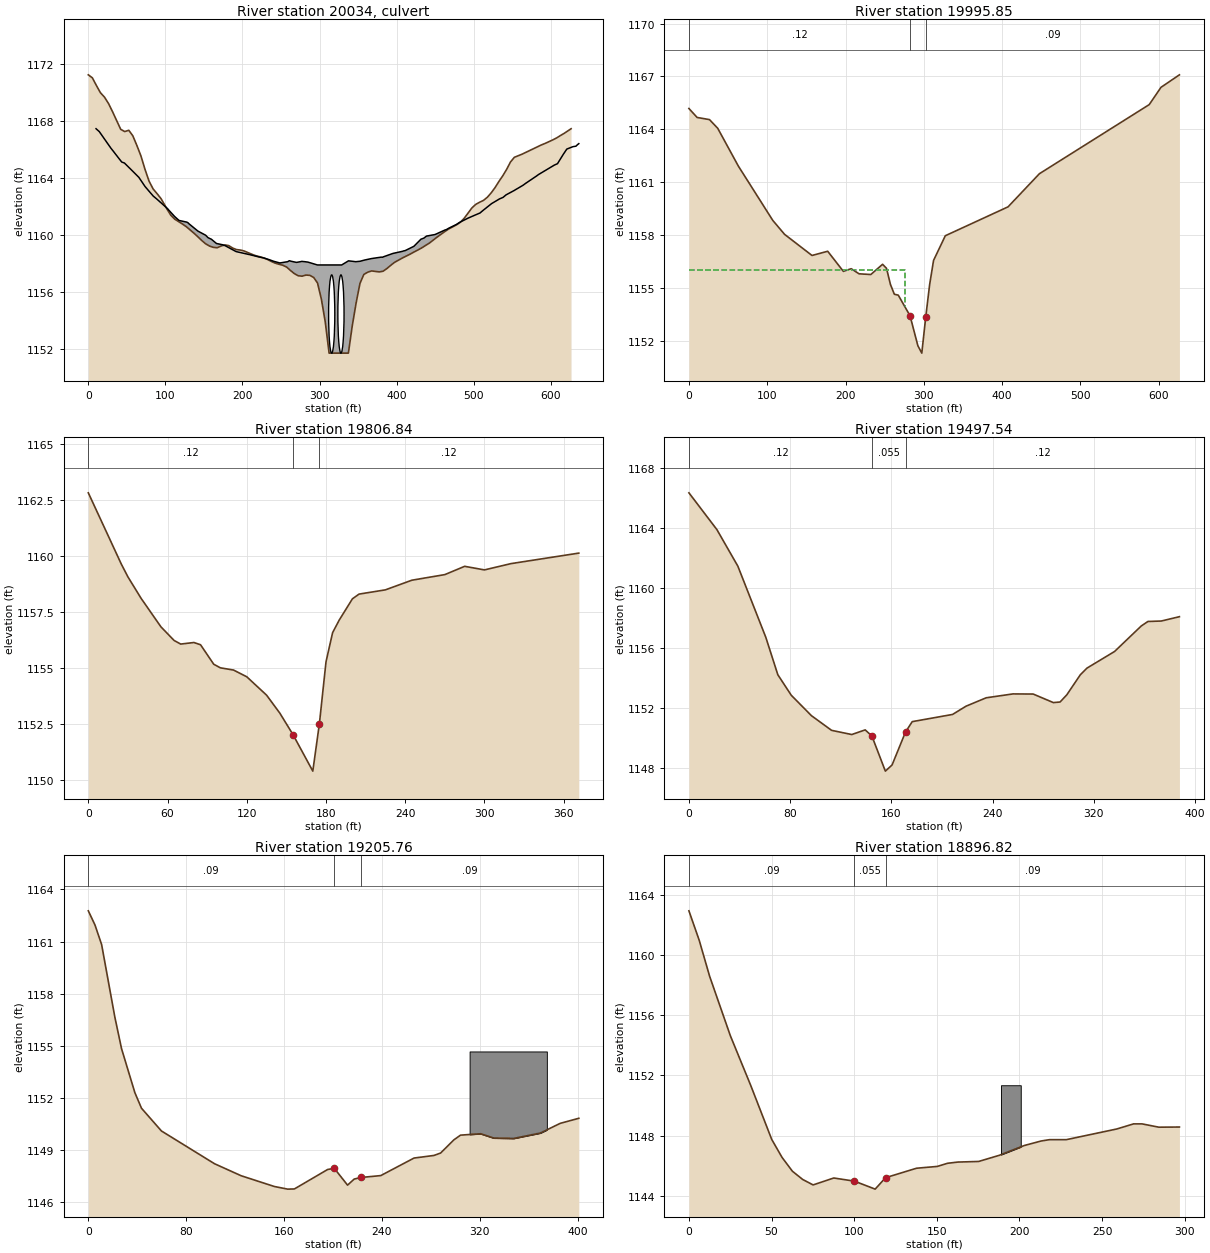
Type RM Length L Ch R = 2 ,20034   ,,,
BEGIN DESCRIPTION:
37003-0039 Culvert X-ing (Center St.)
END DESCRIPTION:
Bridge Culvert--1,0,-1,-1, 0
Deck Dist Width WeirC Skew NumUp NumDn MinLoCord MaxHiCord MaxSubmerge Is_Ogee
15,20,2.6,0, 98, 98, , , 0.95, 0, 0,0,,
   10.02    14.2   27.76   28.37    28.5   43.28   46.81   58.59   65.57   73.67
   84.11   88.97  102.98  104.33  110.24  112.11  117.65  127.91  129.45  130.49
  142.23  152.24  155.28  159.63  166.28  174.35  176.18  177.71  191.74  208.06
  208.62   209.7  221.66  227.75  234.82  240.42  248.43   258.6  260.86  263.13
  270.11  277.04  280.87  284.95  297.24  307.95  312.22  314.32   314.9  317.39
  318.47  320.78  323.68  328.69  337.51  346.99  352.53  358.75  367.39  379.98
  381.48  382.67  395.13  407.63  409.18   411.1  422.32  431.49  435.35  438.69
  449.79   462.8  464.25  467.83  477.62  481.53  492.54     504  508.03  511.97
  523.06   533.6  538.02  541.99  552.27  563.84  567.13  581.34  584.14  584.44
  604.51  608.66  616.43   620.8  628.83  632.57  634.65  636.34
 1167.48 1167.28 1166.23 1166.19 1166.17 1165.14 1165.07 1164.44 1164.06 1163.41
 1162.75 1162.53 1161.85 1161.76 1161.41  1161.3 1161.03 1160.91 1160.86  1160.8
 1160.28 1159.99 1159.82 1159.71 1159.41 1159.32 1159.28 1159.25 1158.84 1158.64
 1158.64 1158.62 1158.46 1158.39 1158.27 1158.16 1158.04 1158.13  1158.2 1158.16
 1158.08 1158.15 1158.13  1158.1  1157.9  1157.9  1157.9  1157.9  1157.9  1157.9
  1157.9  1157.9  1157.9  1157.9 1158.19 1158.13 1158.16 1158.25 1158.35 1158.45
 1158.44 1158.47 1158.71 1158.86 1158.89 1158.91 1159.21 1159.71 1159.79 1159.93
 1160.04 1160.36 1160.38 1160.49 1160.75 1160.89 1161.19 1161.46 1161.55 1161.73
 1162.21 1162.55 1162.65 1162.83 1163.13  1163.5 1163.63 1164.15 1164.26 1164.27
 1164.92 1165.02  1165.7 1166.05 1166.22 1166.25 1166.36 1166.43
                                                                                
                                                                                
                                                                                
                                                                                
                                                                                
                                                                                
                                                                                
                                                                                
                                                                                
                                                                
  -10.02   -5.84    7.72    8.33    8.46   23.24   26.77   38.55   45.53   53.63
   64.07   68.93   82.94   84.29    90.2   92.07   97.61  107.87  109.41  110.45
  122.19   132.2  135.24  139.59  146.24  154.31  156.14  157.67   171.7  188.02
  188.58  189.66  201.62  207.71  214.78  220.38  228.39  238.56  240.82  243.09
  250.07     257  260.83  264.91   277.2  287.91  292.18  294.28  294.86  297.35
  298.43  300.74  303.64  308.65  317.47  326.95  332.49  338.71  347.35  359.94
  361.44  362.63  375.09  387.59  389.14  391.06  402.28  411.45  415.31  418.65
  429.75  442.76  444.21  447.79  457.58  461.49   472.5  483.96  487.99  491.93
  503.02  513.56  517.98  521.95  532.23   543.8  547.09   561.3   564.1   564.4
  584.47  588.62  596.39  600.76  608.79  612.53  614.61   616.3
 1167.48 1167.28 1166.23 1166.19 1166.17 1165.14 1165.07 1164.44 1164.06 1163.41
 1162.75 1162.53 1161.85 1161.76 1161.41  1161.3 1161.03 1160.91 1160.86  1160.8
 1160.28 1159.99 1159.82 1159.71 1159.41 1159.32 1159.28 1159.25 1158.84 1158.64
 1158.64 1158.62 1158.46 1158.39 1158.27 1158.16 1158.04 1158.13  1158.2 1158.16
 1158.08 1158.15 1158.13  1158.1  1157.9  1157.9  1157.9  1157.9  1157.9  1157.9
  1157.9  1157.9  1157.9  1157.9 1158.19 1158.13 1158.16 1158.25 1158.35 1158.45
 1158.44 1158.47 1158.71 1158.86 1158.89 1158.91 1159.21 1159.71 1159.79 1159.93
 1160.04 1160.36 1160.38 1160.49 1160.75 1160.89 1161.19 1161.46 1161.55 1161.73
 1162.21 1162.55 1162.65 1162.83 1163.13  1163.5 1163.63 1164.15 1164.26 1164.27
 1164.92 1165.02  1165.7 1166.05 1166.22 1166.25 1166.36 1166.43
                                                                                
                                                                                
                                                                                
                                                                                
                                                                                
                                                                                
                                                                                
                                                                                
                                                                                
                                                                
BR Coef=-1 , 0 , 0 ,, 0 ,,,0.8,-1,,0,
WSPro=,,,, 1 ,,,, 0 ,,,, 0 ,,,,-1 ,-1 ,-1 , 0 , 0 , 0 , 0 , 0
Multiple Barrel Culv=4,5.5,8,50,0.017,0.5,1,29,1,1151.7,1151.66, 2,Culvert #1  , 0 ,5
  315.75  295.25  327.75  307.25
Culvert Bottom n=0.017
BR U #Sta/Elev= 105
       0 1171.27    5.24 1171.06   10.49 1170.52   15.74 1170.01   20.99  1169.7
   26.24 1169.25    31.5 1168.67   41.99 1167.44   47.24 1167.28   52.51 1167.37
   57.76 1166.98   63.01  1166.3   68.26 1165.57   73.51 1164.63   78.76  1163.8
   84.01 1163.25   89.26 1162.91   94.51 1162.55  102.08 1161.83   107.1 1161.39
  112.11 1161.12  122.12 1160.78  127.13 1160.59  137.14 1160.13  142.15 1159.88
  147.15 1159.62  152.15 1159.39  157.17 1159.23  162.17 1159.14  167.17 1159.11
  172.19 1159.23  177.19 1159.31  182.19 1159.26  187.21 1159.09  192.22 1158.98
  197.21 1158.95  202.23 1158.88  212.24 1158.65  217.25 1158.55  222.26 1158.48
  227.26  1158.4  232.27 1158.29  237.28 1158.15  242.28 1158.03  247.28 1157.95
   252.3 1157.88   257.3 1157.75   262.3 1157.51  267.32 1157.29  272.33 1157.14
  277.32 1157.11  282.34 1157.19  287.35 1157.17  292.35 1157.02  297.36 1156.63
  302.37 1155.49  307.37  1153.9  312.38  1151.7  317.39  1151.7  322.39  1151.7
  332.41  1151.7  337.41  1151.7  342.41 1153.61  347.43 1155.22  352.43  1156.6
  357.43 1157.23  362.45 1157.39  367.46 1157.48  377.47 1157.41  382.48 1157.46
  387.48 1157.65  392.49 1157.88   397.5 1158.09  407.51 1158.39  417.52 1158.66
  422.52 1158.81  427.54 1158.95  432.54  1159.1  442.56 1159.44  452.56 1159.86
  462.59 1160.25  467.58 1160.43  477.61 1160.72  482.61  1160.9  487.62 1161.18
  497.63 1161.91  502.64 1162.16  507.65 1162.31  512.65 1162.44  517.65 1162.66
  522.67 1162.97  527.68 1163.34  532.67 1163.77  537.69 1164.17   542.7 1164.62
  547.69 1165.14  552.71 1165.47  562.72 1165.69  587.76 1166.34  592.76 1166.45
  602.78  1166.7  607.78 1166.84  612.78 1167.01   617.8 1167.17  626.32 1167.48
BR U #Mann= 3
       0      .1  307.37    .055  322.39      .1
BR U Banks=,342.41
BR D #Sta/Elev= 99
       0 1165.18    5.24 1164.92   10.49 1164.67   15.74  1164.6   20.99 1164.65
   26.24 1164.55   31.49 1164.33   36.74 1164.06   41.99 1163.69   47.24 1163.28
    52.5 1162.81   63.01 1161.92   73.51 1161.23   84.01 1160.48   89.26 1160.19
   94.51 1159.71  102.08 1159.17   107.1 1158.83  117.11 1158.28  122.12 1158.04
  127.13 1157.85  132.13  1157.7  137.14 1157.52  142.15 1157.29  147.15  1157.1
  152.15 1156.95  157.17 1156.84  162.17  1156.8  167.17 1156.89  172.19 1157.02
  177.19 1157.08  182.19  1156.9  192.22 1156.11  197.21 1155.94  202.23 1156.07
  207.24 1156.09  217.25  1155.8  227.26 1155.73  232.27 1155.76  237.28 1155.95
  242.28 1156.17  247.28 1156.34   252.3 1156.11   257.3  1155.2   262.3 1154.64
  267.32 1154.59  272.32 1154.21  277.32 1153.77  282.34 1153.42  287.35  1152.7
  292.35 1151.66  297.36 1151.66  302.37 1151.66     311 1151.66  312.38  1152.6
  317.39 1157.03  322.39 1157.63  327.39 1157.96  332.41    1158  337.41 1158.05
  342.41 1158.14  352.43 1158.41  367.46 1158.77  372.45  1158.9  387.48 1159.18
   397.5 1159.35   402.5 1159.45  407.51  1159.6  412.52  1159.8  417.52 1160.04
  422.52 1160.27  427.54 1160.49  437.54 1160.95  442.56 1161.23  447.56 1161.48
  452.56 1161.65  467.58 1161.95   472.6 1162.06  477.61 1162.18  487.62  1162.5
  492.63 1162.62  502.64 1162.92  517.65 1163.38  527.67 1163.66  532.67 1163.81
  537.69    1164   542.7 1164.16  552.71 1164.44  567.73 1164.83  577.74  1165.1
  587.76  1165.4  592.76 1165.63  597.76 1166.02  602.78 1166.38  607.78 1166.57
  612.78  1166.7   617.8 1166.81  622.81 1166.94  626.32 1167.09
BR D #Mann= 3
       0      .1  287.35    .055  302.37      .1
BR D Banks=,312.38
BC Design=,, 0 ,, 0 ,,,,,,

Type RM Length L Ch R = 1 ,19995.85,185.76,189.01,186.83
XS GIS Cut Line= 3
  1356727.432545   794903.315137   1356696.27133   795000.537996
  1356668.849515   795524.045778
#Sta/Elev= 30
       0 1165.18   10.49 1164.67   26.24 1164.55   36.74 1164.06   63.01 1161.92
   107.1 1158.83  122.12 1158.04  157.17 1156.84  177.19 1157.08  197.21 1155.94
  207.24 1156.09  217.25  1155.8  232.27 1155.76  247.28 1156.34   252.3 1156.11
   257.3  1155.2   262.3 1154.64  267.32 1154.59  282.34 1153.42  292.35 1151.72
  297.36  1151.3  302.37 1153.34  307.37 1155.19  312.38 1156.56  327.39 1157.96
  407.51  1159.6  447.56 1161.48  587.76  1165.4  602.78 1166.38  626.32 1167.09
#Mann= 3 , 0 , 0
       0     .12       0  282.34    .055       0  302.37     .09       0
#XS Ineff= 2 , 0
       0     276    1156     326       0    1156
Permanent Ineff=
       F       F
#Block Obstruct= 2 , 0
       0                  350.18       0 1161.43
Bank Sta=282.34,302.37
Exp/Cntr=0.5,0.3

Type RM Length L Ch R = 1 ,19806.84,297.28,309.3,318.4
XS GIS Cut Line= 2
  1356529.781168    794932.14623  1356526.041815   795303.587476
#Sta/Elev= 30
       0  1162.8   24.99 1159.62   29.99 1159.05   39.99 1158.09   54.99 1156.82
   64.99 1156.21   69.99 1156.05   79.99 1156.12   84.99 1156.02   94.99 1155.15
  100.01 1154.99  110.01 1154.89  120.01 1154.59  135.01 1153.77  145.01 1152.97
  155.01 1152.01  170.01 1150.38  175.01  1152.5  180.01 1155.26  185.01 1156.56
  190.01 1157.12  200.01 1158.07  205.01 1158.28     225 1158.47     245  1158.9
     270 1159.15     285 1159.52  300.02 1159.36  320.02 1159.64  371.46 1160.11
#Mann= 3 , 0 , 0
       0     .12       0  155.01    .055       0  175.01     .12       0
#Block Obstruct= 2 , 0
       0                   279.3       0 1161.57
Bank Sta=155.01,175.01
Exp/Cntr=0.3,0.1

Type RM Length L Ch R = 1 ,19497.54,290.02,291.78,293.53
XS GIS Cut Line= 4
  1356339.074756   794892.259919  1356275.505937   794922.174652
  1356185.761738    795172.71053  1356201.965587   795221.321936
#Sta/Elev= 30
       0 1166.33   22.09 1163.88   38.67 1161.44   60.78 1156.69   70.25  1154.2
   80.88 1152.83    96.8 1151.47  112.74 1150.49  128.68 1150.21  139.29 1150.52
   144.6 1150.11  155.23 1147.77  160.54 1148.18  171.17 1150.38  176.48 1151.07
  208.34 1151.55  218.97  1152.1   234.9 1152.66  256.14 1152.92  272.08 1152.91
  288.01 1152.34  293.32 1152.38  298.63 1152.86  309.26 1154.19  314.57 1154.64
  336.38 1155.75  357.46 1157.45  362.73 1157.75  373.27 1157.78  387.62 1158.07
#Mann= 3 , 0 , 0
       0     .12       0   144.6    .055       0  171.17     .12       0
Bank Sta=144.6,171.17
Exp/Cntr=0.3,0.1

Type RM Length L Ch R = 1 ,19205.76,292.98,308.94,324.6
XS GIS Cut Line= 2
  1356054.884792    794710.27865  1355897.832467   795079.226978
#Sta/Elev= 30
       0 1162.77    5.42 1161.96   10.87 1160.83   21.74 1156.63   27.17 1154.83
   38.04  1152.3   43.47  1151.4   59.77 1150.09  103.25  1148.2  124.98 1147.51
  152.15 1146.89  163.02 1146.74  168.46 1146.75  195.63 1147.87  201.06 1147.94
  211.93 1146.97  217.36 1147.32   222.8 1147.41   239.1 1147.52  266.27 1148.53
  282.58 1148.68  288.01 1148.82  298.88 1149.58  304.31 1149.85  320.61 1149.93
  331.48 1149.68  347.79 1149.66  369.52 1149.97  385.82 1150.53  400.98 1150.82
#Mann= 3 , 0 , 0
       0     .09       0  201.06    .055       0   222.8     .09       0
#Block Obstruct= 1 ,-1
   311.7  374.85 1154.67
Bank Sta=201.06,222.8
Exp/Cntr=0.3,0.1

Type RM Length L Ch R = 1 ,18896.82,223.74,223.97,224.14
XS GIS Cut Line= 3
  1355823.045634   794651.695619   1355661.00752   794773.847422
   1355568.77045   794791.297707
#Sta/Elev= 29
       0 1162.95    6.26 1160.98   12.52  1158.6   25.05 1154.65   37.57 1151.29
   50.09 1147.75   56.35 1146.55   62.62 1145.63   68.88 1145.08   75.14 1144.72
   87.66 1145.18  100.18 1144.97   112.7 1144.44  118.97  1145.2  137.75 1145.83
  150.28 1145.95  156.54 1146.16  162.79 1146.24  175.32 1146.28  187.84 1146.69
  202.92 1147.34   213.1 1147.64  218.19 1147.73  228.37 1147.73   258.9 1148.44
  269.08 1148.78  274.16 1148.78  284.34 1148.56   296.8 1148.57
#Mann= 3 , 0 , 0
       0     .09       0  100.18    .055       0  118.97     .09       0
#Block Obstruct= 1 ,-1
  188.84  200.79 1151.35
Bank Sta=100.18,118.97
Exp/Cntr=0.3,0.1

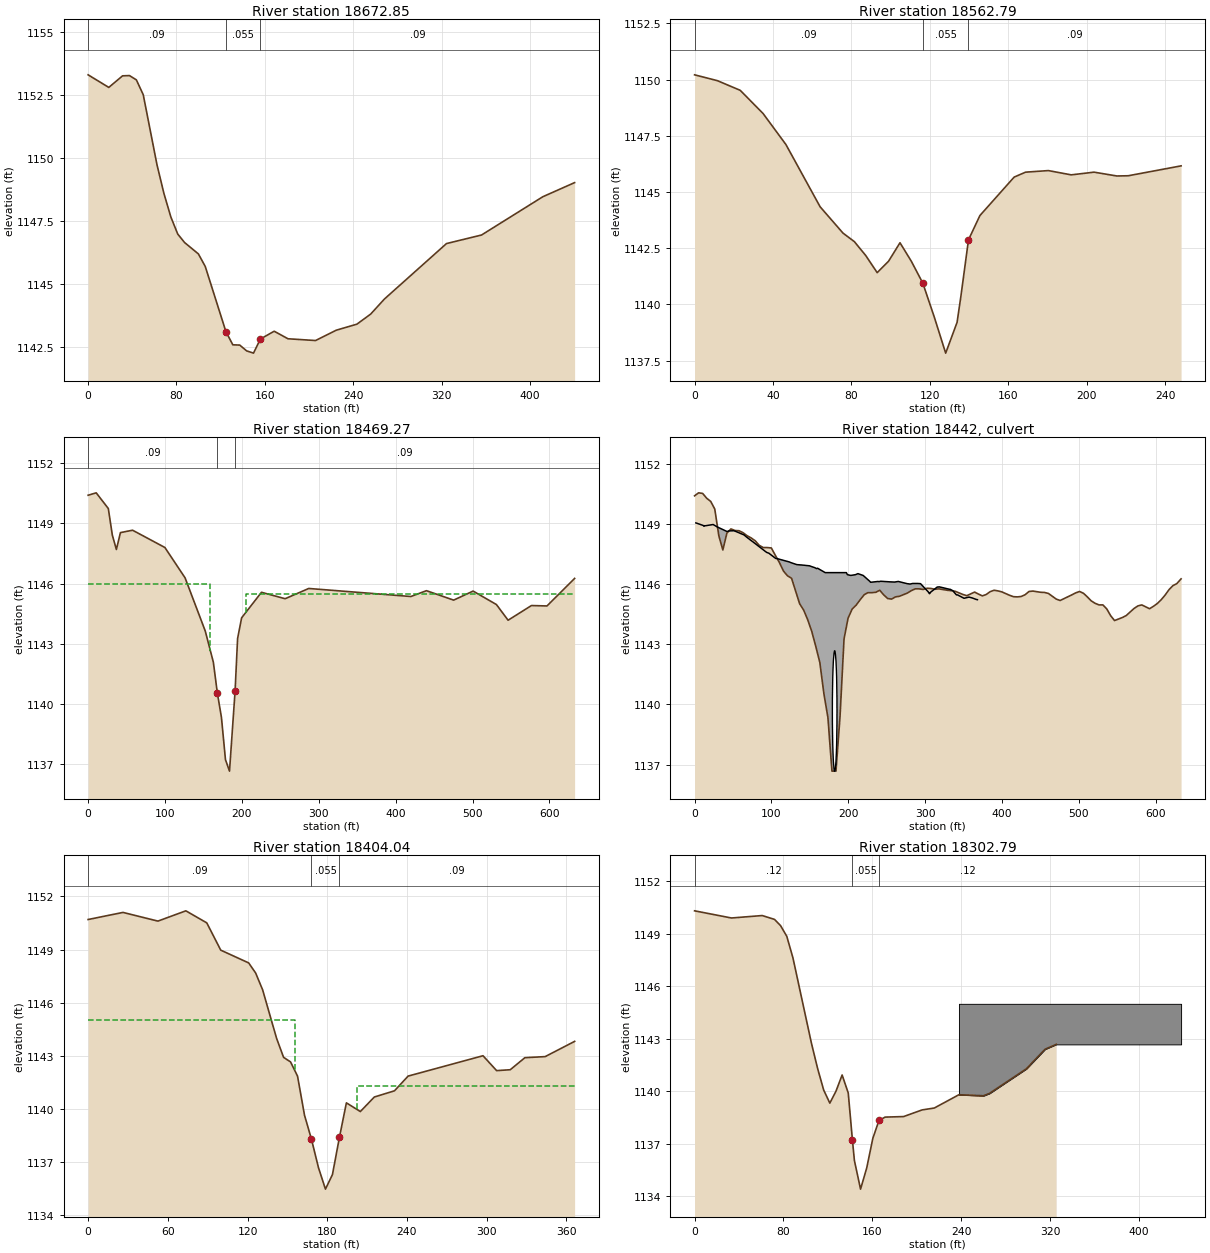
Type RM Length L Ch R = 1 ,18672.85,106.96,110.06,113.1
XS GIS Cut Line= 3
  1355729.562129   794444.785405  1355444.125729   794657.927843
  1355432.907716   794741.439818
#Sta/Elev= 30
       0 1153.29   18.72 1152.79    31.2 1153.25   37.44 1153.26   43.68 1153.09
   49.92  1152.5    62.4 1149.71   68.64 1148.58   74.88 1147.65   81.12 1146.97
   87.36 1146.63   99.83 1146.18  106.07 1145.68  124.79 1143.09  131.03 1142.57
  137.27 1142.56  143.51 1142.33  149.75 1142.24  155.99  1142.8  168.49 1143.11
  180.96 1142.81  205.93 1142.74  224.65 1143.15  243.37 1143.39  255.84 1143.79
  268.32 1144.39  324.48 1146.59  356.23 1146.93  411.72 1148.45  440.49 1149.01
#Mann= 3 , 0 , 0
       0     .09       0  124.79    .055       0  155.99     .09       0
Bank Sta=124.79,155.99
Exp/Cntr=0.3,0.1

Type RM Length L Ch R = 1 ,18562.79,86.52,93.52,100.21
XS GIS Cut Line= 2
   1355653.52886   794382.463068  1355440.386376    794509.60066
#Sta/Elev= 28
       0 1150.21   11.65 1149.95   23.29 1149.52   34.93 1148.49   46.59 1147.11
   64.04 1144.34    75.7 1143.17   81.51 1142.79   87.33 1142.17   93.15 1141.41
   98.97 1141.92  104.79 1142.74  110.62 1141.91  116.44 1140.94  122.26 1139.44
  128.09 1137.83  133.91  1139.2  135.84 1140.35  139.73 1142.87  145.55 1143.95
  163.02 1145.66  168.84 1145.88  180.48 1145.95  192.12 1145.76  203.77 1145.88
  215.41 1145.71  221.23 1145.72  248.18 1146.16
#Mann= 3 , 0 , 0
       0     .09       0  116.44    .055       0  139.73     .09       0
Bank Sta=116.44,139.73
Exp/Cntr=0.5,0.3

Type RM Length L Ch R = 1 ,18469.27,64.38,65.23,65.97
XS GIS Cut Line= 4
  1355663.292706   794317.488184  1355448.733401   794386.840703
   1355347.95559   794409.596965  1355047.405269   794455.189489
#Sta/Elev= 30
       0  1150.4   10.51 1150.52   26.26 1149.74   31.53 1148.41   36.77  1147.7
   42.04 1148.54    57.8 1148.66   99.84  1147.8  126.11 1146.29  152.39 1143.64
   162.9 1142.09  168.15 1140.54   173.4 1139.35  178.66 1137.24   183.9 1136.67
  191.14 1140.64  194.42 1143.27  199.68  1144.3  225.49 1145.57  256.23 1145.25
     287 1145.76  419.83 1145.36  440.06 1145.65  475.46 1145.18  500.75 1145.63
  531.09 1144.96  546.26 1144.18  576.61 1144.91  596.84 1144.89  632.79 1146.26
#Mann= 3 , 0 , 0
       0     .09       0  168.15    .055       0  191.14     .09       0
#XS Ineff= 2 , 0
       0     159    1146     205       0  1145.5
Permanent Ineff=
       F       F
Bank Sta=168.15,191.14
Exp/Cntr=0.5,0.3

Type RM Length L Ch R = 2 ,18442   ,,,
BEGIN DESCRIPTION:
37003-0097 Culvert X-ing (unnamed road)
END DESCRIPTION:
Bridge Culvert--1,0,-1,-1, 0
Deck Dist Width WeirC Skew NumUp NumDn MinLoCord MaxHiCord MaxSubmerge Is_Ogee
20,20,2.6,0, 76, 76, , , 0.95, 0, 0,0,,
    1.68   11.34   12.23   12.77   14.54   24.12   29.42   42.24   44.78   51.24
   51.82    53.3   64.31   68.41   78.11   79.47   80.12   82.51   93.65   96.57
  105.39  107.32  123.51  124.01  124.49  132.88  139.42  149.57   151.5  156.16
  158.83  159.95  169.92  179.55  180.39  182.81   183.9  184.57   187.5  197.44
  198.71  203.21  209.45  212.37  219.27  227.17  229.01  229.34  238.57  239.87
  242.09  254.16   260.2  264.87  276.49  280.27  283.65  289.82   293.9  304.15
  305.22  305.63   307.2  315.54  318.39  330.48  331.35  332.34  335.81  340.56
  341.97  350.47  356.89  360.93  366.45   367.9
 1149.05 1148.92 1148.88 1148.91 1148.91 1148.97 1148.85 1148.62 1148.65 1148.66
 1148.65 1148.63 1148.45 1148.32 1148.04    1148 1147.98 1147.91 1147.58 1147.54
 1147.28 1147.27  1147.1 1147.09 1147.08 1146.97 1146.95 1146.91 1146.88 1146.82
 1146.77 1146.79 1146.57 1146.57 1146.57 1146.57 1146.57 1146.57 1146.57 1146.57
 1146.47 1146.43 1146.47 1146.52 1146.43 1146.16 1146.09 1146.09 1146.13 1146.12
 1146.14 1146.11  1146.1 1146.13 1146.02    1146 1146.03 1146.03 1146.02  1145.6
 1145.53 1145.52  1145.6 1145.85 1145.86 1145.75 1145.74 1145.74 1145.67 1145.46
 1145.46 1145.29 1145.35 1145.31 1145.23 1145.22
                                                                                
                                                                                
                                                                                
                                                                                
                                                                                
                                                                                
                                                                                
                                                
    3.36   13.02   13.91   14.45   16.22    25.8    31.1   43.92   46.46   52.92
    53.5   54.98   65.99   70.09   79.79   81.15    81.8   84.19   95.33   98.25
  107.07     109  125.19  125.69  126.17  134.56   141.1  151.25  153.18  157.84
  160.51  161.63   171.6  181.23  182.07  184.49  185.58  186.25  189.18  199.12
  200.39  204.89  211.13  214.05  220.95  228.85  230.69  231.02  240.25  241.55
  243.77  255.84  261.88  266.55  278.17  281.95  285.33   291.5  295.58  305.83
   306.9  307.31  308.88  317.22  320.07  332.16  333.03  334.02  337.49  342.24
  343.65  352.15  358.57  362.61  368.13  369.58
 1149.05 1148.92 1148.88 1148.91 1148.91 1148.97 1148.85 1148.62 1148.65 1148.66
 1148.65 1148.63 1148.45 1148.32 1148.04    1148 1147.98 1147.91 1147.58 1147.54
 1147.28 1147.27  1147.1 1147.09 1147.08 1146.97 1146.95 1146.91 1146.88 1146.82
 1146.77 1146.79 1146.57 1146.57 1146.57 1146.57 1146.57 1146.57 1146.57 1146.57
 1146.47 1146.43 1146.47 1146.52 1146.43 1146.16 1146.09 1146.09 1146.13 1146.12
 1146.14 1146.11  1146.1 1146.13 1146.02    1146 1146.03 1146.03 1146.02  1145.6
 1145.53 1145.52  1145.6 1145.85 1145.86 1145.75 1145.74 1145.74 1145.67 1145.46
 1145.46 1145.29 1145.35 1145.31 1145.23 1145.22
                                                                                
                                                                                
                                                                                
                                                                                
                                                                                
                                                                                
                                                                                
                                                
BR Coef=-1 , 0 , 0 ,, 0 ,,,0.8,-1,,0,
WSPro=,,,, 1 ,,,, 0 ,,,, 0 ,,,,-1 ,-1 ,-1 , 0 , 0 , 0 , 0 , 0
Culvert=1,6,,47,0.013,0.5,1,1,1,1136.67,182.22,1135.48,179.4,Culvert #1  , 0 ,6.5
Culvert Bottom n=0.013
BR U #Sta/Elev= 111
       0  1150.4    5.24 1150.55   10.51 1150.52   15.76 1150.28   21.02 1150.12
   26.26 1149.74   31.53 1148.41   36.77  1147.7   42.04 1148.54   47.29 1148.75
   52.55 1148.67    57.8 1148.66   63.06 1148.56   68.31 1148.41   73.57  1148.3
   78.82 1148.16   84.08 1147.93   89.33 1147.82   94.58 1147.82   99.84  1147.8
  105.08 1147.43  110.35 1147.07  115.59 1146.65  120.86 1146.41  126.11 1146.29
  136.62 1145.02  141.88  1144.7  147.13 1144.22  152.39 1143.64  157.64 1142.89
   162.9 1142.09  168.15 1140.54   173.4 1139.35  178.66 1136.67   183.9 1136.67
  189.17 1139.38  194.42 1143.27  199.68  1144.3  204.92 1144.75  210.19 1144.95
  215.44 1145.22   220.7 1145.47  225.49 1145.57  230.62 1145.57  235.74 1145.59
  240.87 1145.69  245.98 1145.46  251.12 1145.28  256.23 1145.25  261.37 1145.36
   266.5 1145.39  276.75 1145.55  281.86 1145.67     287 1145.76  292.13 1145.76
  297.25 1145.73  302.38 1145.79  307.49 1145.78  312.63 1145.74  317.75 1145.76
   328.8 1145.69  333.86 1145.67  338.92 1145.64  349.03 1145.48  354.09 1145.42
   364.2  1145.6  369.25  1145.5  374.32 1145.41  379.38 1145.48  384.43 1145.62
  389.49 1145.69  394.55 1145.66  399.61 1145.61  409.72 1145.44  414.78 1145.37
  419.83 1145.36  424.89 1145.38  429.95 1145.47  435.01 1145.63  440.06 1145.65
  450.18 1145.59  455.23 1145.58  460.29 1145.53  470.41 1145.25  475.46 1145.18
  490.64 1145.46  495.69 1145.56  500.75 1145.63  505.81 1145.54  510.86 1145.36
  515.92 1145.16  520.98 1145.04  526.04 1144.96  531.09 1144.96  536.15 1144.76
  541.21 1144.42  546.26 1144.18  556.38 1144.33  561.44 1144.43  571.55 1144.78
  576.61 1144.91  581.66 1144.96  591.78 1144.77  596.84 1144.89  601.89 1145.03
  606.95 1145.22  612.01 1145.45  617.07 1145.72  622.13 1145.92  627.18 1146.02
  632.79 1146.26
BR U #Mann= 3
       0      .1   173.4    .055  189.17      .1
BR U Banks=,189.17
BR D #Sta/Elev= 69
       0  1150.7    5.26 1150.88   15.76 1151.07   21.02 1151.04   26.27  1151.1
   31.53 1151.08   36.79 1150.84   42.04 1150.68   47.29 1150.72   52.55 1150.61
    57.8 1150.67   63.06 1151.06   68.31 1151.11   73.57 1151.19   78.82 1151.06
   84.08 1150.87   89.33 1150.51   94.58 1149.66   99.84 1148.97   105.1 1148.83
  110.35 1148.72  115.61 1148.57  120.86 1148.25  126.11 1147.68  131.37 1146.73
  141.88 1143.99  147.13 1142.92  152.39 1142.66  157.64 1141.86   162.9 1139.65
  168.15 1138.29  173.41 1136.69     175 1135.48  178.66 1135.48  183.92 1135.48
  189.17  1138.4  194.42 1140.35  199.68 1140.29  204.93 1139.86  210.19 1140.33
  215.45 1140.68   220.7 1140.64  225.49  1140.8  230.62 1141.03  235.74 1141.43
  240.87 1141.86  245.99    1142  256.24 1142.12  261.37 1142.31   266.5 1142.53
  271.63 1142.51  276.75 1142.46  281.87 1142.55     287 1142.84  292.13 1142.98
  297.25 1143.01  302.38  1142.6   307.5 1142.17  312.63 1142.23  317.76 1142.22
  322.88 1142.48   328.8  1142.9  333.88 1143.03  338.96 1142.94  344.04 1142.96
  349.11 1143.18  354.18 1143.37  359.27 1143.55  366.22 1143.82
BR D #Mann= 3
       0      .1  173.41    .055  189.17      .1
BC Design=,, 0 ,, 0 ,,,,,,

Type RM Length L Ch R = 1 ,18404.04,105.97,101.25,96.48
XS GIS Cut Line= 4
  1355626.739087   794263.844656  1355412.179781   794333.197175
  1355311.401971   794355.953437   1355274.55843   794362.455232
#Sta/Elev= 30
       0  1150.7   26.27  1151.1   52.55 1150.61   73.57 1151.19   89.33 1150.51
   99.84 1148.97  120.86 1148.25  126.11 1147.68  131.37 1146.73  141.88 1143.99
  147.13 1142.92  152.39 1142.66  157.64 1141.86   162.9 1139.65  168.15 1138.29
  173.41 1136.69  178.66 1135.48  183.92  1136.3  189.17  1138.4  194.42 1140.35
  204.93 1139.86  215.45 1140.68  230.62 1141.03  240.87 1141.86  297.25 1143.01
   307.5 1142.17  317.76 1142.22   328.8  1142.9  344.04 1142.96  366.22 1143.82
#Mann= 3 , 0 , 0
       0     .09       0  168.15    .055       0  189.17     .09       0
#XS Ineff= 2 , 0
       0     156    1145  202.05       0 1141.29
Permanent Ineff=
       F       F
Bank Sta=168.15,189.17
Exp/Cntr=0.5,0.3

Type RM Length L Ch R = 1 ,18302.79,420.94,387.51,350.95
XS GIS Cut Line= 2
  1355540.102152   794168.074148  1355245.940657   794307.676235
#Sta/Elev= 30
       0 1150.32   33.21 1149.91   60.88 1150.05   71.95 1149.83   77.47 1149.47
   83.02 1148.86   88.55 1147.63  105.16 1142.76  110.69 1141.32  116.22 1140.07
  121.76 1139.32  127.29    1140  132.83 1140.93  138.35  1139.9  142.07 1137.23
   143.9 1136.03  149.43  1134.4  154.97 1135.61   160.5 1137.31  166.03 1138.33
  171.57 1138.52  188.16 1138.55  204.78 1138.93  215.85 1139.04  237.98  1139.8
  260.11 1139.74  265.66 1139.88  298.86 1141.29  315.47  1142.4  325.61 1142.68
#Mann= 3 , 0 , 0
       0     .12       0  142.07    .055       0  166.03     .12       0
#Block Obstruct= 1 ,-1
     238     438    1145
Bank Sta=142.07,166.03
Exp/Cntr=0.3,0.1

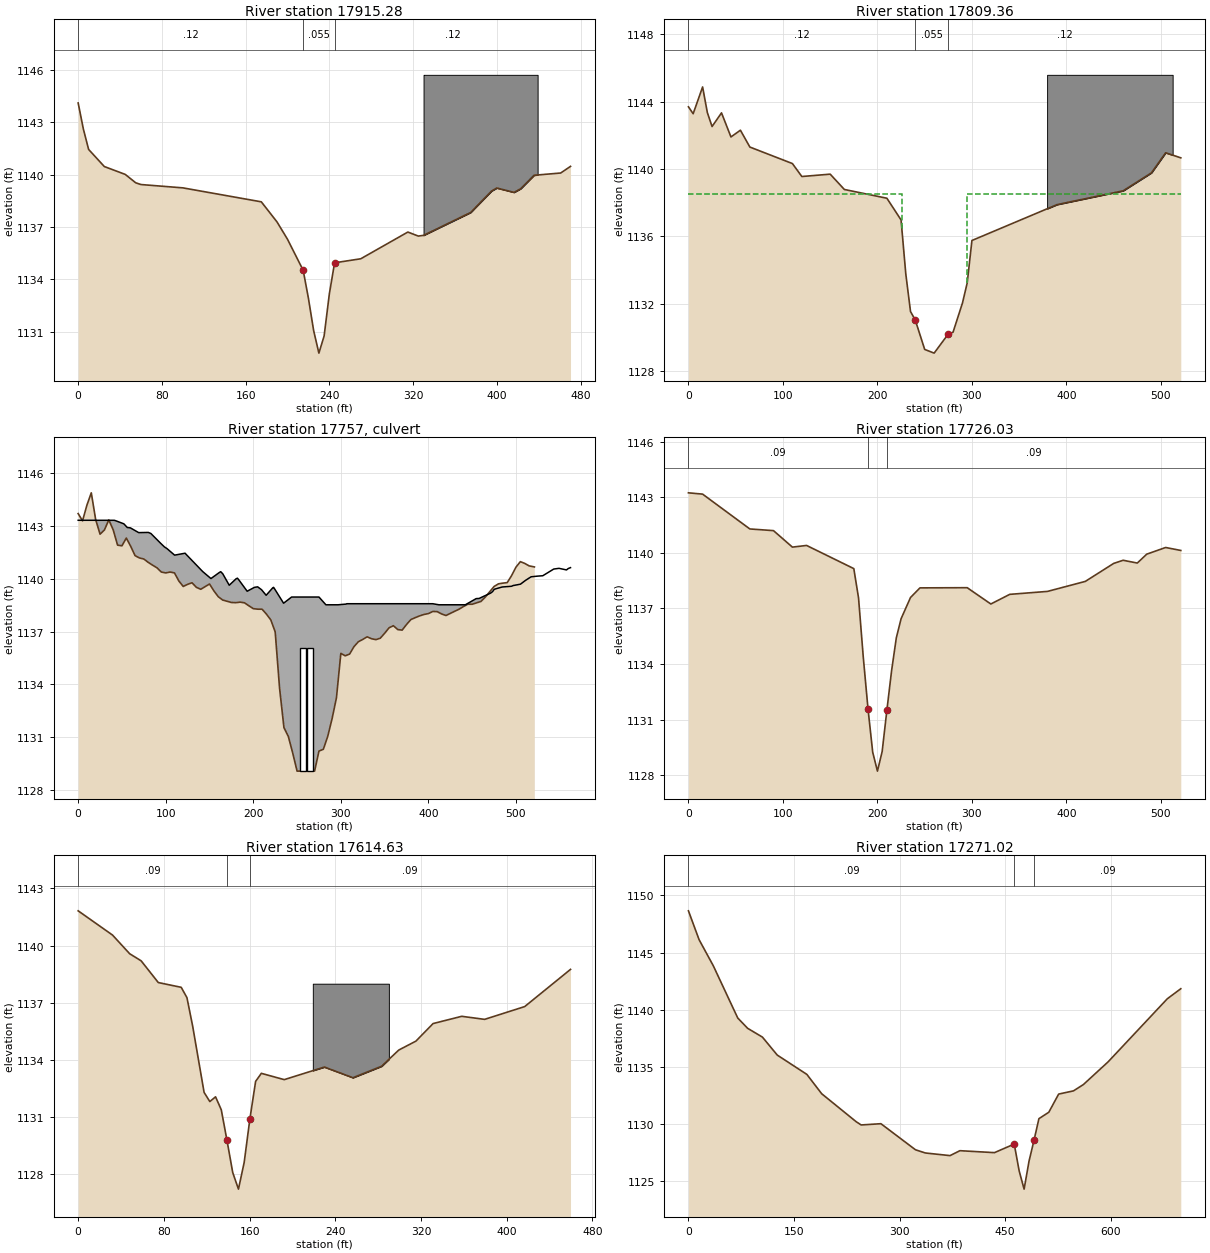
Type RM Length L Ch R = 1 ,17915.28,124.68,105.92,80.87
XS GIS Cut Line= 3
  1355218.518795   793704.395832  1355214.779489   794114.476906
  1355177.386049   794161.841923
#Sta/Elev= 30
       0  1144.1       5  1142.6      10 1141.44      25 1140.46   44.99 1140.01
   54.99 1139.53   59.99 1139.43   99.99 1139.24  175.01 1138.44  190.01 1137.29
  200.01  1136.3  215.01 1134.52  220.01 1132.92  225.01 1131.07  230.01 1129.78
  235.01 1130.76  240.01 1133.17  245.01 1134.95  270.01 1135.18  315.01 1136.71
  325.01 1136.48  330.01 1136.52  375.02 1137.83  395.02 1139.06  400.02 1139.23
  416.47 1138.98  422.84 1139.19  435.58 1139.96  461.06 1140.09  470.44 1140.47
#Mann= 3 , 0 , 0
       0     .12       0  215.01    .055       0  245.01     .12       0
#Block Obstruct= 1 ,-1
     330     439 1145.71
Bank Sta=215.01,245.01
Exp/Cntr=0.5,0.3

Type RM Length L Ch R = 1 ,17809.36,63.95,83.32,104.8
XS GIS Cut Line= 2
  1355134.459017   793628.828784  1355139.444805   794149.843695
#Sta/Elev= 30
       0  1143.7       5 1143.29      15 1144.88      20 1143.36      25 1142.53
      35 1143.34      45 1141.91      55 1142.31      65 1141.31  110.01 1140.33
  120.01 1139.56  150.01  1139.7  165.01 1138.79  210.01 1138.27  225.01 1136.98
  230.01 1133.78  235.01 1131.54  240.01 1131.04  250.01 1129.29  260.01 1129.07
  275.01 1130.21  280.01 1130.31     290 1132.05     295 1133.24     300 1135.76
  390.02 1137.89  460.02 1138.71  490.02 1139.78  505.01 1140.97  521.03 1140.67
#Mann= 3 , 0 , 0
       0     .12       0  240.01    .055       0  275.01     .12       0
#XS Ineff= 2 , 0
       0     226 1138.52     295       0 1138.52
Permanent Ineff=
       F       F
#Block Obstruct= 1 ,-1
  379.56   512.4  1145.6
Bank Sta=240.01,275.01
Exp/Cntr=0.5,0.3

Type RM Length L Ch R = 2 ,17757   ,,,
BEGIN DESCRIPTION:
37003-0043 Culvert X-ing (SR # 16)
END DESCRIPTION:
Bridge Culvert--1,0,-1,-1, 0
Deck Dist Width WeirC Skew NumUp NumDn MinLoCord MaxHiCord MaxSubmerge Is_Ogee
27,25,2.6,0, 94, 94, , , 0.95, 0, 0,0,,
       0   41.24   42.61   52.15   56.13   59.63    69.1   80.17   83.05   94.27
   98.46   101.5  110.16  122.04  122.15   122.3  123.21   140.8   142.4  151.64
  161.09   162.8  165.16  172.53  180.43   181.9  183.27  193.01  201.29  204.95
  209.35  214.69  222.15  223.09  223.76   234.6  243.74  246.58  253.05   254.4
  255.16  255.62  260.01     263  264.82  269.41  275.02   282.9  286.44  290.32
  296.87  305.96  306.73  322.02  326.78   332.2  338.89   346.4  352.24  357.49
  364.31   372.1  375.23  379.55  383.69  386.66  393.84   399.5  404.94  411.94
  416.42  424.28  427.87  429.87  442.17  454.52  457.88  470.91   473.3  475.15
   484.2  494.54  495.38  496.49  505.11  511.01  517.27  525.16  530.62  543.12
  549.16  557.67   559.7  562.28
 1143.32 1143.32  1143.3 1143.12 1142.91 1142.89 1142.62 1142.63 1142.57 1142.01
 1141.81 1141.71 1141.34 1141.45 1141.45 1141.44 1141.39 1140.48  1140.4 1140.01
 1140.35  1140.4 1140.28 1139.63    1140 1140.03 1139.95 1139.29 1139.51 1139.54
 1139.38 1139.06 1139.48 1139.51 1139.47 1138.61 1138.96 1138.96 1138.96 1138.96
 1138.96 1138.96 1138.96 1138.96 1138.96 1138.96 1138.96 1138.52 1138.52 1138.52
 1138.52 1138.56 1138.58 1138.58 1138.58 1138.58 1138.58 1138.58 1138.58 1138.58
 1138.58 1138.58 1138.58 1138.58 1138.58 1138.58 1138.58 1138.58 1138.58 1138.52
 1138.52 1138.52 1138.52 1138.52 1138.52 1138.87 1138.88 1139.18 1139.27  1139.4
 1139.53 1139.57 1139.58 1139.61 1139.69 1139.91 1140.11 1140.15 1140.17 1140.55
 1140.59  1140.5 1140.58 1140.63
                                                                                
                                                                                
                                                                                
                                                                                
                                                                                
                                                                                
                                                                                
                                                                                
                                                                                
                                
  -18.78  -17.41   -7.87   -3.89    -.39    9.08   20.15   23.03   34.25   38.44
   41.48   50.14   62.02   62.13   62.28   63.19   80.78   82.38   91.62  101.07
  102.78  105.14  112.51  120.41  121.88  123.25  132.99  141.27  144.93  149.33
  154.67  162.13  163.07  163.74  174.58  183.72  186.56  193.03  194.38  195.14
   195.6  199.99  202.98   204.8  209.39     215  222.88  226.42   230.3  236.85
  245.94  246.71     262  266.76  272.18  278.87  286.38  292.22  297.47  304.29
  312.08  315.21  319.53  323.67  326.64  333.82  339.48  344.92  351.92   356.4
  364.26  367.85  369.85  382.15   394.5  397.86  410.89  413.28  415.13  424.18
  434.52  435.36  436.47  445.09  450.99  457.25  465.14   470.6   483.1  489.14
  497.65  499.68  502.26     600
 1143.32  1143.3 1143.12 1142.91 1142.89 1142.62 1142.63 1142.57 1142.01 1141.81
 1141.71 1141.34 1141.45 1141.45 1141.44 1141.39 1140.48  1140.4 1140.01 1140.35
  1140.4 1140.28 1139.63    1140 1140.03 1139.95 1139.29 1139.51 1139.54 1139.38
 1139.06 1139.48 1139.51 1139.47 1138.61 1138.96 1138.96 1138.96 1138.96 1138.96
 1138.96 1138.96 1138.96 1138.96 1138.96 1138.96 1138.52 1138.52 1138.52 1138.52
 1138.56 1138.58 1138.58 1138.58 1138.58 1138.58 1138.58 1138.58 1138.58 1138.58
 1138.58 1138.58 1138.58 1138.58 1138.58 1138.58 1138.58 1138.58 1138.58 1138.52
 1138.52 1138.52 1138.52 1138.52 1138.87 1138.88 1139.18 1139.27  1139.4 1139.53
 1139.57 1139.58 1139.61 1139.69 1139.91 1140.11 1140.15 1140.17 1140.55 1140.59
  1140.5 1140.58 1140.63 1140.63
                                                                                
                                                                                
                                                                                
                                                                                
                                                                                
                                                                                
                                                                                
                                                                                
                                                                                
                                
BR Coef=-1 , 1 , 0 ,, 0 ,,,0.8,0,1.2,0,
WSPro=,,,, 1 ,,,, 0 ,,,, 0 ,,,,-1 ,-1 ,-1 , 0 , 0 , 0 , 0 , 0
Multiple Barrel Culv=2,7,7,68,0.013,0.4,1,8,1,1129.07,1128.22, 2,Culvert #1  , 0 ,5.5
  256.52  195.99  264.52  203.99
Culvert Bottom n=0.013
BR U #Sta/Elev= 99
       0  1143.7       5 1143.29      10 1144.18      15 1144.88      20 1143.36
      25 1142.53      30 1142.77      35 1143.34      40 1142.78      45 1141.91
      50 1141.87      55 1142.31      60 1141.84      65 1141.31      70 1141.18
      75 1141.12   79.99 1140.93   84.99 1140.77   89.99 1140.62   94.99 1140.38
   99.99 1140.33  104.99 1140.38  110.01 1140.33  115.01 1139.87  120.01 1139.56
  125.01 1139.68  130.01 1139.77  135.01 1139.51  140.01  1139.4  150.01  1139.7
  155.01 1139.31  160.01 1138.98  165.01 1138.79  175.01 1138.65  180.01 1138.64
  185.01 1138.67  190.01 1138.63  195.01 1138.46  200.01  1138.3  205.01 1138.27
  210.01 1138.27  215.01 1137.99  220.01 1137.66  225.01 1136.98  230.01 1133.78
  235.01 1131.54  240.01 1131.04  245.01  1130.1  250.01 1129.07  255.01 1129.07
  260.01 1129.07  265.01 1129.07  270.01 1129.07  275.01 1130.21  280.01 1130.31
  285.01 1131.04     290 1132.05     295 1133.24     300 1135.76     305 1135.62
     310 1135.72     315 1136.14     320 1136.42     325 1136.55  330.02  1136.7
  335.02 1136.59  340.02 1136.54  345.02 1136.62  350.02  1136.9  355.02 1137.21
  360.02 1137.33  365.02 1137.11  370.02 1137.08  375.02  1137.4  380.02 1137.68
  385.02 1137.79  390.02 1137.89  395.02 1137.97  400.02 1138.02  405.02 1138.14
  410.02 1138.13  415.02    1138  420.02 1137.91  435.02 1138.27  440.02 1138.42
  445.02 1138.55  450.02 1138.55  460.02 1138.71  465.02 1138.96  475.02 1139.56
  480.02 1139.71  485.02 1139.75  490.02 1139.78  495.01 1140.18  500.01 1140.66
  505.01 1140.97  510.01 1140.87  515.01 1140.73  521.03 1140.67
BR U #Mann= 3
       0      .1  235.01    .055     290      .1
BR U Banks=245.01,275.01
BR D #Sta/Elev= 100
       0 1143.24       5 1143.11      10 1143.21      15 1143.17      20 1142.96
      25 1142.73      30 1142.55      35 1142.41      40 1142.23      60 1141.45
      65 1141.29      70 1141.21      75 1141.27      80 1141.31      85 1141.27
      90  1141.2      95 1141.06     100 1140.87     105 1140.58  110.02 1140.31
  115.02  1140.3  120.02 1140.41  125.02  1140.4  130.02 1140.31  135.02 1140.14
  140.02 1140.12  145.02 1139.98  150.02  1139.8  155.02 1139.65  160.01 1139.65
  170.01 1139.41  175.01 1139.15  180.01 1137.57  185.01 1134.38  190.01 1131.59
     192 1128.22  195.01 1128.22  200.01 1128.22  205.01 1128.22   207.5 1128.22
  210.01 1131.51  215.01 1133.65  220.01 1135.42  225.01 1136.44  230.01 1137.11
  235.01 1137.59  240.01 1137.94  245.01 1138.11  250.01 1138.24  255.01 1138.25
  260.01 1138.25  265.01 1138.22  270.01  1138.2  280.01 1138.18  285.01 1138.16
  290.01 1138.15  295.01 1138.12  300.01 1138.03  305.01 1137.78  310.01 1137.52
  315.01 1137.34  320.01 1137.24  325.01 1137.29  330.03 1137.47  335.03 1137.63
  340.03 1137.76  345.03 1137.82  350.03 1137.79  355.03 1137.79  360.03 1137.82
  365.03  1137.9  370.02 1137.92  375.02  1137.9  380.02 1137.92  385.02 1138.01
  390.02 1138.07  395.02  1138.1  400.02 1138.18  405.02 1138.37  410.02 1138.46
  415.02 1138.41  420.02 1138.46  425.02 1138.68  430.02 1138.93  435.02  1139.1
  450.02 1139.43  455.02 1139.53  460.02  1139.6  465.02 1139.57  470.02 1139.48
  475.02 1139.45  480.02 1139.66  485.02 1139.93  490.02 1140.06  495.02 1140.04
  500.02 1140.14  505.02 1140.29  510.02 1140.31  515.02 1140.12  521.04 1140.13
BR D #Mann= 3
       0      .1  190.01    .055  210.01      .1
BR D Banks=190.01,210.01
BC Design=,, 0 ,, 0 ,,,,,,

Type RM Length L Ch R = 1 ,17726.03,102.84,111.4,124.94
XS GIS Cut Line= 2
  1355081.577822    793630.69264  1355086.563611    794151.70755
#Sta/Elev= 30
       0 1143.24      15 1143.17      65 1141.29      90  1141.2  110.02 1140.31
  125.02  1140.4  175.01 1139.15  180.01 1137.57  185.01 1134.38  190.01 1131.59
  195.01 1129.24  200.01 1128.22  205.01 1129.28  210.01 1131.51  215.01 1133.65
  220.01 1135.42  225.01 1136.44  235.01 1137.59  245.01 1138.11  295.01 1138.12
  320.01 1137.24  340.03 1137.76  380.02 1137.92  420.02 1138.46  450.02 1139.43
  460.02  1139.6  475.02 1139.45  485.02 1139.93  505.02 1140.29  521.04 1140.13
#Mann= 3 , 0 , 0
       0     .09       0  190.01    .055       0  210.01     .09       0
#XS Ineff= 2 , 0
       0     165    1137   234.5       0    1137
Permanent Ineff=
       F       F
Bank Sta=190.01,210.01
Exp/Cntr=0.5,0.3

Type RM Length L Ch R = 1 ,17614.63,325.14,343.61,355.6
XS GIS Cut Line= 2
  1355034.044655   793647.059283  1354872.006494   794077.083513
#Sta/Elev= 30
       0 1141.82   32.06 1140.55   48.09 1139.57   58.77  1139.2   74.79 1138.06
   96.18 1137.81  101.52 1137.27  106.86 1135.78  117.55  1132.3  122.89 1131.82
  128.23 1132.07  133.58 1131.39  138.92 1129.78  144.27  1128.1  149.61 1127.23
  154.95 1128.63   160.3 1130.92  165.64 1132.88  170.98  1133.3  192.34 1132.97
  229.76 1133.63  256.47 1133.07  283.19 1133.67  299.22 1134.52  315.25 1134.99
  331.28 1135.91  357.99 1136.29  379.36 1136.13  416.77  1136.8  459.53 1138.75
#Mann= 3 , 0 , 0
       0     .09       0  138.92    .055       0   160.3     .09       0
#Block Obstruct= 1 ,-1
     219     290    1138
Bank Sta=138.92,160.3
Exp/Cntr=0.3,0.1

Type RM Length L Ch R = 1 ,17271.02,312.87,328.11,337.53
XS GIS Cut Line= 3
   1355042.76975   793321.736573  1354994.158344   793327.968797
  1354537.958688   793791.647113
#Sta/Elev= 30
       0 1148.65   15.12 1146.13   35.29 1143.85   70.05 1139.28   84.08 1138.38
  105.12 1137.61  126.17 1136.04  168.25 1134.35   189.3 1132.66  238.39 1130.21
  245.41 1129.93  273.46 1130.04  322.57 1127.76  336.59 1127.48  371.67 1127.25
  385.69 1127.68  434.79 1127.51  462.85 1128.26  469.87 1125.91  476.88 1124.32
  483.89 1126.77  490.91 1128.58  497.92 1130.48  511.95 1131.04  525.98 1132.63
  547.03 1132.91  561.05 1133.46  596.12 1135.44  680.29 1140.96  699.48 1141.84
#Mann= 3 , 0 , 0
       0     .09       0  462.85    .055       0  490.91     .09       0
Bank Sta=462.85,490.91
Exp/Cntr=0.3,0.1