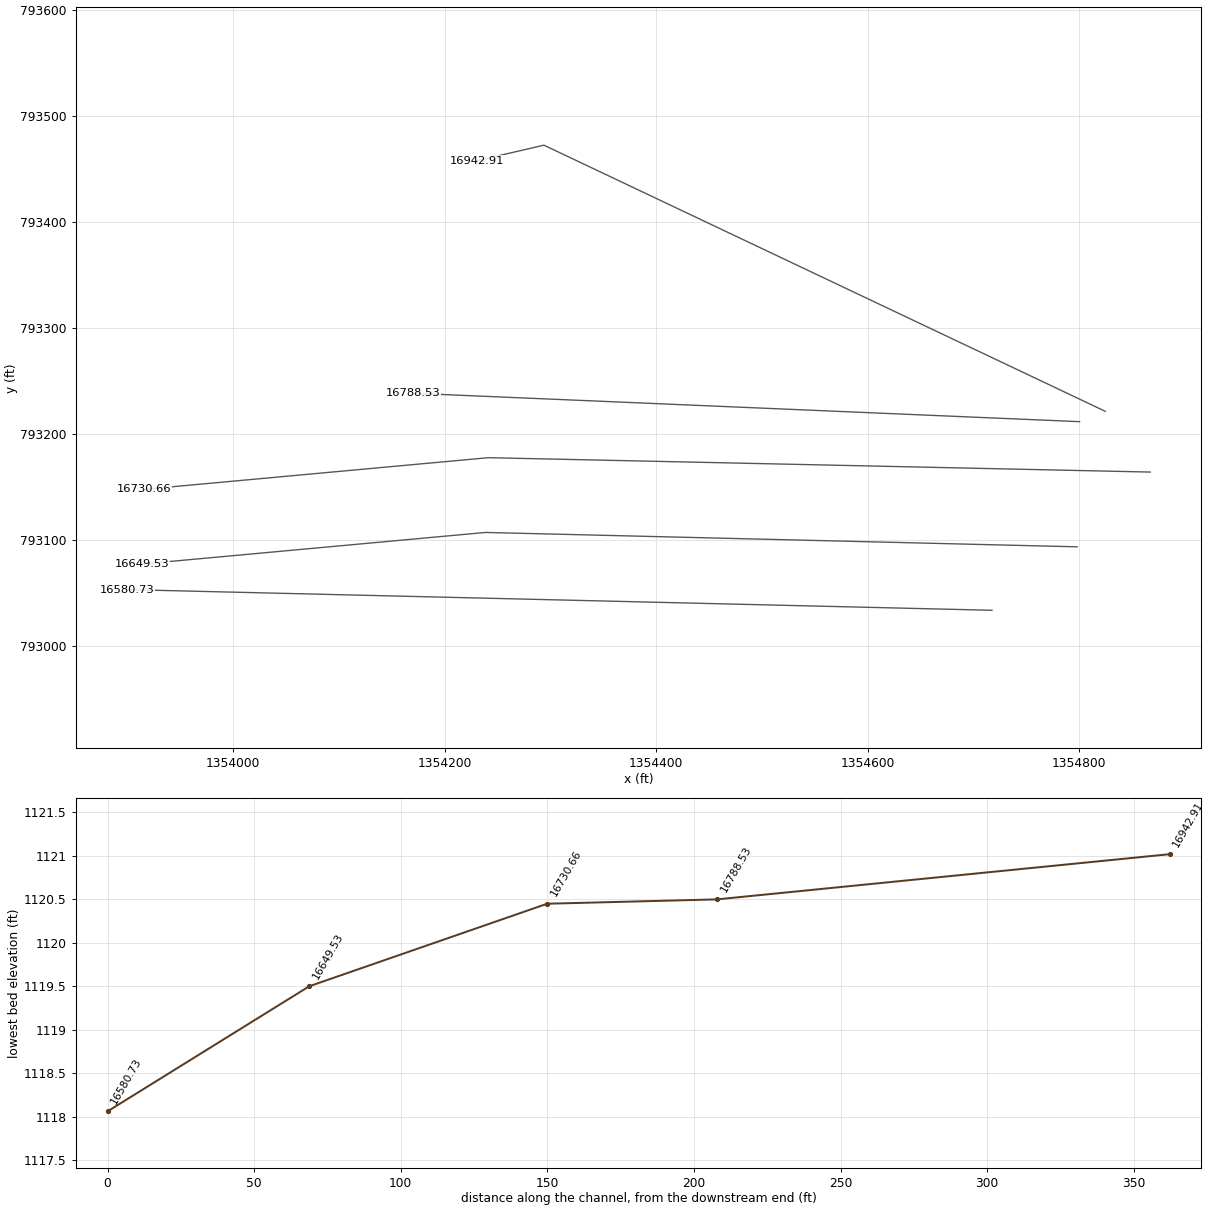
HEC-RAS study StirewaitCr.prj: StirewaitCr

--- StirewaitCr.g01 (geometry) --- (continued)

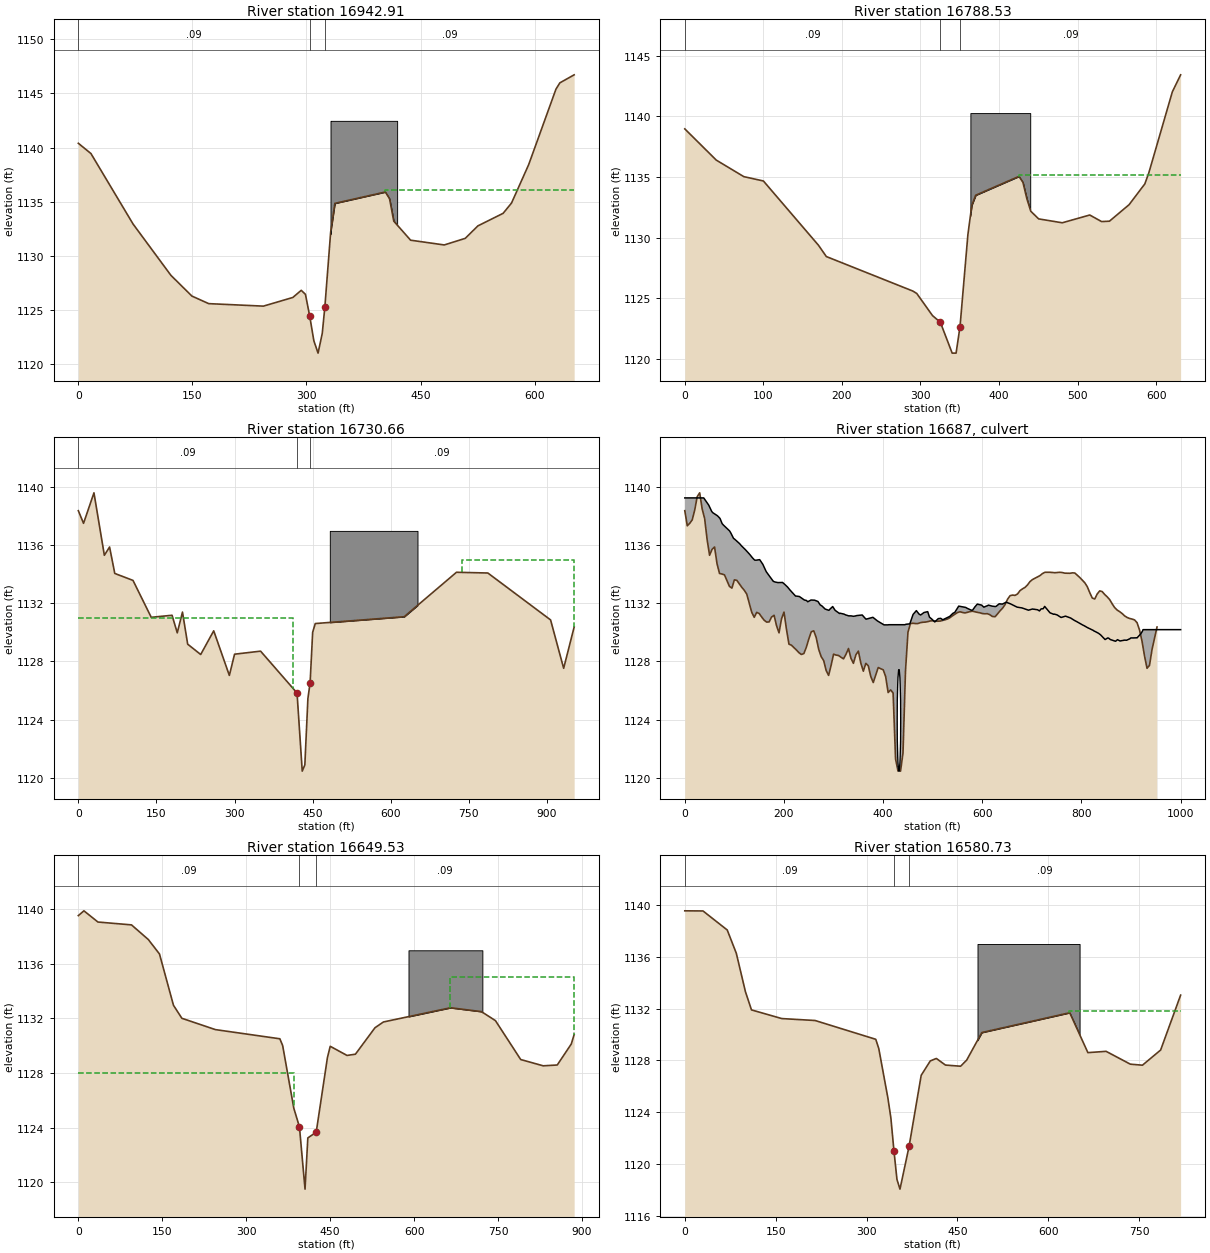
Type RM Length L Ch R = 1 ,16942.91,139.5,154.38,166.47
XS GIS Cut Line= 3
  1354824.602594   793221.504704   1354293.88875   793472.254786
  1354230.592622   793457.648016
#Sta/Elev= 30
       0  1140.4   16.59 1139.45   71.89 1132.95  121.66 1128.21  149.31 1126.29
  171.43 1125.59  243.32 1125.36  282.03 1126.16  293.09 1126.82  298.62 1126.45
  304.15 1124.47  309.68 1122.16  315.21 1121.02  320.74 1122.85  324.17  1125.3
   331.8 1132.21  337.33 1134.85  403.69  1135.9  409.22 1135.27  414.75 1133.21
  436.87 1131.45  481.11 1131.01  508.76 1131.62  525.35 1132.77  558.53 1133.93
  569.59 1134.88   592.1 1138.42  628.02  1145.4  633.15 1145.98  651.93 1146.72
#Mann= 3 , 0 , 0
       0     .09       0  304.15    .055       0  324.17     .09       0
#XS Ineff= 2 , 0
                          402.96         1136.09
Permanent Ineff=
       F       F
#Block Obstruct= 1 ,-1
  331.58  419.18 1142.47
Bank Sta=304.15,324.17
Exp/Cntr=0.3,0.1

Type RM Length L Ch R = 1 ,16788.53,58.01,57.87,60.19
XS GIS Cut Line= 2
  1354800.257915   793211.766841  1354169.730971   793238.545951
#Sta/Elev= 30
       0 1138.96   40.05 1136.39   75.07 1135.03  100.09 1134.67  170.15 1129.38
  180.16 1128.45  290.26 1125.61  295.27 1125.41  315.28 1123.59  325.29 1123.04
  340.31  1120.5  345.31  1120.5  350.32 1122.69  360.31 1130.24  365.33 1132.68
  370.33  1133.5  425.38 1135.05  430.39 1134.56  435.39 1133.21   440.4 1132.18
  450.41 1131.55  480.43 1131.23  515.45 1131.87  530.48 1131.33  540.49 1131.36
  565.51 1132.72  585.53 1134.43  590.53 1135.32  620.56 1142.01   631.1 1143.41
#Mann= 3 , 0 , 0
       0     .09       0  325.29    .055       0  350.32     .09       0
#XS Ineff= 2 , 0
                          424.82         1135.17
Permanent Ineff=
       F       F
#Block Obstruct= 1 ,-1
  363.51  439.65 1140.26
Bank Sta=325.29,350.32
Exp/Cntr=0.5,0.3

Type RM Length L Ch R = 1 ,16730.66,82.31,81.13,79.94
XS GIS Cut Line= 3
  1354867.085385   793164.276049  1354241.287511   793177.821484
  1353916.197678   793148.021583
#Sta/Elev= 30
       0 1138.38      10 1137.51   30.02 1139.61   50.01 1135.31   60.01 1135.88
   70.03 1134.06  105.02 1133.58  140.03 1131.04  180.04 1131.18  190.04 1129.97
  200.06  1131.4  210.05 1129.19  235.06 1128.48  260.06 1130.11  290.08 1127.04
  300.07  1128.5  350.08 1128.71  420.11 1125.83   430.1 1120.45   435.1 1120.88
  440.96 1125.44  445.22 1126.54  450.12 1130.01  455.12 1130.61  625.95 1131.08
  726.37 1134.14  786.62 1134.09  907.12 1130.86  932.23 1127.53   952.4 1130.37
#Mann= 3 , 0 , 0
       0     .09       0  420.11    .055       0  445.22     .09       0
#XS Ineff= 2 , 0
       0     413    1131  736.59       0    1135
Permanent Ineff=
       F       F
#Block Obstruct= 1 ,-1
  483.04  651.46 1136.99
Bank Sta=420.11,445.22
Exp/Cntr=0.5,0.3

Type RM Length L Ch R = 2 ,16687   ,,,
BEGIN DESCRIPTION:
37003-0098 Culvert X-ing (Commerce St.)
END DESCRIPTION:
Bridge Culvert--1,0,-1,-1, 0
Deck Dist Width WeirC Skew NumUp NumDn MinLoCord MaxHiCord MaxSubmerge Is_Ogee
15,30,2.6,0, 176, 174, , , 0.95, 0, 0,0,,
       0   38.17    45.3   48.33   54.27    56.5   65.94   70.97   75.34   77.91
   90.27   92.61   98.35  100.21   110.3  114.08  120.11  122.69  131.18  136.33
  140.81  143.54  151.03  157.37  164.28  165.12  172.58  178.61  178.95  182.15
  187.24  187.78  197.12  201.82   207.1  209.49   212.4  223.44  225.35  231.16
  241.19  245.34   247.9  254.52  261.64  268.54  272.97  276.67  282.95  290.55
  293.21  298.31  303.16  312.12  313.54  321.24  324.05  330.51  335.31  339.84
   343.7  346.72  357.83  364.47  365.36  366.64  379.37   387.6  388.08  388.57
  401.67  401.77  410.01  411.37  420.57  424.48   425.8   426.6  427.96   430.1
  432.05  434.84  443.89  446.05  453.83  460.43     467  472.49  475.67  482.38
  489.92  493.51  497.44   504.2  511.23  516.07  520.31  528.08  534.29  540.56
  544.56  552.42  559.04  566.65  567.19  567.64  568.98  577.75  580.62  584.91
  589.95  597.76  598.54  603.09  610.97  612.41  619.74  626.25  628.01   634.1
  640.47  648.27  651.13  656.73  662.64   670.2   678.6  679.47  680.53  693.17
  698.01  701.09  711.49  715.28  718.61  722.79  725.82  735.85  736.54  743.92
  745.54  751.14  758.74  761.09  767.84  771.69  778.25  786.09  789.05  801.38
  803.02  804.94  812.17  824.31  825.62  827.83  834.37  838.64  847.61  853.18
  855.04  858.15  868.75  872.67  877.88   887.1  890.85  897.54  899.63  904.88
  912.53  913.09  919.56  923.05  924.21    1000
 1139.26 1139.26 1138.91 1138.76 1138.33 1138.24 1138.03 1137.85 1137.49 1137.39
 1136.99 1136.86 1136.47 1136.43 1136.12 1135.97 1135.76 1135.68 1135.36 1135.14
 1134.98 1134.97 1135.01 1134.69 1134.18 1134.14 1133.79 1133.51 1133.51 1133.47
 1133.44 1133.43 1133.44  1133.3 1133.13 1133.03 1132.91  1132.5  1132.5 1132.47
 1132.23  1132.2 1132.11 1132.23 1132.22 1132.13  1131.9 1131.82 1131.61 1131.52
 1131.62 1131.78 1131.52  1131.3 1131.32 1131.26 1131.21 1131.14 1131.14 1131.11
 1131.13 1131.16  1131.2 1130.95 1130.91 1130.92 1131.04 1130.81 1130.79 1130.79
 1130.52 1130.52 1130.52 1130.53 1130.53 1130.53 1130.53 1130.53 1130.53 1130.53
 1130.53 1130.53 1130.53 1130.56 1130.59 1131.24  1131.5 1131.26  1131.2 1131.37
 1131.43 1131.05 1130.94 1130.72 1130.95 1130.97 1130.87    1131  1131.1 1131.31
 1131.38 1131.81 1131.77 1131.72 1131.71 1131.71 1131.67 1131.53 1131.54 1131.75
 1131.95 1131.89 1131.88 1131.74 1131.85 1131.88 1131.81 1131.78  1131.8 1131.97
 1131.95 1132.08 1132.04 1131.97 1131.87 1131.74  1131.7 1131.69 1131.68 1131.53
 1131.58 1131.61 1131.56 1131.48 1131.62 1131.63 1131.79 1131.38 1131.35 1131.25
 1131.26  1131.2 1131.03 1131.05 1131.12 1131.07 1130.99 1130.82 1130.77 1130.53
  1130.5 1130.47 1130.33 1130.13 1130.09 1130.06 1129.94 1129.83 1129.51 1129.62
  1129.6 1129.51 1129.39  1129.5 1129.41 1129.47 1129.46 1129.56 1129.62 1129.62
 1129.63 1129.66  1129.9 1130.09 1130.19 1130.19
                                                                                
                                                                                
                                                                                
                                                                                
                                                                                
                                                                                
                                                                                
                                                                                
                                                                                
                                                                                
                                                                                
                                                                                
                                                                                
                                                                                
                                                                                
                                                                                
                                                                                
                                                
   13.69   20.82   23.85   29.79   32.02   41.46   46.49   50.86   53.43   65.79
   68.13   73.87   75.73   85.82    89.6   95.63   98.21   106.7  111.85  116.33
  119.06  126.55  132.89   139.8  140.64   148.1  154.13  154.47  157.67  162.76
   163.3  172.64  177.34  182.62  185.01  187.92  198.96  200.87  206.68  216.71
  220.86  223.42  230.04  237.16  244.06  248.49  252.19  258.47  266.07  268.73
  273.83  278.68  287.64  289.06  296.76  299.57  306.03  310.83  315.36  319.22
  322.24  333.35  339.99  340.88  342.16  354.89  363.12   363.6  364.09  377.19
  377.29  385.53  386.89  396.09     400  401.32  402.12  403.48  405.62  407.57
  410.36  419.41  421.57  429.35  435.95  442.52  448.01  451.19   457.9  465.44
  469.03  472.96  479.72  486.75  491.59  495.83   503.6  509.81  516.08  520.08
  527.94  534.56  542.17  542.71  543.16   544.5  553.27  556.14  560.43  565.47
  573.28  574.06  578.61  586.49  587.93  595.26  601.77  603.53  609.62  615.99
  623.79  626.65  632.25  638.16  645.72  654.12  654.99  656.05  668.69  673.53
  676.61  687.01   690.8  694.13  698.31  701.34  711.37  712.06  719.44  721.06
  726.66  734.26  736.61  743.36  747.21  753.77  761.61  764.57   776.9  778.54
  780.46  787.69  799.83  801.14  803.35  809.89  814.16  823.13   828.7  830.56
  833.67  844.27  848.19   853.4  862.62  866.37  873.06  875.15   880.4  888.05
  888.61  895.08  898.57  899.73
 1139.26 1138.91 1138.76 1138.33 1138.24 1138.03 1137.85 1137.49 1137.39 1136.99
 1136.86 1136.47 1136.43 1136.12 1135.97 1135.76 1135.68 1135.36 1135.14 1134.98
 1134.97 1135.01 1134.69 1134.18 1134.14 1133.79 1133.51 1133.51 1133.47 1133.44
 1133.43 1133.44  1133.3 1133.13 1133.03 1132.91  1132.5  1132.5 1132.47 1132.23
  1132.2 1132.11 1132.23 1132.22 1132.13  1131.9 1131.82 1131.61 1131.52 1131.62
 1131.78 1131.52  1131.3 1131.32 1131.26 1131.21 1131.14 1131.14 1131.11 1131.13
 1131.16  1131.2 1130.95 1130.91 1130.92 1131.04 1130.81 1130.79 1130.79 1130.52
 1130.52 1130.52 1130.52 1130.52 1130.52 1130.52 1130.52 1130.52 1130.52 1130.52
 1130.52 1130.52 1130.56 1130.59 1131.24  1131.5 1131.26  1131.2 1131.37 1131.43
 1131.05 1130.94 1130.72 1130.95 1130.97 1130.87    1131  1131.1 1131.31 1131.38
 1131.81 1131.77 1131.72 1131.71 1131.71 1131.67 1131.53 1131.54 1131.75 1131.95
 1131.89 1131.88 1131.74 1131.85 1131.88 1131.81 1131.78  1131.8 1131.97 1131.95
 1132.08 1132.04 1131.97 1131.87 1131.74  1131.7 1131.69 1131.68 1131.53 1131.58
 1131.61 1131.56 1131.48 1131.62 1131.63 1131.79 1131.38 1131.35 1131.25 1131.26
  1131.2 1131.03 1131.05 1131.12 1131.07 1130.99 1130.82 1130.77 1130.53  1130.5
 1130.47 1130.33 1130.13 1130.09 1130.06 1129.94 1129.83 1129.51 1129.62  1129.6
 1129.51 1129.39  1129.5 1129.41 1129.47 1129.46 1129.56 1129.62 1129.62 1129.63
 1129.66  1129.9 1130.09 1130.19
                                                                                
                                                                                
                                                                                
                                                                                
                                                                                
                                                                                
                                                                                
                                                                                
                                                                                
                                                                                
                                                                                
                                                                                
                                                                                
                                                                                
                                                                                
                                                                                
                                                                                
                                
BR Coef=-1 , 0 , 0 ,, 0 ,,,0.8,-1,,0,
WSPro=,,,, 1 ,,,, 0 ,,,, 0 ,,,,-1 ,-1 ,-1 , 0 , 0 , 0 , 0 , 0
Culvert=1,7,,80,0.027,0.9,1,2,3,1120.45,431.9,1119.5,403.52,Culvert #1  , 0 ,0
Culvert Bottom n=0.027
BR U #Sta/Elev= 174
       0 1138.38       5 1137.34      10 1137.51      15 1137.75      20 1138.42
   25.02 1139.34   30.02 1139.61   35.02  1138.5   40.02 1137.84   45.01 1136.39
   50.01 1135.31   55.01 1135.72   60.01 1135.88   65.03 1134.72   70.03 1134.06
   75.03 1134.02   80.03 1133.96   90.02 1133.17   95.02 1133.05  100.02 1133.62
  105.02 1133.58  115.04  1133.1  120.04  1132.9  125.03 1132.63  130.03 1132.01
  135.03 1131.38  140.03 1131.04  145.03 1131.38  150.05  1131.3  155.05 1131.06
  160.05 1130.84  165.05 1130.71  170.04 1130.72  175.04 1131.06  180.04 1131.18
  185.04 1130.46  190.04 1129.97  195.06 1130.93  200.06  1131.4  205.06 1130.21
  210.05 1129.19  215.05 1129.12  225.05 1128.79  230.05 1128.61  235.06 1128.48
  240.07 1128.54  245.07 1128.97  250.07 1129.54  255.06 1130.04  260.06 1130.11
  265.06 1129.64  270.06 1128.83  275.06 1128.33  280.08 1128.06  285.08 1127.38
  290.08 1127.04  295.07 1127.73  300.07  1128.5  305.07 1128.44  310.07 1128.41
  315.07 1128.29  320.07 1128.18  325.09 1128.49  330.09 1128.89  335.09 1128.22
  340.08 1127.87  345.08 1128.46  350.08 1128.71  355.08 1127.88  360.08 1127.33
   365.1 1127.87   370.1  1127.7   375.1 1126.96  380.09 1126.55  390.09 1127.58
  395.09  1127.5  400.09 1127.43   405.1 1126.96  410.11 1125.86  415.11 1126.04
  420.11 1125.83   425.1 1121.27   430.1 1120.45   435.1 1120.45   440.1  1121.7
   445.1 1127.33  450.12 1130.01  455.12 1130.61  460.12 1130.63  465.11 1130.61
  470.11 1130.61  475.11 1130.67  480.11  1130.7  485.11 1130.71  490.12 1130.74
  495.13 1130.79  500.13  1130.8  505.12 1130.78  510.12 1130.77  515.12 1130.78
  525.12 1130.87  530.12 1130.93  535.14 1131.02  540.14 1131.15  550.13 1131.37
  555.13 1131.42  560.13 1131.37  565.13 1131.34  575.14 1131.43  580.15 1131.46
  590.14 1131.38  595.14 1131.35  600.14  1131.3  605.14 1131.28  610.14 1131.29
  615.14 1131.22  620.16  1131.1  625.95 1131.08  635.99 1131.49  641.01 1131.67
  646.03 1131.92  651.05 1132.29  656.07 1132.53  661.09 1132.57  666.11 1132.55
  671.14 1132.65  676.16 1132.88  681.19    1133   686.2  1133.1  691.22 1133.27
  696.24  1133.5  701.26 1133.64  716.32 1133.91  721.35 1134.05  726.37 1134.14
  736.41 1134.14  746.45 1134.11  756.49 1134.14  761.51 1134.12  766.53 1134.08
  776.58 1134.07   781.6  1134.1  786.62 1134.09  796.66 1133.78   806.7 1133.42
  811.72 1133.15  816.74 1132.74  821.76 1132.37  826.79  1132.3  831.81 1132.65
  836.83 1132.86  841.85 1132.81  846.87 1132.61  851.89 1132.45  856.91 1132.26
  861.93 1131.97  866.95 1131.71  871.97 1131.54  876.99 1131.43  882.02  1131.3
  887.04 1131.14  892.06 1131.03  897.08 1130.96   902.1 1130.92  907.12 1130.86
  912.14 1130.67  917.16 1130.16  922.18 1129.39  927.21 1128.37  932.23 1127.53
  937.25 1127.73  942.27 1128.81  947.29  1129.6   952.4 1130.37
BR U #Mann= 3
       0      .1   425.1    .055   440.1      .1
BR U Banks=420.11,445.1
BR D #Sta/Elev= 152
       0 1139.53    4.99 1139.72    9.99 1139.88   20.01 1139.51   25.01 1139.34
   30.01 1139.18   35.01 1139.06      40 1139.15      45 1139.05      50 1139.04
   55.02 1139.04   65.02    1139   70.02 1138.99   75.01 1139.06   80.01 1138.93
   85.01 1138.93   90.03  1138.9   95.03 1138.85  100.03 1138.76  105.03 1138.53
  110.02 1138.26  115.02 1138.02  120.04 1137.81  125.04 1137.78  130.04 1137.45
  135.04 1137.32  140.04 1137.17  145.03 1136.72  150.03    1136  155.05 1135.21
  160.05 1134.48  165.05 1133.71  170.05 1132.96  175.05 1132.65  185.04 1132.01
  190.06 1131.91  195.06 1131.85  205.06 1131.83  210.06 1131.76  215.05 1131.65
  220.05 1131.57  230.07 1131.44  235.07 1131.34  240.07 1131.25  245.07 1131.18
  250.06 1131.17  255.06 1131.17  260.08 1131.15  265.08 1131.16  270.08 1131.18
  275.08 1131.18  285.07 1131.13  290.08 1131.02  295.09 1130.94  300.09 1130.88
  305.09 1130.84  310.09 1130.75  315.08 1130.65  320.08 1130.59   325.1  1130.6
   330.1 1130.54   335.1 1130.45   340.1 1130.42   345.1 1130.51  350.09 1130.58
  355.09 1130.57  360.11 1130.51  365.11 1130.02  370.11    1129  375.11 1127.67
  380.11  1126.5   385.1 1125.42   390.1 1124.51  395.12 1122.36  400.12  1119.5
  405.12  1119.5  410.12 1121.55  415.12  1123.3  420.11 1123.44  425.11 1123.67
  430.13 1125.04  435.13 1126.18  440.13  1127.6  445.13 1129.13  450.13 1129.96
  455.12 1130.04  460.12 1130.11  465.14 1129.82  470.14 1129.48  475.14 1129.36
  480.14 1129.29  485.14 1129.27  490.13  1129.3  495.15 1129.38  500.15 1129.65
  505.15 1129.93  510.15 1130.23  515.15 1130.47  520.15 1130.73  525.14 1131.07
  530.16 1131.32  545.16 1131.74  550.16 1131.64  555.15 1131.67  569.63 1131.93
  574.65 1132.06  579.67 1132.15  589.72 1132.22  594.74 1132.28  609.79 1132.34
  614.82 1132.37  619.84 1132.41  629.88 1132.57   634.9 1132.58  639.92 1132.65
  649.97 1132.52  654.99 1132.47     660 1132.65  665.02 1132.78  670.05 1132.78
  675.07 1132.75  680.09 1132.69  685.11 1132.64  690.13 1132.57  695.16 1132.52
  700.18  1132.5  720.26  1132.5  725.28  1132.4  740.34 1132.06  745.36 1131.84
  750.39 1131.53  755.41 1131.12  760.43 1130.83  765.44 1130.75  770.46 1130.41
  775.49    1130  785.53 1129.23  790.55 1128.99  795.57 1128.85   800.6 1128.72
  810.64 1128.84  815.66 1128.84  820.67 1128.73   825.7 1128.59  830.72 1128.53
  840.76 1128.58  855.83 1128.59  860.85 1128.86  870.88 1129.72  875.91 1129.95
  880.93 1130.13  886.04 1130.82
BR D #Mann= 3
       0      .1  395.12    .055  410.12      .1
BC Design=,, 0 ,, 0 ,,,,,,

Type RM Length L Ch R = 1 ,16649.53,68.42,68.8,69.18
XS GIS Cut Line= 3
  1354798.003788   793093.839983  1354238.578434   793107.385371
    1353913.4886    793077.58547
#Sta/Elev= 30
       0 1139.53    9.99 1139.88   35.01 1139.06   95.03 1138.85  125.04 1137.78
  145.03 1136.72  170.05 1132.96  185.04 1132.01  245.07 1131.18  360.11 1130.51
  365.11 1130.02   385.1 1125.42  395.12 1124.06  405.12  1119.5  410.12 1123.25
  425.11 1123.67  445.13 1129.13  450.13 1129.96  480.14 1129.29  495.15 1129.38
  530.16 1131.32  545.16 1131.74  665.02 1132.78  720.26  1132.5  745.36 1131.84
  790.55 1128.99  830.72 1128.53  855.83 1128.59  880.93 1130.13  886.04 1130.82
#Mann= 3 , 0 , 0
       0     .09       0  395.12    .055       0  425.11     .09       0
#XS Ineff= 2 , 0
       0     385    1128  664.53       0    1135
Permanent Ineff=
       F       F
#Block Obstruct= 1 ,-1
     590     722 1136.99
Bank Sta=395.12,425.11
Exp/Cntr=0.5,0.3

Type RM Length L Ch R = 1 ,16580.73,235.82,223.74,211.62
XS GIS Cut Line= 2
  1354717.486016    793034.05075  1353899.505118   793053.526474
#Sta/Elev= 30
       0 1139.55   30.02 1139.54   70.02 1138.07   85.02 1136.27  100.04 1133.31
  110.03  1131.9  160.06 1131.23  215.06 1131.08   315.1 1129.63  320.09 1128.92
   335.1 1125.11  340.11 1123.54   345.1 1121.04  350.11 1118.81   355.1 1118.06
   370.1 1121.36  390.11 1126.85  405.11 1127.96  415.13 1128.15  430.12 1127.64
  455.14 1127.55  465.13 1128.02  490.15 1130.15  635.19 1131.68   665.2  1128.6
  695.21  1128.7  735.22 1127.71  755.21 1127.63  785.22  1128.8  818.21 1133.04
#Mann= 3 , 0 , 0
       0     .09       0   345.1    .055       0   370.1     .09       0
#XS Ineff= 2 , 0
                          634.11          1131.8
Permanent Ineff=
       F       F
#Block Obstruct= 1 ,-1
  483.04  651.46 1136.99
Bank Sta=345.1,370.1
Exp/Cntr=0.3,0.1