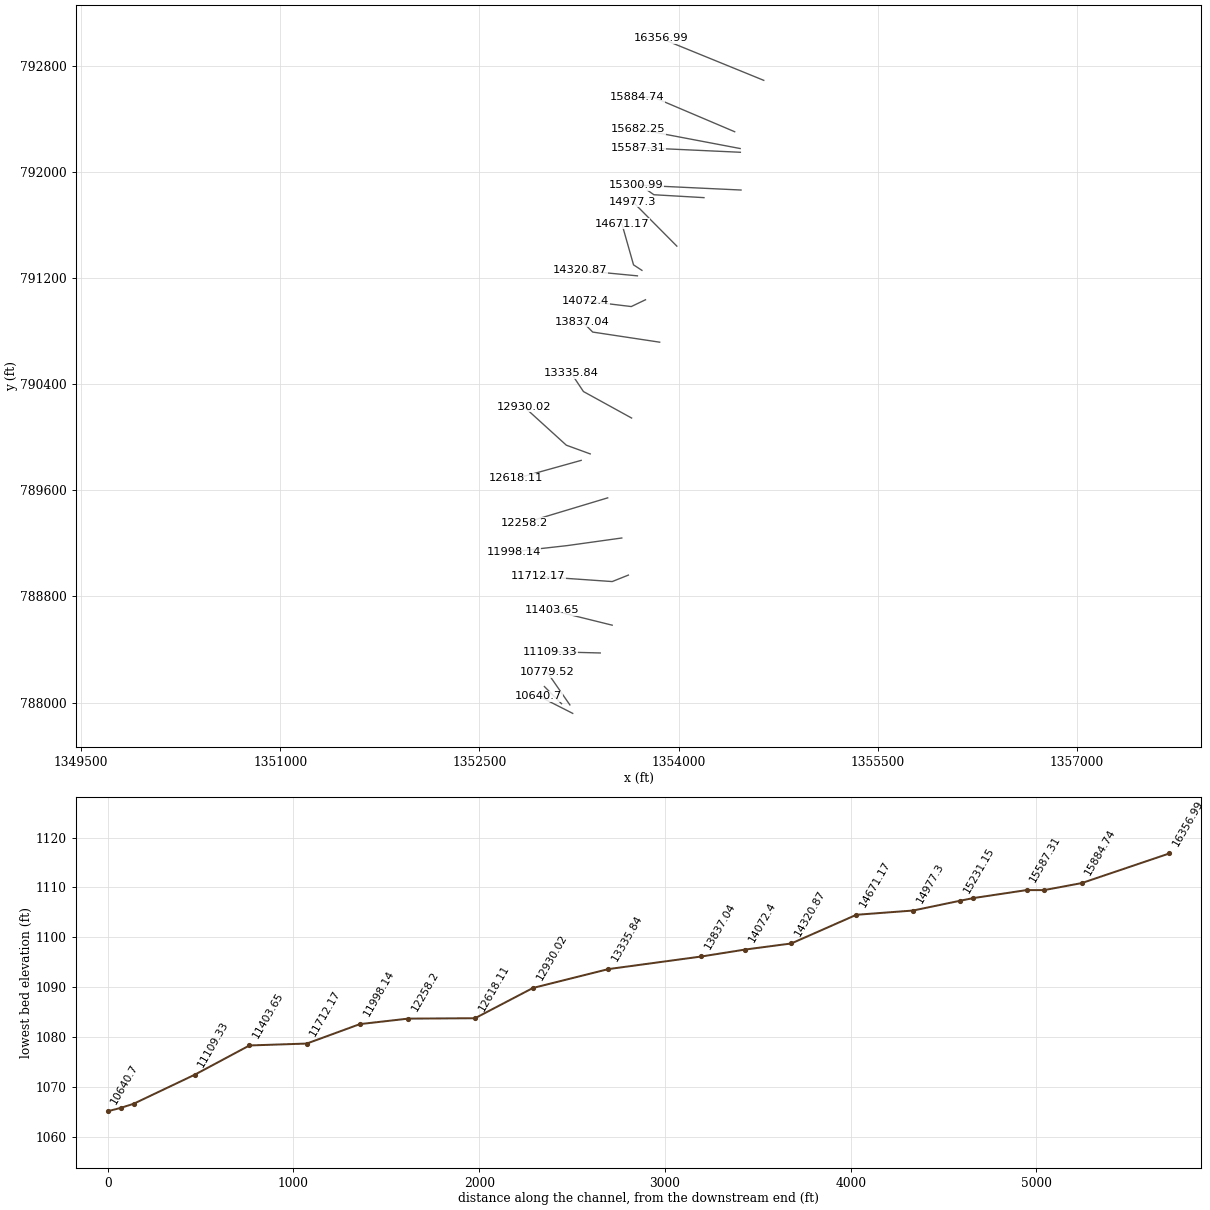
HEC-RAS study StirewaitCr.prj: StirewaitCr

--- StirewaitCr.g01 (geometry) --- (continued)

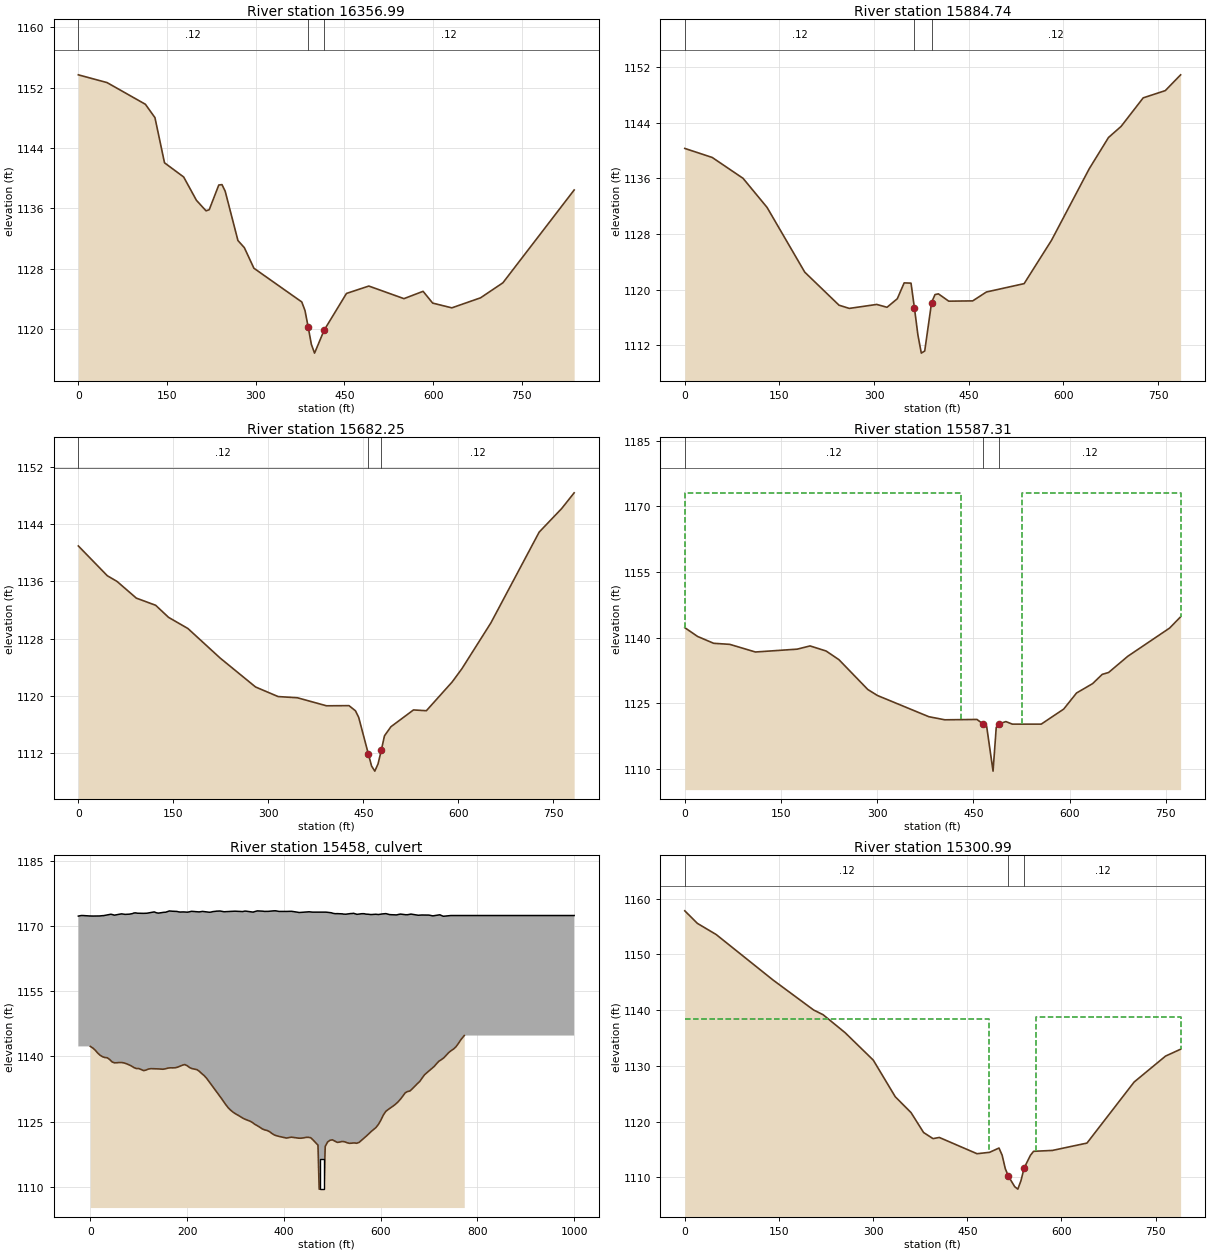
Type RM Length L Ch R = 1 ,16356.99,471.04,472.26,463.5
XS GIS Cut Line= 2
  1354642.017548   792688.356429  1353865.422576   793004.837116
#Sta/Elev= 30
       0  1153.7   48.59 1152.67  113.38  1149.8  129.58 1148.03  145.78 1142.04
  178.18 1140.16  199.77 1137.07  215.97 1135.68  221.37 1135.82  237.57  1139.1
  242.97 1139.15  248.37 1138.28  269.96 1131.74  280.76  1130.8  296.96 1128.07
  377.95  1123.6  383.35 1122.47  388.75 1120.28  394.15 1117.98  399.54 1116.82
  415.74 1119.86  453.54 1124.73  491.33 1125.71  550.72 1124.04  583.12 1125.01
  599.31 1123.45  631.71 1122.82  680.31 1124.15   718.1 1126.14  838.61 1138.44
#Mann= 3 , 0 , 0
       0     .12       0  388.75    .055       0  415.74     .12       0
Bank Sta=388.75,415.74
Exp/Cntr=0.3,0.1

Type RM Length L Ch R = 1 ,15884.74,195.99,202.49,208.84
XS GIS Cut Line= 3
   1354422.91553   792301.276182  1353809.429833   792561.764126
  1353690.140962   792561.764126
#Sta/Elev= 30
       0  1140.3   43.46    1139   92.34    1136  130.37 1131.82  190.12 1122.51
  244.44 1117.76  260.74  1117.3  304.19 1117.87  320.49 1117.46  336.79 1118.69
  347.65 1120.97  358.53 1120.93  363.96 1117.34  369.38 1113.52  374.81 1110.87
  380.24 1111.18  391.11 1118.14  396.54 1119.29  401.97 1119.39  418.27 1118.34
  456.29 1118.38  478.02 1119.66  537.77 1120.86  581.23  1127.1  640.98 1137.38
   671.5 1141.87   691.5 1143.47   726.5 1147.57   761.5 1148.61  785.79 1150.88
#Mann= 3 , 0 , 0
       0     .12       0  363.96    .055       0  391.11     .12       0
Bank Sta=363.96,391.11
Exp/Cntr=0.3,0.1

Type RM Length L Ch R = 1 ,15682.25,90.67,94.94,99.22
XS GIS Cut Line= 2
  1354464.301456   792174.683879   1353695.00987   792320.751907
#Sta/Elev= 30
       0 1140.96    45.8 1136.79   61.07    1136   91.61 1133.66  122.14 1132.66
   142.5 1130.97  173.04 1129.41  223.93 1125.28   279.9 1121.23  315.54 1119.89
  346.07 1119.72  391.88  1118.6  427.49 1118.62  437.67  1117.9  442.76 1116.98
  458.04 1111.86  463.13 1110.17  468.22 1109.46  473.31 1110.47   478.4 1112.35
  483.49  1114.4  493.67 1115.67  529.29 1118.02  549.65 1117.91  590.35 1121.93
  605.63 1123.77  651.43 1130.18  727.77 1142.89   763.4  1146.2  783.04 1148.39
#Mann= 3 , 0 , 0
       0     .12       0  458.04    .055       0   478.4     .12       0
Bank Sta=458.04,478.4
Exp/Cntr=0.5,0.3

Type RM Length L Ch R = 1 ,15587.31,286.04,286.32,286.47
XS GIS Cut Line= 2
  1354465.802655   792146.507925  1353693.714354   792182.064657
#Sta/Elev= 30
       0 1142.27   20.02 1140.26   45.05  1138.7   70.06 1138.46  110.12 1136.71
  175.19 1137.36  195.21  1138.1  220.22 1136.94  240.24 1134.96  285.29 1128.13
  300.32 1126.76  380.39 1121.91  405.43  1121.2  455.47 1121.28  465.48 1120.18
   470.5 1119.77  480.51 1109.46   485.5 1119.48  490.52 1120.31  500.53 1120.79
  510.53 1120.21  555.59 1120.21  590.63 1123.65  610.65 1127.33  635.66 1129.47
  650.69 1131.59  660.69 1132.03  690.72 1135.75  755.79 1142.19  772.91 1144.77
#Mann= 3 , 0 , 0
       0     .12       0  465.48    .055       0  490.52     .12       0
#XS Ineff= 2 , 0
       0     430 1173.12     525       0 1173.12
Permanent Ineff=
       F       F
Bank Sta=465.48,490.52
Exp/Cntr=0.5,0.3

Type RM Length L Ch R = 2 ,15458   ,,,
BEGIN DESCRIPTION:
37003-0044 Culvert X-ing (SR # 64)
END DESCRIPTION:
Bridge Culvert--1,0,-1,-1, 0
Deck Dist Width WeirC Skew NumUp NumDn MinLoCord MaxHiCord MaxSubmerge Is_Ogee
113,50,2.6,0, 150, 150, , , 0.95, 0, 0,0,,
   -24.8  -24.01  -18.81  -17.37  -15.21    -1.8    3.05    5.46   19.08   21.45
   26.18   27.11   37.24   42.61    47.6   49.46   59.87   64.21   66.17   71.94
   81.08   87.22   90.03   93.67   97.52  107.33  108.84  109.43  116.38  116.85
  116.93  132.04  136.77  140.51   151.9  155.71  158.33  163.25  170.61  178.88
  182.73  185.99  192.14  201.03  203.66  209.25   219.8  223.99  224.89  231.21
  231.88  246.19  249.25  253.17  261.61  268.32  274.37  276.32  287.34  291.43
   295.1  298.76  308.22  314.73  319.47  321.53  334.73  336.66  337.81  345.05
  356.85  359.76  367.06  367.96  379.27  383.28   389.5  390.15  400.42  406.01
   412.8  414.14  415.97  429.16  431.16  437.42   438.7  444.96  451.04  452.25
  453.53  458.94  467.45   475.4  479.48  480.19  481.01  484.99  487.26   498.3
  501.34  506.33  510.45  521.28   522.5  528.53  530.48  537.03  542.27  543.83
   550.9  551.13  560.88  565.66  570.24  573.87  579.95  588.62  590.05   595.6
  604.47  610.82  616.71  617.84  618.69   632.8  637.71   641.2  651.99  655.79
  660.77  662.82  670.54  677.96  684.28  684.83  698.97  699.24   699.7  707.85
  716.79  722.38  727.35  729.89  743.61  745.05  751.54  751.92  759.87    1000
 1172.24 1172.26 1172.37 1172.37 1172.37 1172.27 1172.26 1172.25 1172.27  1172.3
 1172.35 1172.34 1172.55 1172.67 1172.53 1172.45 1172.67 1172.75 1172.73 1172.63
 1172.69 1172.82 1172.95 1172.98  1172.9 1172.88  1172.9 1172.87  1172.9  1172.9
  1172.9  1173.2    1173 1172.92 1173.11 1173.13 1173.23 1173.42 1173.35 1173.31
 1173.21 1173.17  1173.2 1173.14  1173.2 1173.34 1173.23 1173.19  1173.2 1173.32
 1173.32 1173.12 1173.16 1173.27 1173.38 1173.41 1173.27 1173.24  1173.3  1173.3
 1173.35 1173.37 1173.32 1173.28 1173.39 1173.38 1173.17 1173.15 1173.21 1173.44
 1173.37 1173.32 1173.33 1173.33 1173.45 1173.45 1173.31 1173.31 1173.31 1173.31
 1173.35 1173.34 1173.34 1173.12 1173.06 1173.11 1173.12 1173.18 1173.23 1173.23
 1173.21 1173.15 1173.15 1173.15 1173.15 1173.15 1173.15 1173.15 1173.15    1173
 1172.88 1172.79 1172.81 1172.75  1172.7 1172.67 1172.71 1172.81 1172.85 1172.89
 1172.65 1172.64 1172.79 1172.79 1172.68 1172.67 1172.59 1172.65 1172.66  1172.6
 1172.75 1172.81 1172.63 1172.58 1172.58 1172.51 1172.64  1172.7 1172.55 1172.56
 1172.66  1172.7 1172.57 1172.43 1172.48 1172.49 1172.48 1172.48 1172.47 1172.29
 1172.44 1172.54 1172.29  1172.2 1172.37 1172.37 1172.38 1172.38 1172.37 1172.37
                                                                                
                                                                                
                                                                                
                                                                                
                                                                                
                                                                                
                                                                                
                                                                                
                                                                                
                                                                                
                                                                                
                                                                                
                                                                                
                                                                                
                                                                                
       0    25.6   26.39   31.59   33.03   35.19    48.6   53.45   55.86   69.48
   71.85   76.58   77.51   87.64   93.01      98   99.86  110.27  114.61  116.57
  122.34  131.48  137.62  140.43  144.07  147.92  157.73  159.24  159.83  166.78
  167.25  167.33  182.44  187.17  190.91   202.3  206.11  208.73  213.65  221.01
  229.28  233.13  236.39  242.54  251.43  254.06  259.65   270.2  274.39  275.29
  281.61  282.28  296.59  299.65  303.57  312.01  318.72  324.77  326.72  337.74
  341.83   345.5  349.16  358.62  365.13  369.87  371.93  385.13  387.06  388.21
  395.45  407.25  410.16  417.46  418.36  429.67  433.68   439.9  440.55  450.82
  456.41   463.2  464.54  466.37  479.56  481.56  487.82   489.1  495.36  501.44
  502.65  503.93  509.34  517.85   525.8  529.88  530.59  531.41  535.39  537.66
   548.7  551.74  556.73  560.85  571.68   572.9  578.93  580.88  587.43  592.67
  594.23   601.3  601.53  611.28  616.06  620.64  624.27  630.35  639.02  640.45
     646  654.87  661.22  667.11  668.24  669.09   683.2  688.11   691.6  702.39
  706.19  711.17  713.22  720.94  728.36  734.68  735.23  749.37  749.64   750.1
  758.25  767.19  772.78  777.75  780.29  794.01  795.45  801.94  802.32  810.27
 1172.24 1172.24 1172.26 1172.37 1172.37 1172.37 1172.27 1172.26 1172.25 1172.27
  1172.3 1172.35 1172.34 1172.55 1172.67 1172.53 1172.45 1172.67 1172.75 1172.73
 1172.63 1172.69 1172.82 1172.95 1172.98  1172.9 1172.88  1172.9 1172.87  1172.9
  1172.9  1172.9  1173.2    1173 1172.92 1173.11 1173.13 1173.23 1173.42 1173.35
 1173.31 1173.21 1173.17  1173.2 1173.14  1173.2 1173.34 1173.23 1173.19  1173.2
 1173.32 1173.32 1173.12 1173.16 1173.27 1173.38 1173.41 1173.27 1173.24  1173.3
  1173.3 1173.35 1173.37 1173.32 1173.28 1173.39 1173.38 1173.17 1173.15 1173.21
 1173.44 1173.37 1173.32 1173.33 1173.33 1173.45 1173.45 1173.31 1173.31 1173.31
 1173.31 1173.35 1173.34 1173.34 1173.12 1173.06 1173.11 1173.12 1173.18 1173.23
 1173.23 1173.21 1173.15 1173.15 1173.15 1173.15 1173.15 1173.15 1173.15 1173.15
    1173 1172.88 1172.79 1172.81 1172.75  1172.7 1172.67 1172.71 1172.81 1172.85
 1172.89 1172.65 1172.64 1172.79 1172.79 1172.68 1172.67 1172.59 1172.65 1172.66
  1172.6 1172.75 1172.81 1172.63 1172.58 1172.58 1172.51 1172.64  1172.7 1172.55
 1172.56 1172.66  1172.7 1172.57 1172.43 1172.48 1172.49 1172.48 1172.48 1172.47
 1172.29 1172.44 1172.54 1172.29  1172.2 1172.37 1172.37 1172.38 1172.38 1172.37
                                                                                
                                                                                
                                                                                
                                                                                
                                                                                
                                                                                
                                                                                
                                                                                
                                                                                
                                                                                
                                                                                
                                                                                
                                                                                
                                                                                
                                                                                
BR Coef=-1 , 0 , 0 ,, 0 ,,,0.8,-1,,0,
WSPro=,,,, 1 ,,,, 0 ,,,, 0 ,,,,-1 ,-1 ,-1 , 0 , 0 , 0 , 0 , 0
Culvert=2,7,9,225,0.013,0.4,1,8,1,1109.46,478.52,1107.86,530.28,Culvert #1  , 0 ,26
Culvert Bottom n=0.013
BR U #Sta/Elev= 148
       0 1142.27    5.01 1141.91   10.01 1141.42   15.02 1140.77   20.02 1140.26
   25.03 1139.91   30.03 1139.72   35.04 1139.66   40.03 1139.26   45.05  1138.7
   50.04  1138.5   55.06 1138.52   60.05 1138.57   65.07 1138.57   70.06 1138.46
   75.08 1138.27   80.07 1138.03   85.09 1137.76    90.1 1137.41    95.1 1137.19
  100.11 1137.18  105.11 1136.96  110.12 1136.71  115.11 1136.83  120.13 1137.07
  125.12 1137.16  135.13 1137.13  140.15  1137.1  145.14 1137.06  150.16 1137.03
  155.15 1137.12  160.17 1137.28  165.16 1137.35  170.18 1137.34  175.19 1137.36
  180.19 1137.49   185.2 1137.71   190.2 1137.95  195.21  1138.1   200.2 1137.84
  205.22 1137.41  210.21 1137.17  215.23 1137.06  220.22 1136.94  225.24 1136.55
  230.23 1136.03  235.25 1135.56  240.24 1134.96  245.26  1134.2  250.25 1133.41
  255.27 1132.65  265.28 1131.19  270.29 1130.42  275.28 1129.61   280.3 1128.83
  285.29 1128.13  290.31 1127.58   295.3 1127.13  300.32 1126.76  305.31 1126.45
  310.33  1126.1  315.32 1125.77  320.34  1125.5  325.33 1125.28  330.35 1125.08
  335.36 1124.75  340.36 1124.33  345.37 1124.03  350.36 1123.69  355.38  1123.3
  360.37 1123.08  365.39 1122.94  370.38 1122.68   375.4 1122.25  380.39 1121.91
  385.41 1121.72   390.4 1121.57  395.42 1121.45  400.41 1121.31  405.43  1121.2
  410.42 1121.31  415.44 1121.41  430.46 1121.18  435.45 1121.17  440.47 1121.24
  445.46 1121.35  450.48 1121.38  455.47 1121.28  460.49 1120.75  465.48 1120.18
   470.5 1119.57     473 1109.46  475.49 1109.46  480.51 1109.46     483 1109.46
   485.5 1119.28  490.52 1120.31  495.51  1120.7  500.53 1120.79  505.54 1120.48
  510.53 1120.21  515.55 1120.28  520.54 1120.42  525.56 1120.35  530.55 1120.13
  535.57 1119.99  540.56 1120.04  545.58 1120.08  550.57 1120.01  555.59 1120.21
  570.59 1121.66  575.61 1122.18   580.6 1122.71  585.61 1123.17  590.63 1123.65
  595.62 1124.36  600.64 1125.35  605.63 1126.49  610.65 1127.33  615.64 1127.76
  625.65 1128.54  630.67 1128.97  635.66 1129.47  640.68  1130.1  645.67 1130.81
  650.69 1131.59  655.68  1131.9  660.69 1132.03  665.69 1132.55   670.7 1133.13
  675.72 1133.68  680.71  1134.2  690.72 1135.75  700.73  1136.7  705.75 1137.16
  710.74 1137.67  715.76 1138.31  720.75  1138.9  725.77 1139.24  730.76 1139.66
  735.78 1140.28  740.77 1140.86  745.78  1141.3  750.79 1141.67  755.79 1142.19
  760.81 1142.96   765.8  1143.8  772.91 1144.77
BR U #Mann= 3
       0      .1   470.5    .055   485.5      .1
BR D #Sta/Elev= 145
       0 1157.84    5.01 1157.32   10.01 1156.73   15.02 1156.12   20.02 1155.59
   25.03 1155.25   30.02 1155.02   35.04 1154.65   40.03 1154.27   45.05 1153.95
   50.06 1153.58   55.06 1153.06   60.07 1152.48   65.07 1152.02   70.08 1151.63
   75.07 1151.23   80.09 1150.78   85.09 1150.32    90.1 1149.87   95.11 1149.39
  100.11  1148.9  105.12  1148.5  110.12 1148.18  115.13 1147.84  120.12 1147.48
  125.14 1147.03  130.14 1146.51  135.15 1145.97  140.16 1145.45  145.16 1145.03
  150.17 1144.71  155.16 1144.31  160.18 1143.82  165.17 1143.36  170.19 1142.99
  175.19 1142.65   180.2 1142.22  185.21 1141.73  190.21 1141.26  195.22 1140.83
  205.23 1140.03  210.22 1139.69  215.24 1139.46  220.25 1139.19  225.25 1138.76
  235.26 1137.71  240.27 1137.24  250.28  1136.4  255.27 1135.97  260.29  1135.4
   265.3 1134.73   270.3  1134.2  275.31 1133.78  280.31 1133.26  290.31 1132.17
  295.33 1131.64  300.32 1131.02  305.34 1130.24  310.35 1129.37  315.35 1128.44
  320.36 1127.48  325.36 1126.43  330.37 1125.39  335.36 1124.44  340.38 1123.66
  345.37 1123.13  350.39 1122.68   355.4 1122.26   360.4 1121.61  370.41 1119.68
  375.42 1118.75  380.41 1118.03  385.43 1117.57  390.43  1117.2  395.44 1116.93
  405.45 1117.14  410.46 1116.85  420.47 1116.19  425.46 1115.89  430.48 1115.66
  435.48 1115.52  440.49 1115.47   445.5 1115.36   450.5 1115.11  455.51 1114.78
   460.5 1114.44  465.52 1114.22  470.51 1114.15  475.53  1114.2  480.53 1114.35
  485.54 1114.47  490.55 1114.63  495.55 1114.92  500.56 1115.24  505.55 1113.96
  510.57 1111.54  515.56 1110.17  520.58 1109.25  525.58 1107.86  530.59 1107.86
   535.6 1107.86   540.6 1111.65  545.61 1112.87   550.6 1113.93  555.62 1114.65
  560.61 1114.81  565.63  1114.8  570.63 1114.78  580.65 1114.78  585.65 1114.81
  595.65 1115.03  600.67 1115.12  605.66  1115.3  615.68 1115.74  620.69 1115.89
   625.7 1115.87   630.7 1115.84  635.71 1115.91   640.7 1116.13  645.72 1116.68
  655.73 1118.35  660.74 1119.11  665.74 1119.93  670.75 1120.69  675.75 1121.42
  685.75 1122.96  690.77 1123.63  695.77 1124.27  705.79  1125.6  710.79 1126.35
   715.8 1127.09  720.79 1127.61  725.81 1127.97   730.8 1128.36  735.82 1128.79
  745.83 1129.78  750.84  1130.3  755.84 1130.84  760.85 1131.35  765.84 1131.75
  770.86 1131.99  775.85 1132.13  780.87 1132.32  785.86 1132.67   789.9 1132.99
BR D #Mann= 3
       0      .1  520.58    .055   540.6      .1
BC Design=,, 0 ,, 0 ,,,,,,

Type RM Length L Ch R = 1 ,15300.99,70.45,69.84,69.21
XS GIS Cut Line= 2
  1354470.882182    791862.05435   1353681.86211   791899.304227
#Sta/Elev= 30
       0 1157.84   20.02 1155.59   50.06 1153.58  140.16 1145.45  205.23 1140.03
  220.25 1139.19  255.27 1135.97  300.32 1131.02  335.36 1124.44   360.4 1121.61
  380.41 1118.03  395.44 1116.93  405.45 1117.14  465.52 1114.22  485.54 1114.47
  500.56 1115.24  505.55 1113.96  510.57 1111.54  515.56 1110.17  525.58  1108.3
  530.59 1107.86   535.6  1109.4   540.6 1111.65   550.6 1113.93  555.62 1114.65
  585.65 1114.81   640.7 1116.13   715.8 1127.09  765.84 1131.75   789.9 1132.99
#Mann= 3 , 0 , 0
       0     .12       0  515.56    .055       0   540.6     .12       0
#XS Ineff= 2 , 0
       0     485 1138.42     560       0 1138.69
Permanent Ineff=
       F       F
Bank Sta=515.56,540.6
Exp/Cntr=0.5,0.3

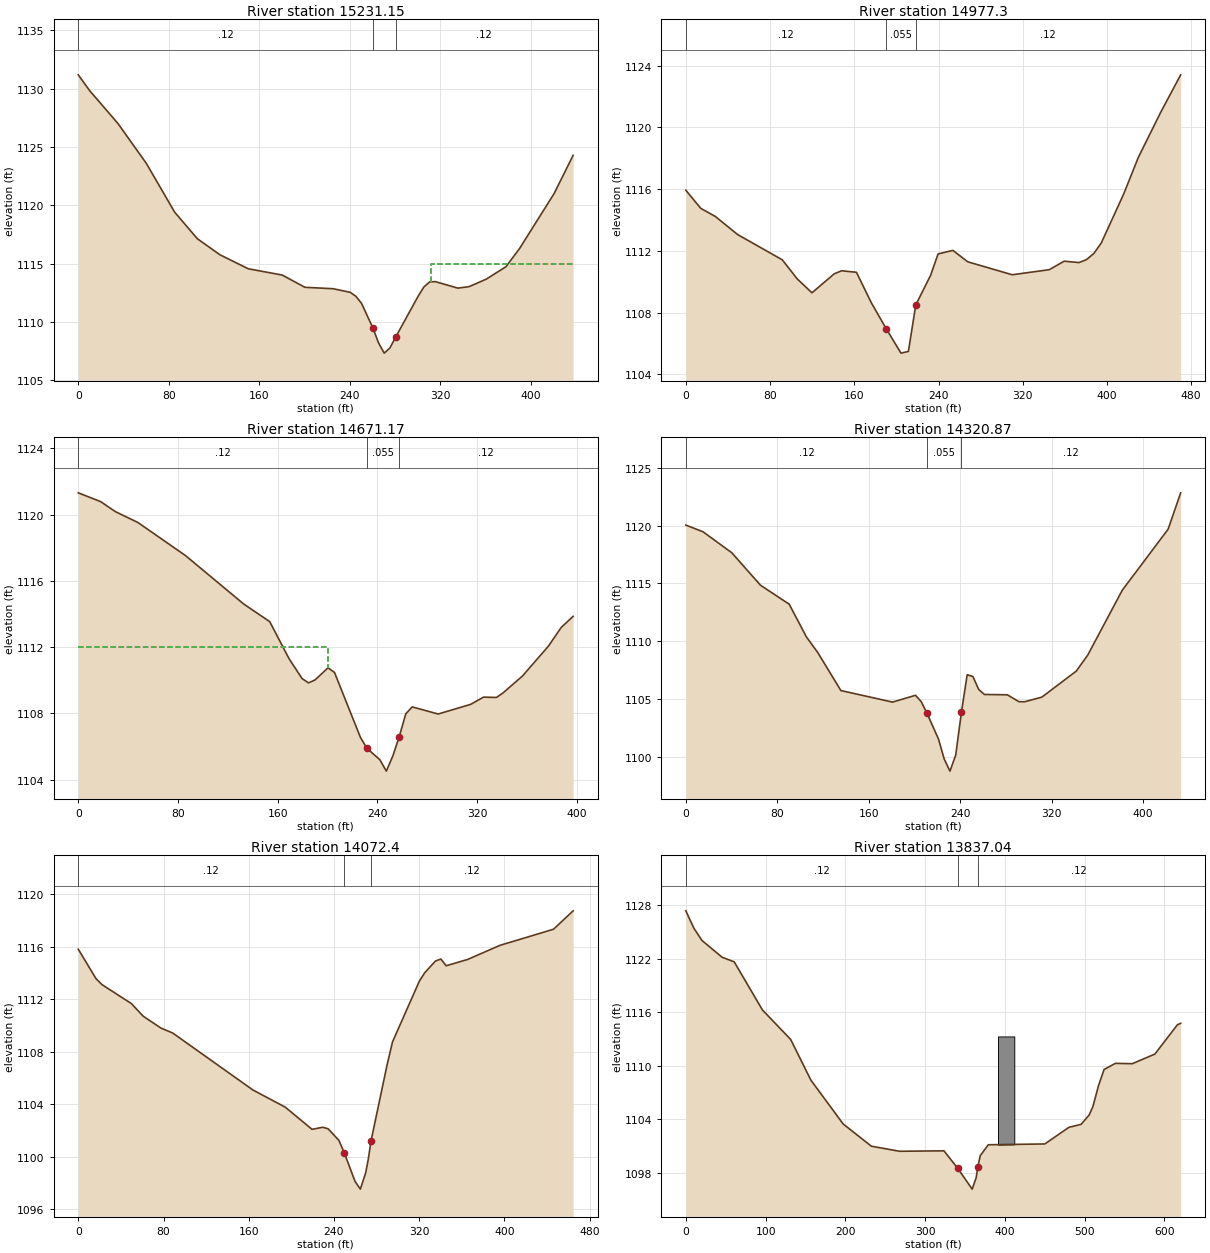
Type RM Length L Ch R = 1 ,15231.15,275.66,253.85,230.9
XS GIS Cut Line= 3
  1354191.641173   791804.644926  1353814.298788   791826.555128
   1353765.60943   791860.637669
#Sta/Elev= 30
       0 1131.19   10.02 1129.84   35.06 1127.02    60.1 1123.61   85.14 1119.43
  105.18 1117.15  125.21 1115.77  150.25 1114.57   180.3 1114.03  200.34 1112.98
  225.38 1112.86   240.4 1112.55  245.41 1112.21  250.42  1111.6  260.44 1109.49
  265.45 1108.21  270.44 1107.34  275.46 1107.78  280.47  1108.7  300.51 1112.23
  305.51 1113.01  310.52 1113.44  315.53 1113.47  335.56 1112.91  345.58 1113.04
  360.61 1113.68  377.98 1114.74  390.18 1116.32   420.7 1121.03  437.41 1124.29
#Mann= 3 , 0 , 0
       0     .12       0  260.44    .055       0  280.47     .12       0
#XS Ineff= 2 , 0
                          311.35         1114.99
Permanent Ineff=
       F       F
Bank Sta=260.44,280.47
Exp/Cntr=0.3,0.1

Type RM Length L Ch R = 1 ,14977.3 ,319.83,306.13,288
XS GIS Cut Line= 2
  1353987.145925   791439.474881  1353656.058421   791772.996815
#Sta/Elev= 30
       0 1115.93   14.09 1114.76   28.19 1114.22   49.33 1113.05    91.6 1111.42
  105.69 1110.19  119.78 1109.28  140.92 1110.51  147.96 1110.71  162.04 1110.61
  176.13 1108.64  190.23 1106.96  204.31 1105.37  211.37 1105.48  218.41  1108.5
  232.51 1110.42  239.55  1111.8  253.64 1112.03  267.73 1111.29     310 1110.45
  345.23 1110.78  359.32 1111.33  373.41 1111.24  380.46 1111.43   387.5 1111.83
  394.55 1112.51  415.68 1115.66  429.77 1118.06  450.91 1120.97  469.96 1123.41
#Mann= 3 , 0 , 0
       0     .12       0  190.23    .055       0  218.41     .12       0
Bank Sta=190.23,218.41
Exp/Cntr=0.3,0.1

Type RM Length L Ch R = 1 ,14671.17,310.96,350.3,385.66
XS GIS Cut Line= 3
  1353724.223503   791256.889835  1353660.927375   791298.275761
  1353573.286522   791607.453063
#Sta/Elev= 30
       0 1121.32   17.92 1120.79   29.87 1120.18   47.79 1119.53   86.02 1117.53
  132.78  1114.6  153.58 1113.54  169.17 1111.29  179.56  1110.1  184.76 1109.84
  189.96 1110.02  200.34 1110.75  205.55 1110.47  226.34 1106.55  231.53 1105.89
  241.93  1105.2  247.13 1104.51  252.32 1105.42  257.52  1106.6  262.72 1107.97
   267.9 1108.39   288.7 1107.96  314.69 1108.54  325.08 1108.98  335.47 1108.96
  340.67 1109.23  356.26 1110.25  377.05 1112.05  387.44 1113.19  396.97 1113.86
#Mann= 3 , 0 , 0
       0     .12       0  231.53    .055       0  257.52     .12       0
#XS Ineff= 2 , 0
             200 1112.01
Permanent Ineff=
       F       F
Bank Sta=231.53,257.52
Exp/Cntr=0.3,0.1

Type RM Length L Ch R = 1 ,14320.87,249.02,248.47,246.84
XS GIS Cut Line= 2
  1353690.140962   791215.503908  1353259.240311   791256.889835
#Sta/Elev= 30
       0 1120.04   15.07 1119.46   40.18 1117.65    65.3 1114.84   90.41  1113.2
  105.48 1110.37  115.53    1109  135.62 1105.73  180.83 1104.73  200.92 1105.32
  205.94 1104.77  210.97 1103.76  221.01 1101.54  226.05  1099.8  231.06 1098.76
  236.08 1100.14   241.1 1103.86  246.13  1107.1  251.15 1106.94  256.17 1105.83
   261.2 1105.39  281.29 1105.36  291.33 1104.77  296.36 1104.76  311.44 1105.16
  341.56 1107.41  351.61  1108.8  381.75  1114.4  421.93 1119.69  432.88 1122.83
#Mann= 3 , 0 , 0
       0     .12       0  210.97    .055       0   241.1     .12       0
Bank Sta=210.97,241.1
Exp/Cntr=0.3,0.1

Type RM Length L Ch R = 1 ,14072.4 ,235.99,235.36,234.34
XS GIS Cut Line= 3
  1353751.002613    791035.35334  1353643.886081   790984.229551
  1353300.626238   791025.615477
#Sta/Elev= 30
       0  1115.8   16.62 1113.56   22.16 1113.11   49.85 1111.66   60.93  1110.7
   77.55  1109.8   88.63 1109.42  164.02 1105.08  194.23 1103.78  219.42 1102.09
  229.48 1102.25  234.52 1102.13   244.6 1101.25  249.62 1100.31  259.71 1098.14
  264.73 1097.54  269.77 1098.79  272.14  1099.8  274.81 1101.23  289.92 1107.03
  294.95 1108.75  320.13 1113.37  325.18 1114.01  335.24  1114.9  340.28 1115.05
  345.31 1114.54  365.47 1115.02  395.67 1116.09  446.04 1117.32  464.43 1118.72
#Mann= 3 , 0 , 0
       0     .12       0  249.62    .055       0  274.81     .12       0
Bank Sta=249.62,274.81
Exp/Cntr=0.3,0.1

Type RM Length L Ch R = 1 ,13837.04,511.75,501.2,490.44
XS GIS Cut Line= 3
  1353857.952438   790715.774189  1353353.385988   790791.967086
  1353275.499853   790869.853173
#Sta/Elev= 30
       0 1127.39    10.1 1125.44   20.23 1124.06   45.51 1122.18   60.68 1121.66
   96.08 1116.26  131.46 1112.95  156.76 1108.39  197.21 1103.47  232.61 1100.97
  268.01  1100.4  323.63 1100.45  340.96 1098.48  359.03 1096.15  364.08 1097.45
  366.14 1098.67  369.14 1099.91  379.25 1101.13  450.06 1101.22   480.4 1103.09
  495.57 1103.42  505.67 1104.47  510.28 1105.38  517.36 1107.75  524.43 1109.58
  538.58 1110.27  559.78 1110.23  588.07 1111.31  616.36  1114.6  620.43 1114.76
#Mann= 3 , 0 , 0
       0     .12       0  340.96    .055       0  366.14     .12       0
#Block Obstruct= 1 ,-1
  391.35  411.81 1113.29
Bank Sta=340.96,366.14
Exp/Cntr=0.3,0.1

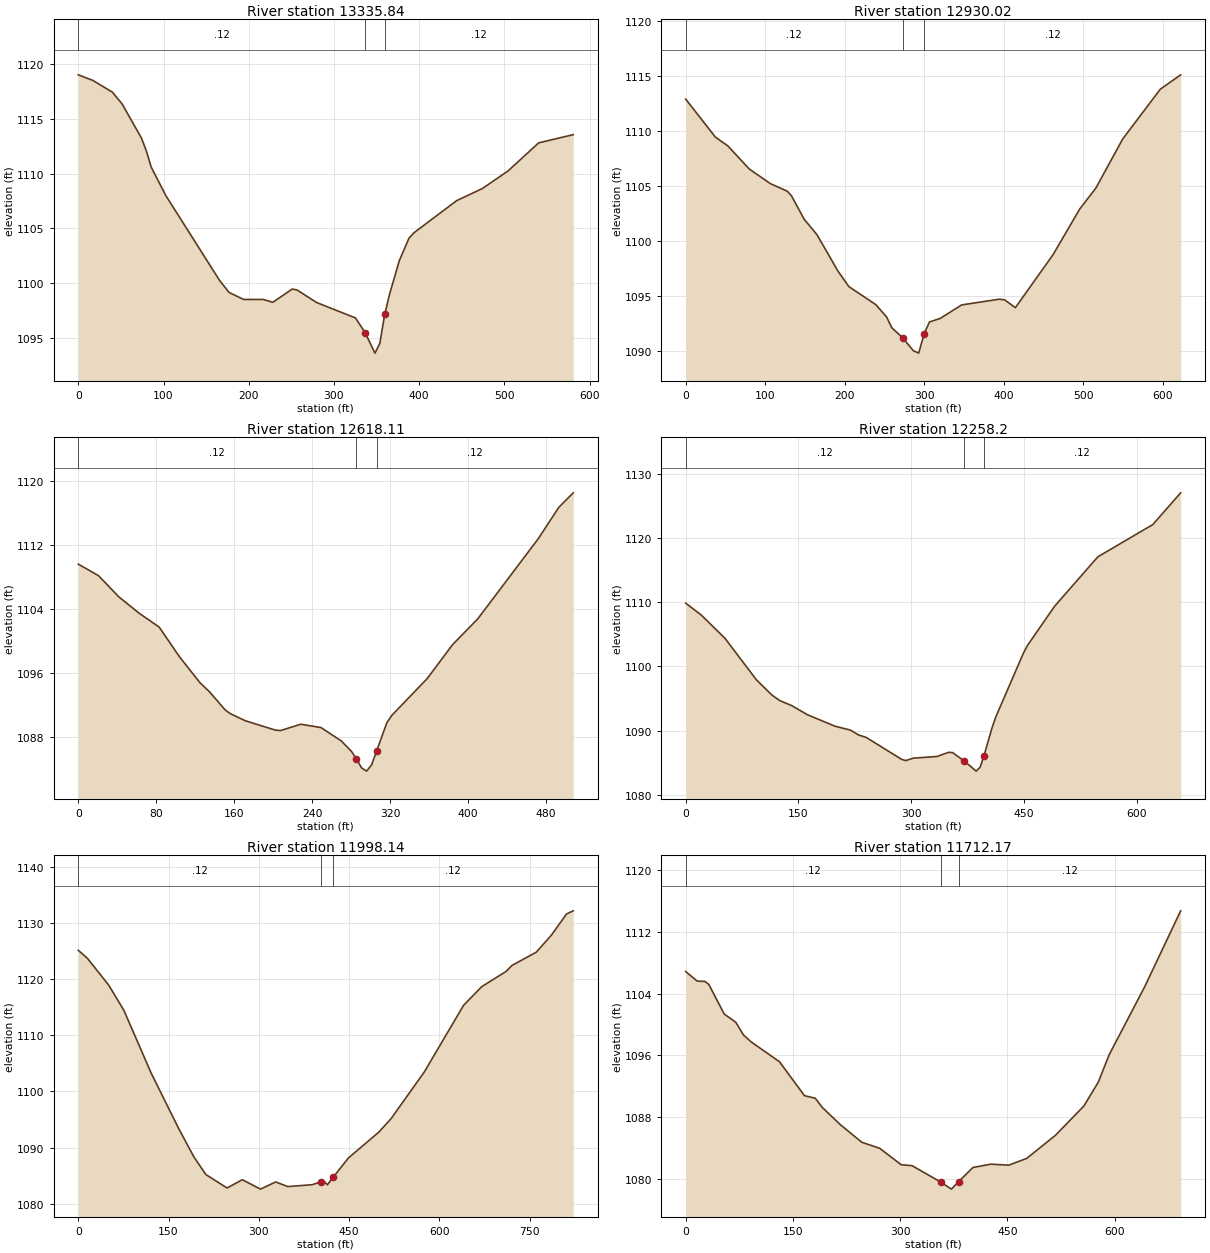
Type RM Length L Ch R = 1 ,13335.84,412.83,405.82,398.42
XS GIS Cut Line= 3
  1353646.320559   790144.338405   1353283.58499   790343.964698
  1353191.075229    790482.72934
#Sta/Elev= 30
       0 1119.02   17.12 1118.51   39.95 1117.44   51.36 1116.37   74.19 1113.24
    79.9 1112.07   85.61 1110.59  102.73    1108  165.51 1100.29  176.92 1099.16
  194.04 1098.52  216.87 1098.52  228.29 1098.26  251.12 1099.47  256.82 1099.38
  279.65 1098.24  325.31 1096.83  336.72 1095.47  348.14 1093.62  353.84  1094.5
  359.55 1097.15  365.26 1098.99  376.67 1102.05  388.09 1104.11  393.79  1104.6
  444.08 1107.54  474.14 1108.64  504.19 1110.24  540.23 1112.81  580.81 1113.56
#Mann= 3 , 0 , 0
       0     .12       0  336.72    .055       0  359.55     .12       0
Bank Sta=336.72,359.55
Exp/Cntr=0.3,0.1

Type RM Length L Ch R = 1 ,12930.02,282.57,311.91,341.47
XS GIS Cut Line= 3
  1353334.708779   789874.112598   1353154.55821   789939.843204
  1352835.643046   790229.544781
#Sta/Elev= 30
       0 1112.91   37.26 1109.47   53.22 1108.65   79.84 1106.57  106.45 1105.24
  127.74 1104.55  133.06 1104.13  149.03    1102  165.01 1100.61  191.77 1097.26
  205.28 1095.88  239.06 1094.25  252.56 1093.14  259.32 1092.14  272.83 1091.24
  286.34 1090.06  293.09 1089.84  299.85 1091.58  306.61 1092.67  320.11 1092.99
  347.13 1094.22  394.42 1094.74  401.17 1094.68  414.68 1093.97  461.97 1098.77
  495.74 1102.94  516.01 1104.84  549.78  1109.3  597.07 1113.82  622.62 1115.12
#Mann= 3 , 0 , 0
       0     .12       0  272.83    .055       0  299.85     .12       0
Bank Sta=272.83,299.85
Exp/Cntr=0.3,0.1

Type RM Length L Ch R = 1 ,12618.11,357.41,359.91,360.76
XS GIS Cut Line= 2
  1353266.543697    789825.42324  1352777.215826   789689.093075
#Sta/Elev= 30
       0 1109.59   20.75 1108.15   41.51 1105.52   62.28 1103.48   83.05 1101.73
  103.81 1098.04  124.57 1094.84  134.95 1093.63  150.52 1091.43   155.7 1090.96
  171.27 1090.06  202.43 1088.88  207.62 1088.83  228.38 1089.62  249.14  1089.2
   269.9 1087.54  280.28 1086.24  285.47 1085.29  290.65 1084.19  295.84 1083.77
  301.03 1084.55  306.24  1086.3  316.61 1089.79  321.81 1090.73  358.14 1095.32
  384.09 1099.54  410.04 1102.77  472.33  1112.8  493.09 1116.66  507.96 1118.48
#Mann= 3 , 0 , 0
       0     .12       0  285.47    .055       0  306.24     .12       0
Bank Sta=285.47,306.24
Exp/Cntr=0.3,0.1

Type RM Length L Ch R = 1 ,12258.2 ,264.66,260.06,254.5
XS GIS Cut Line= 2
   1353466.16999   789543.025094  1352835.643046   789353.136663
#Sta/Elev= 30
       0 1109.83   20.89 1107.96   52.22 1104.36   93.99 1097.91  114.88 1095.51
  125.32 1094.66  140.99 1093.89  161.88 1092.47  198.43 1090.69  219.32 1090.07
  229.76 1089.33   240.2 1088.93   287.2 1085.53  292.42 1085.33  302.87 1085.71
   334.2 1085.97  349.86 1086.62  355.09 1086.57  370.75 1085.25  386.42 1083.69
  391.64 1084.29  396.86 1086.09   407.3 1090.34  412.52 1092.11  449.08    1102
   454.3 1103.18  490.85 1109.36  548.29 1117.04   621.4 1122.06   658.5    1127
#Mann= 3 , 0 , 0
       0     .12       0  370.75    .055       0  396.86     .12       0
Bank Sta=370.75,396.86
Exp/Cntr=0.3,0.1

Type RM Length L Ch R = 1 ,11998.14,290.71,285.97,279.45
XS GIS Cut Line= 3
   1353572.46286   789240.689194   1353162.42593   789183.512088
   1352756.33548   789137.732042
#Sta/Elev= 30
       0 1125.13   15.14 1123.71   50.47 1118.94   75.73 1114.45  121.16 1103.25
   166.6 1093.44  191.84 1088.38  212.02 1085.19  247.37 1082.79   272.6 1084.27
  302.89 1082.59  328.13 1083.87  348.34 1083.04  388.73 1083.38  403.87  1083.9
  408.92 1083.94     414 1083.36  424.06 1084.77  449.23 1088.16  499.54 1092.75
  519.66 1095.11  575.01 1103.44  640.42 1115.33  670.61 1118.66  710.87 1121.35
  720.94 1122.44  761.18 1124.79  786.34 1127.82   811.5  1131.6  822.66 1132.16
#Mann= 3 , 0 , 0
       0     .12       0  403.87    .055       0  424.06     .12       0
Bank Sta=403.87,424.06
Exp/Cntr=0.3,0.1

Type RM Length L Ch R = 1 ,11712.17,312.65,308.52,302.28
XS GIS Cut Line= 3
   1353621.97588   788961.187462  1353500.252531   788912.498104
  1352940.325147   788951.449599
#Sta/Elev= 30
       0 1106.84   16.16  1105.6   26.94 1105.57   32.31 1105.18   53.85 1101.35
   70.02 1100.28   80.79 1098.64   91.56 1097.74  131.11 1095.18  166.18 1090.78
  181.23 1090.45  191.25 1089.24  216.31 1087.03  246.38 1084.75  271.45 1083.97
  301.52 1081.84  316.55 1081.73  356.64 1079.61  371.69 1078.69   381.7 1079.65
  401.76 1081.49  426.81 1081.92  451.87 1081.79  476.93 1082.66  517.04 1085.64
  557.13 1089.46  577.18 1092.54  592.22 1096.05  642.34 1104.93  692.38  1114.7
#Mann= 3 , 0 , 0
       0     .12       0  356.64    .055       0   381.7     .12       0
Bank Sta=356.64,381.7
Exp/Cntr=0.3,0.1

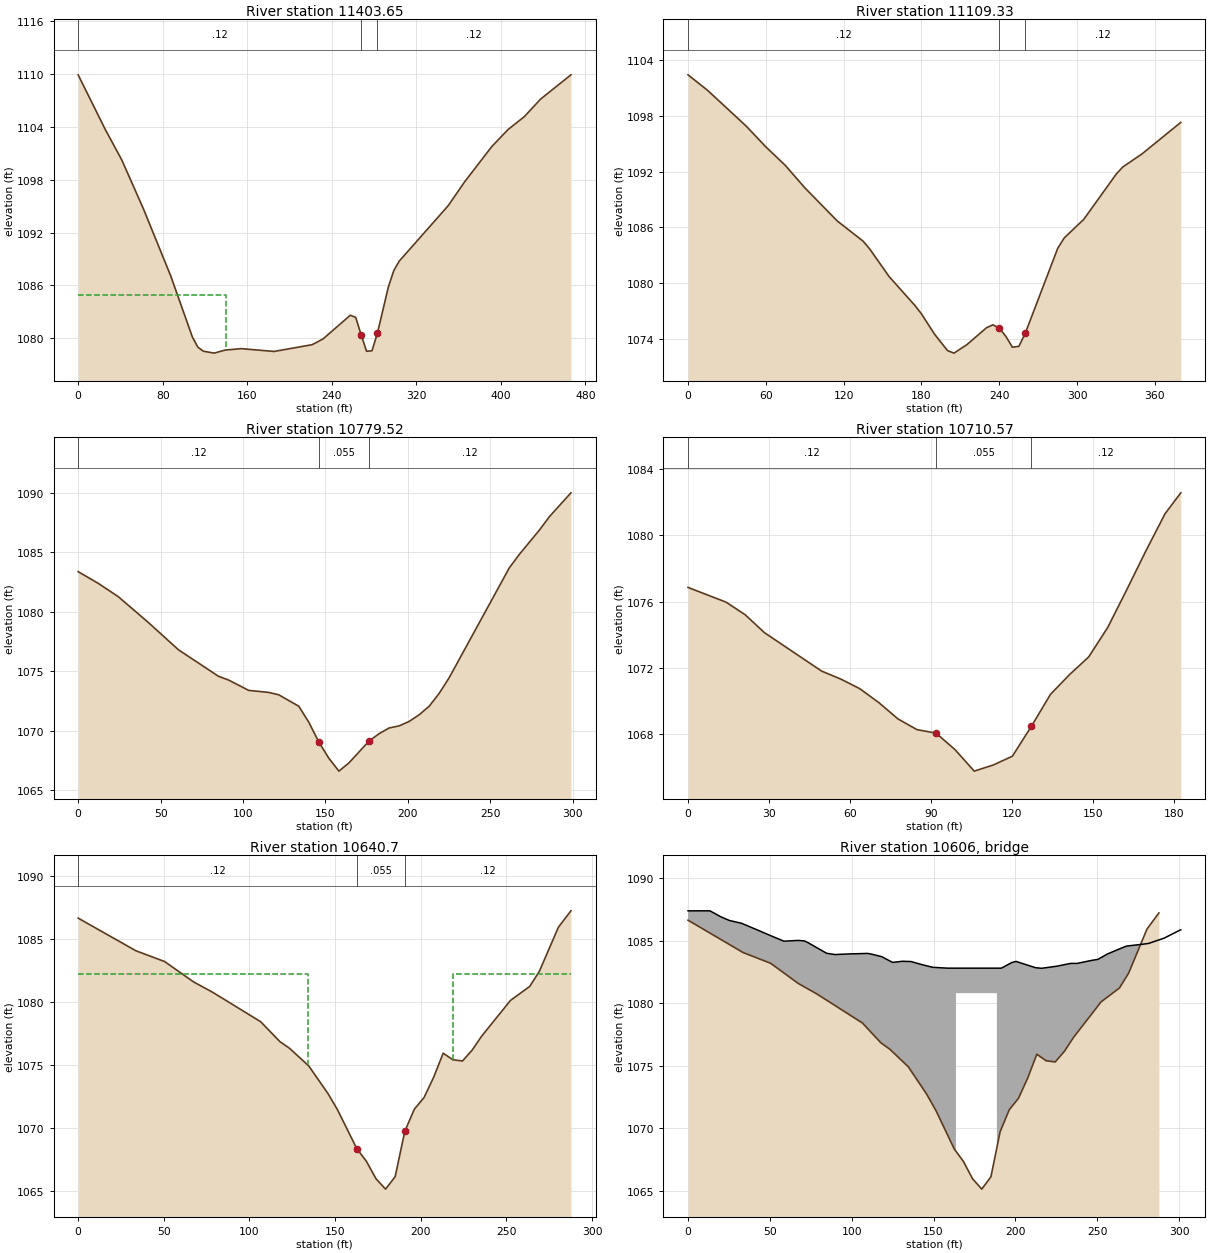
Type RM Length L Ch R = 1 ,11403.65,287.32,294.32,300.26
XS GIS Cut Line= 2
  1353500.252531   788583.845077  1353047.441679   788695.830563
#Sta/Elev= 30
       0 1109.92   25.74  1103.7    41.2 1100.28   61.81 1094.69   87.56  1087.1
  108.15 1080.13   113.3 1078.99  118.45 1078.53  128.77 1078.31  139.07 1078.66
  154.52 1078.82  185.42  1078.5  221.48 1079.27  231.78 1079.92  257.53 1082.61
  262.68 1082.38  267.83 1080.41  272.98 1078.52  278.12 1078.58  283.28 1080.58
  293.59 1085.81  298.74 1087.68  303.89 1088.76  350.24 1095.06  365.69 1097.75
  391.45 1101.77   406.9 1103.71  422.35 1105.18   437.8 1107.18  466.45 1109.93
#Mann= 3 , 0 , 0
       0     .12       0  267.83    .055       0  283.28     .12       0
#XS Ineff= 2 , 0
          140.22 1084.96
Permanent Ineff=
       F       F
Bank Sta=267.83,283.28
Exp/Cntr=0.3,0.1

Type RM Length L Ch R = 1 ,11109.33,357.77,329.81,299.94
XS GIS Cut Line= 2
  1353410.177247   788374.480921  1353030.400385   788384.218783
#Sta/Elev= 30
       0 1102.41   15.01 1100.75   45.01 1096.87   60.02 1094.65   75.02 1092.66
   90.03 1090.25  115.05 1086.68  135.04  1084.5  140.06 1083.67  155.05 1080.69
  175.07 1077.56  180.06 1076.66  190.06 1074.49  200.08 1072.72  205.08 1072.45
  215.07 1073.37  230.09 1075.18  235.09  1075.5  240.08 1075.12  245.08 1074.25
  250.08 1073.09  255.08 1073.18   260.1 1074.62  285.09 1083.75  290.11 1084.86
   305.1 1086.85  330.12 1091.72  335.11 1092.48  350.13 1093.91   379.9 1097.29
#Mann= 3 , 0 , 0
       0     .12       0  240.08    .055       0   260.1     .12       0
Bank Sta=240.08,260.1
Exp/Cntr=0.3,0.1

Type RM Length L Ch R = 1 ,10779.52,68.59,68.95,74.21
XS GIS Cut Line= 2
  1353181.337367   787983.202458  1353011.073718   788228.884888
#Sta/Elev= 30
       0 1083.36   12.17 1082.38   24.33 1081.26   42.59 1079.09   60.83  1076.8
   85.18 1074.57   91.25 1074.26  103.43 1073.39  115.59 1073.22  121.68 1073.02
  133.83 1072.06  139.93 1070.71     146 1069.05  152.08 1067.69  158.18 1066.61
  164.25  1067.3  176.43 1069.13   182.5 1069.75  188.58 1070.23  194.68 1070.41
  200.75 1070.78  206.84 1071.34  212.93 1072.06     219 1073.14  225.08 1074.46
  261.58 1083.69  267.68 1084.82  279.84 1086.86  285.93 1087.99  298.92 1089.98
#Mann= 3 , 0 , 0
       0     .12       0     146    .055       0  176.43     .12       0
Bank Sta=146,176.43
Exp/Cntr=0.3,0.1

Type RM Length L Ch R = 1 ,10710.57,55.11,69.87,78.37
XS GIS Cut Line= 2
  1353118.488366   787992.344134  1352989.362261    788121.47024
#Sta/Elev= 24
       0 1076.86   14.14 1075.97   21.21 1075.21   28.28 1074.14    49.5 1071.82
   56.58 1071.34   63.64 1070.76   70.71 1069.92   77.78 1068.94   84.85 1068.29
   91.92 1068.08   98.99 1067.08  106.08 1065.79  113.14 1066.16  120.22 1066.69
  127.29  1068.5  134.35 1070.42  141.42 1071.61  148.49 1072.67  155.56 1074.45
  162.63 1076.73  169.72 1079.07  176.79  1081.3  182.62 1082.56
#Mann= 3 , 0 , 0
       0     .12       0   91.92    .055       0  127.29     .12       0
Bank Sta=91.92,127.29
Exp/Cntr=0.5,0.3

Type RM Length L Ch R = 1 ,10640.7 ,69.33,69.92,70.73
XS GIS Cut Line= 2
  1353202.751406    787919.43089  1352946.263632   788049.763431
#Sta/Elev= 30
       0 1086.65   33.65 1084.06   50.48  1083.2    67.3 1081.59   78.52 1080.76
  106.56 1078.42  117.78 1076.84  123.39 1076.31  134.61 1074.91  145.82 1072.72
  151.43 1071.42  162.65 1068.34  168.25 1067.34  173.86 1065.95  179.47 1065.12
  185.08 1066.11  190.69 1069.71   196.3 1071.48  201.91 1072.39  207.52    1074
  213.12 1075.92  218.73  1075.4  224.34  1075.3  229.95 1076.15  235.56 1077.27
  252.38 1080.11   263.6 1081.22  269.21 1082.41  280.43 1085.94   287.7 1087.23
#Mann= 3 , 0 , 0
       0     .12       0  162.65    .055       0  190.69     .12       0
#XS Ineff= 2 , 0
       0     134 1082.25     219       0 1082.25
Permanent Ineff=
       F       F
Bank Sta=162.65,190.69
Exp/Cntr=0.5,0.3

Type RM Length L Ch R = 3 ,10606   ,,,
BEGIN DESCRIPTION:
37003-0048 Bridge X-ing (SR # 1111)
END DESCRIPTION:
Bridge Culvert--1,0,-1,-1, 0
Deck Dist Width WeirC Skew NumUp NumDn MinLoCord MaxHiCord MaxSubmerge Is_Ogee
30,20,2.6,0, 52, 52, , , 0.95, 0, 0,0,,
       0   13.37   19.95   25.25   32.77   43.05   45.69   52.71   58.59   67.36
   71.14   73.62   84.71   89.85   98.64   109.9  112.51  118.35  124.98  130.85
  136.29  142.45  149.42  158.69  163.71  167.62  173.61  178.39  179.71  180.43
  185.71  186.55  188.71  191.41  197.84  200.44  203.23  212.28  216.01  225.05
  233.81  237.68  247.35  250.37  256.18  263.94  267.97  277.44  281.38  290.86
  300.19  301.07
  1087.4  1087.4 1086.93 1086.63  1086.4 1085.83 1085.68 1085.29 1084.97 1085.03
 1084.99 1084.83    1084  1083.9 1083.95 1083.99 1083.92 1083.73 1083.27 1083.36
 1083.34 1083.11 1082.88 1082.81 1082.81 1082.81 1082.81 1082.81 1082.81 1082.81
 1082.81 1082.81 1082.81 1082.81 1083.26 1083.35 1083.23 1082.85  1082.8 1082.96
 1083.19 1083.19 1083.45 1083.51 1083.94 1084.37 1084.58 1084.72 1084.79 1085.21
 1085.83 1085.88
                                                                                
                                                                                
                                 1080.81 1080.81 1080.81 1080.81 1080.81 1080.81
 1080.81 1080.81 1080.81
                                                                                
                
  -14.83   -8.25   -2.95    4.57   14.85   17.49   24.51   30.39   39.16   42.94
   45.42   56.51   61.65   70.44    81.7   84.31   90.15   96.78  102.65  108.09
  114.25  121.22  130.49  135.31  139.42  145.41  150.19  151.51  152.23  157.51
  158.35  160.51  163.21  169.64  172.24  175.03  184.08  187.81  196.85  205.61
  209.48  219.15  222.17  227.98  235.74  239.77  249.24  253.18  262.66  271.99
  272.87     300
  1087.4 1086.93 1086.63  1086.4 1085.83 1085.68 1085.29 1084.97 1085.03 1084.99
 1084.83    1084  1083.9 1083.95 1083.99 1083.92 1083.73 1083.27 1083.36 1083.34
 1083.11 1082.88 1082.81 1082.81 1082.81 1082.81 1082.81 1082.81 1082.81 1082.81
 1082.81 1082.81 1082.81 1083.26 1083.35 1083.23 1082.85  1082.8 1082.96 1083.19
 1083.19 1083.45 1083.51 1083.94 1084.37 1084.58 1084.72 1084.79 1085.21 1085.83
 1085.88 1085.88
                                                                                
                                                                                
                         1080.81 1080.81 1080.81 1080.81 1080.81 1080.81 1080.81
 1080.81 1080.81
                                                                                
                
BR Coef=-1 , 1 , 0 ,, 0 ,,,0.8,0,1.2,0,
WSPro=,,,, 1 ,,,, 0 ,,,, 0 ,,,,-1 ,-1 ,-1 , 0 , 0 , 0 , 0 , 0
BC Design=,, 0 ,, 0 ,,,,,,