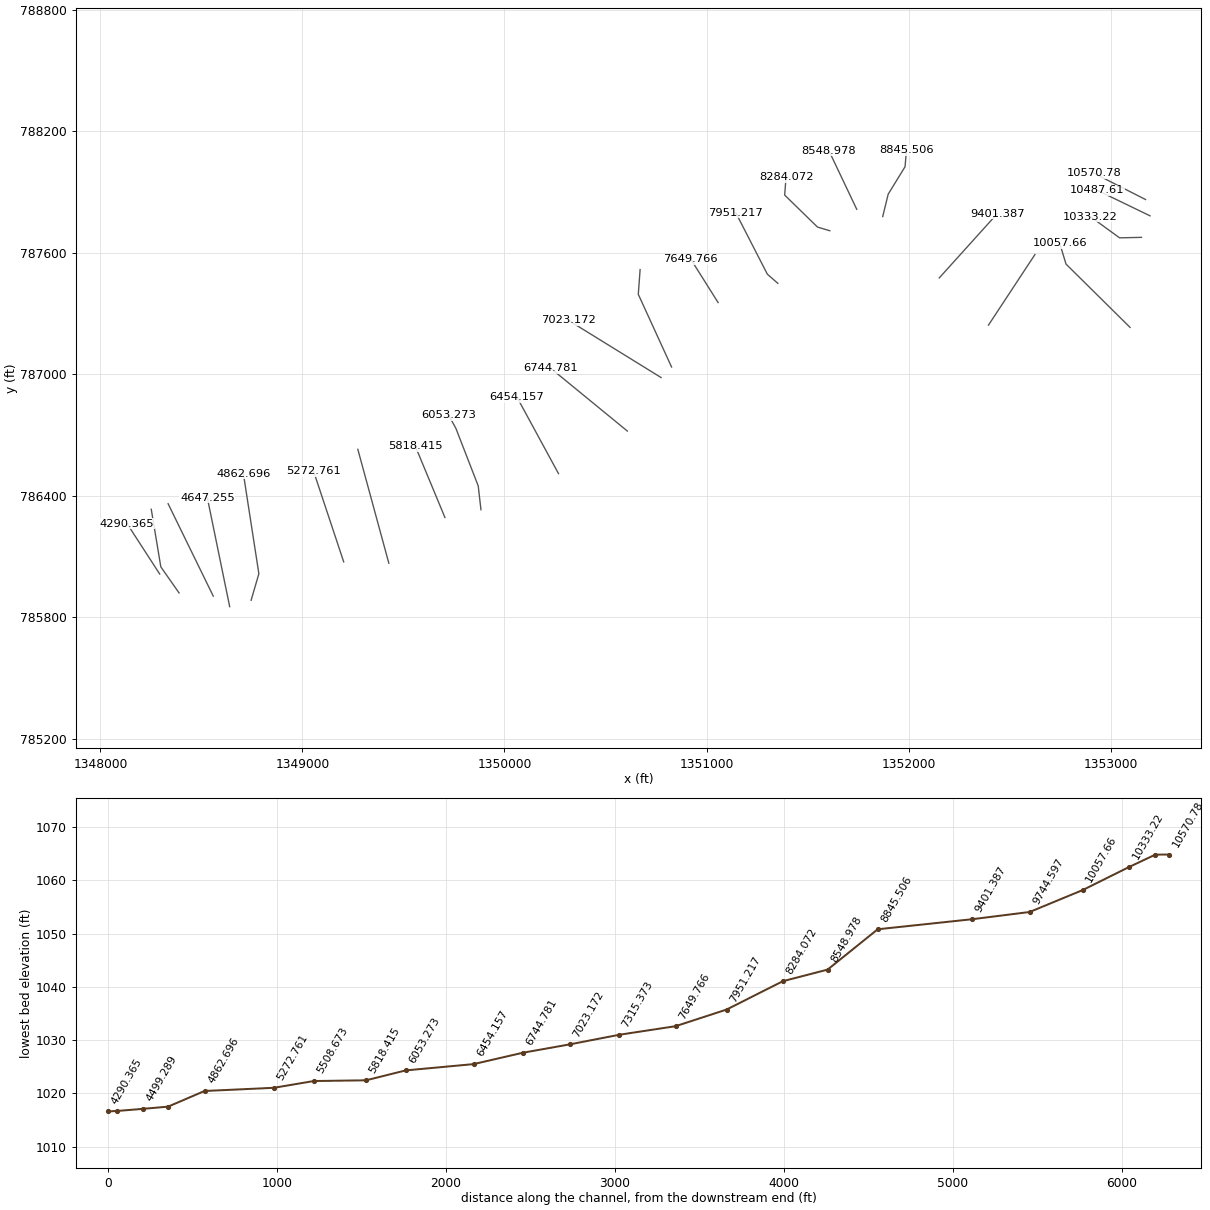
HEC-RAS study StirewaitCr.prj: StirewaitCr

--- StirewaitCr.g01 (geometry) --- (continued)

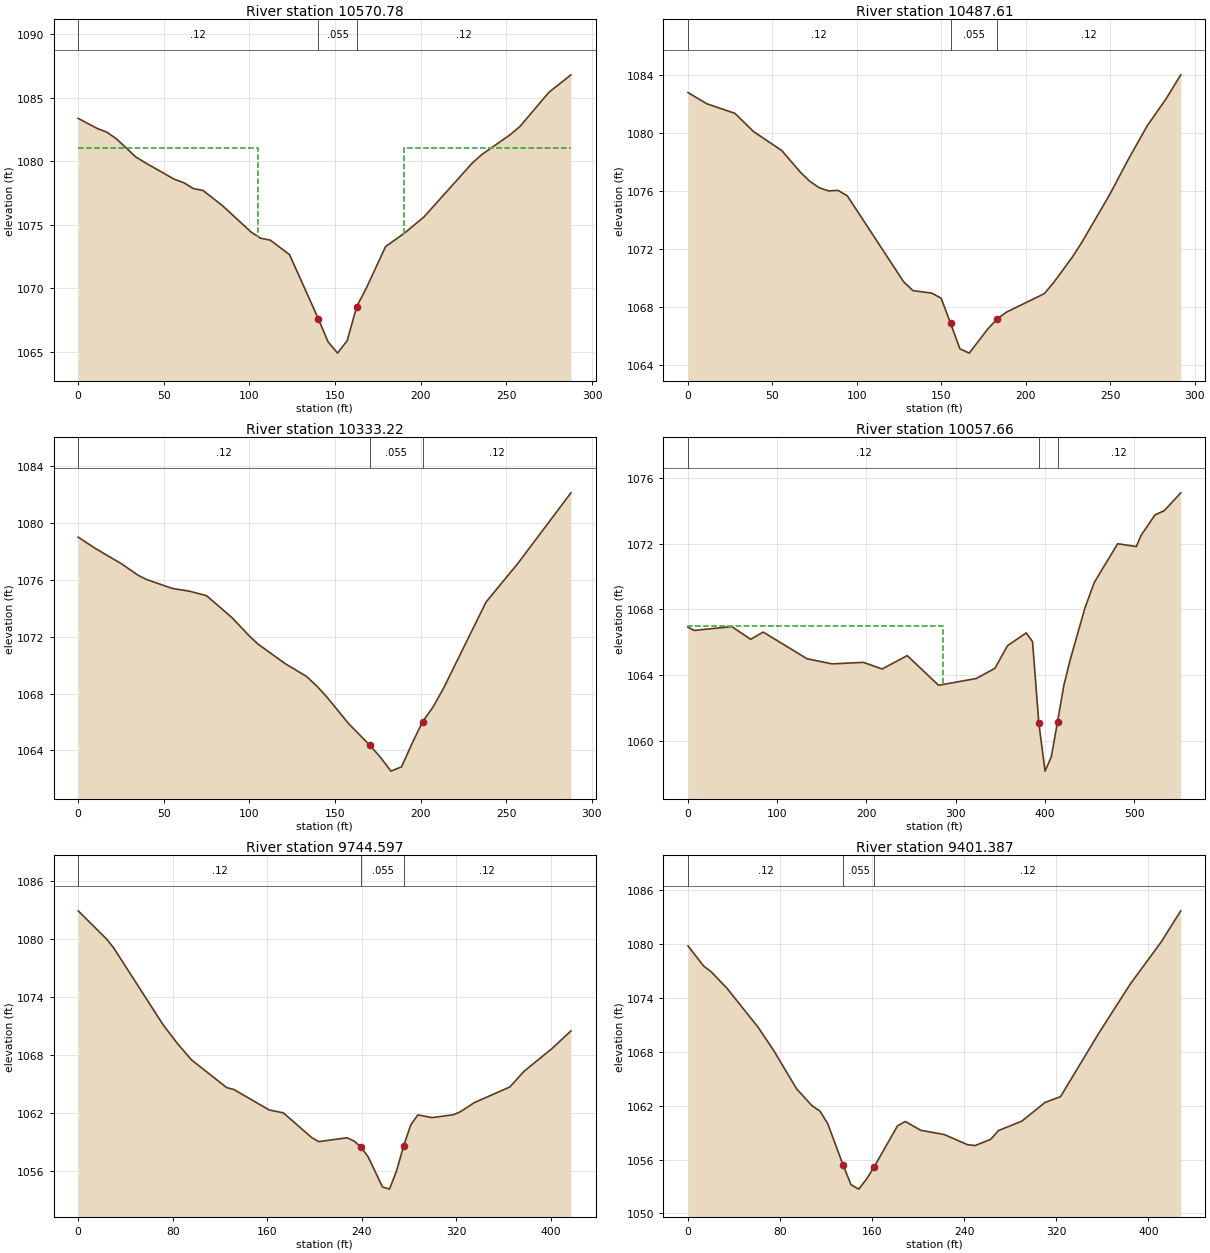
Type RM Length L Ch R = 1 ,10570.78,81.66,83.17,82.74
XS GIS Cut Line= 2
   1353172.67467   787862.619281  1352916.186896   787992.951822
#Sta/Elev= 30
       0 1083.37   11.22 1082.57   16.82 1082.28   22.42 1081.75   33.64 1080.33
   39.26 1079.87   56.07 1078.58   61.69  1078.3   67.29 1077.84   72.91 1077.69
   84.13 1076.51  100.94 1074.42  106.55 1073.93  112.17 1073.78  123.39 1072.64
   140.2 1067.59  145.82 1065.79  151.43 1064.88  157.04 1065.86  162.65 1068.55
  168.25 1070.01  179.46 1073.27  190.69 1074.35  201.91 1075.61  229.95 1079.83
  235.56 1080.51  252.37  1082.1  257.99 1082.74  274.82 1085.42  287.69  1086.8
#Mann= 3 , 0 , 0
       0     .12       0   140.2    .055       0  162.65     .12       0
#XS Ineff= 2 , 0
       0     105    1081     190       0    1081
Permanent Ineff=
       F       F
Bank Sta=140.2,162.65
Exp/Cntr=0.5,0.3

Type RM Length L Ch R = 1 ,10487.61,159.83,154.39,148.6
XS GIS Cut Line= 2
  1353195.049881   787782.085676  1352932.226785   787908.926363
#Sta/Elev= 30
       0 1082.78    11.1 1082.01   27.76 1081.35   38.86 1080.09   55.52 1078.79
   66.62 1077.29   72.17 1076.67   77.72 1076.23   83.27 1076.01   88.83 1076.05
   94.38 1075.67  127.69 1069.76  133.24 1069.15  144.35 1068.98   149.9 1068.63
  155.45 1066.92     161 1065.15  166.55 1064.85  177.66 1066.53  183.21 1067.22
  188.76 1067.68  210.97 1068.94  216.52  1069.7  227.62 1071.46  233.17 1072.46
  249.83 1075.78  260.93 1078.22  272.04 1080.51  283.14 1082.35  291.83    1084
#Mann= 3 , 0 , 0
       0     .12       0  155.45    .055       0  183.21     .12       0
Bank Sta=155.45,183.21
Exp/Cntr=0.3,0.1

Type RM Length L Ch R = 1 ,10333.22,279.46,275.56,270.81
XS GIS Cut Line= 3
  1353152.769652   787675.813714  1353044.212271   787673.528342
  1352899.088232   787778.657524
#Sta/Elev= 27
       0    1079      10 1078.21   25.02 1077.15   35.01 1076.32   40.01 1076.02
   55.01 1075.39   65.01  1075.2   75.02 1074.88   90.02 1073.32  100.02 1072.04
  105.02 1071.48  120.93  1070.1  133.28 1069.21  139.45 1068.52  145.63  1067.7
  157.97 1065.88  170.32 1064.36   176.5 1063.52  182.67 1062.54  188.84 1062.84
  195.02 1064.49  201.19 1066.03  207.37 1067.07  213.54 1068.41  238.24 1074.44
  256.76 1077.15  287.78 1082.12
#Mann= 3 , 0 , 0
       0     .12       0  170.32    .055       0  201.19     .12       0
Bank Sta=170.32,201.19
Exp/Cntr=0.3,0.1

Type RM Length L Ch R = 1 ,10057.66,353.76,313.06,270.58
XS GIS Cut Line= 3
  1353096.187661   787231.487397  1352779.264502   787543.946913
  1352748.018537   787646.612188
#Sta/Elev= 30
       0 1066.92    7.02 1066.73   49.15 1066.96   70.21 1066.19   84.25 1066.63
  133.41 1065.01  161.49  1064.7  196.59 1064.79  217.66 1064.39  245.75  1065.2
  280.86  1063.4  322.99 1063.81  344.04 1064.43  358.09  1065.8  379.15 1066.58
  386.18 1066.05   393.2 1061.13  400.22 1058.19  407.24 1059.06  414.26  1061.2
  421.28 1063.39  428.31 1064.93  445.04 1068.11   455.5 1069.65  481.64 1071.99
  502.54 1071.82  507.76 1072.49  523.45 1073.74  533.89    1074  552.37 1075.08
#Mann= 3 , 0 , 0
       0     .12       0   393.2    .055       0  414.26     .12       0
#XS Ineff= 2 , 0
          286.16 1067.02
Permanent Ineff=
       F       F
Bank Sta=393.2,414.26
Exp/Cntr=0.3,0.1

Type RM Length L Ch R = 1 ,9744.597,345.94,343.21,336.91
XS GIS Cut Line= 2
  1352395.385677    787242.64669  1352625.266589   787590.815814
#Sta/Elev= 30
       0 1082.91   23.96    1080   29.95 1079.09    71.9 1071.11   83.88 1069.19
   95.85 1067.48  125.82 1064.59   131.8  1064.4  161.77 1062.28  173.74 1061.98
  197.72 1059.42  203.71    1059  227.68  1059.4  233.67 1059.06  239.66 1058.41
  245.65  1057.4  257.63 1054.31  263.62 1054.08  269.62 1055.99  275.61 1058.58
   281.6 1060.73  287.59 1061.77  299.57 1061.49  317.55 1061.78  323.54 1062.09
  335.52 1063.05  365.48 1064.66  377.47 1066.28  401.43 1068.67  417.21 1070.47
#Mann= 3 , 0 , 0
       0     .12       0  239.66    .055       0  275.61     .12       0
Bank Sta=239.66,275.61
Exp/Cntr=0.3,0.1

Type RM Length L Ch R = 1 ,9401.387,544.04,555.88,543.6
XS GIS Cut Line= 2
  1352151.945313   787475.694565  1352439.136417   787793.171255
#Sta/Elev= 30
       0 1079.82   13.48 1077.59   20.23 1076.92   33.71 1075.12   60.68 1070.79
   74.16 1068.22   94.39 1063.88  107.88 1061.99  114.62 1061.41  121.36 1060.01
  134.84 1055.36  141.59 1053.21  148.33 1052.71  155.07 1053.82  161.81 1055.22
  182.04 1059.77  188.78 1060.25  202.27 1059.26  222.49  1058.8  242.71 1057.67
  249.46 1057.57  262.96 1058.26   269.7 1059.24  289.92 1060.28  310.14 1062.37
  323.63 1063.02  357.35 1070.19  384.31 1075.58  411.28  1080.3   428.1 1083.73
#Mann= 3 , 0 , 0
       0     .12       0  134.84    .055       0  161.81     .12       0
Bank Sta=134.84,161.81
Exp/Cntr=0.3,0.1

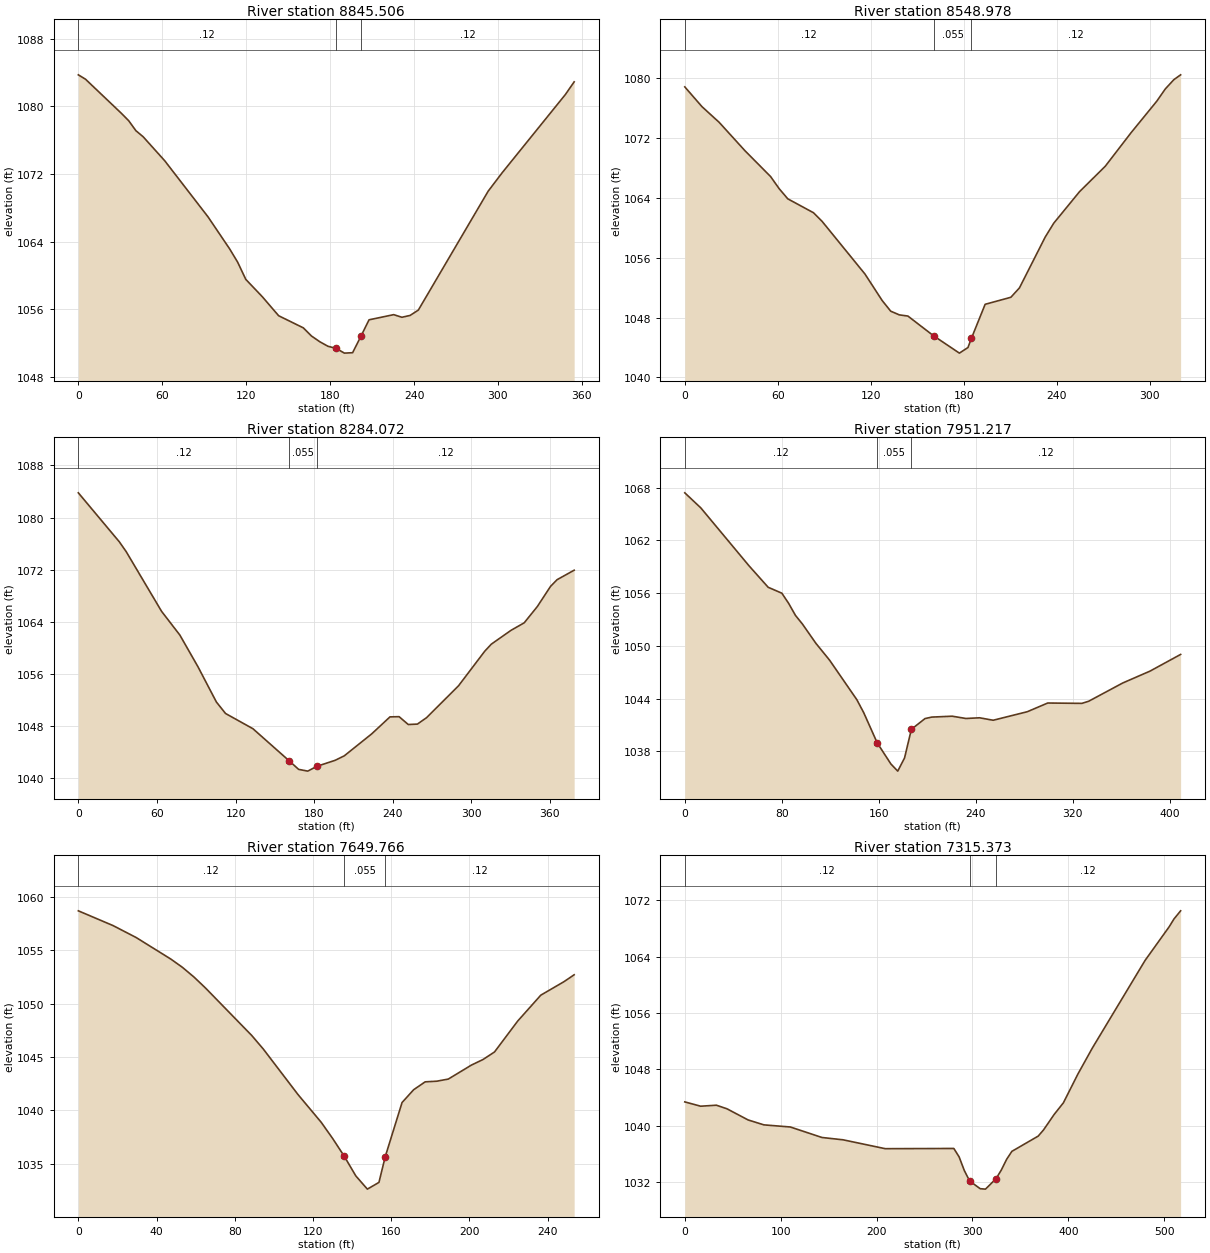
Type RM Length L Ch R = 1 ,8845.506,265.99,296.53,326.19
XS GIS Cut Line= 4
  1351872.002599   787778.462552  1351899.087834   787889.060507
  1351982.600554   788024.486591  1351989.371874    788105.74225
#Sta/Elev= 30
       0 1083.74    5.15 1083.22    30.9 1079.17   36.03 1078.31   41.18 1077.13
   46.33 1076.42   61.77 1073.58   92.66 1066.96   108.1 1063.18  113.87  1061.6
  119.74 1059.55  131.49 1057.51  143.24 1055.25  160.86 1053.82  166.74 1052.85
  172.61 1052.18  178.48 1051.64  184.36 1051.39  190.23 1050.83  196.11 1050.88
  201.98  1052.8  207.86 1054.77  225.48 1055.38  231.35 1055.07  237.23 1055.29
   243.1 1055.92  293.04 1069.98  303.08 1072.17  348.23 1081.41  354.51 1082.91
#Mann= 3 , 0 , 0
       0     .12       0  184.36    .055       0  201.98     .12       0
Bank Sta=184.36,201.98
Exp/Cntr=0.3,0.1

Type RM Length L Ch R = 1 ,8548.978,254.09,264.91,275.32
XS GIS Cut Line= 2
  1351743.347835   787814.576168  1351605.664645   788103.485144
#Sta/Elev= 30
       0 1078.81   11.08 1076.17   22.16 1074.08   38.76  1070.3   55.39 1066.83
   60.93 1065.21   66.47 1063.86   83.07    1062   88.62 1060.85  116.31 1053.81
  127.38 1050.28  132.93 1048.85  138.47 1048.36  144.01  1048.2  160.61 1045.56
  177.24 1043.25  182.78    1044  185.05 1045.25  193.86 1049.77  210.47 1050.71
     216 1051.96  232.63 1058.75  238.17 1060.61  254.77 1064.81   271.4 1068.21
  288.02 1072.68  304.62 1076.89  310.17 1078.54  315.71 1079.78  320.04 1080.42
#Mann= 3 , 0 , 0
       0     .12       0  160.61    .055       0  185.05     .12       0
Bank Sta=160.61,185.05
Exp/Cntr=0.3,0.1

Type RM Length L Ch R = 1 ,8284.072,335.65,332.86,321.16
XS GIS Cut Line= 4
  1351610.178858   787708.492426  1351549.237114   787726.549235
  1351386.725841    787884.54634  1351393.497162   787972.573274
#Sta/Elev= 30
       0  1083.8   31.29 1076.28    36.5 1074.78   63.56  1065.6   77.51 1061.96
   91.45 1057.05   105.4 1051.68  112.38 1049.92   133.3 1047.58  161.19 1042.61
  168.16 1041.34  175.15 1041.07  182.11 1041.81  196.06 1042.73  203.03 1043.42
  223.95 1046.79  237.91  1049.4  244.87 1049.43  251.85 1048.23  258.82 1048.29
  265.79 1049.27  290.22 1054.17  310.28 1059.49  315.29 1060.57  330.32 1062.69
  340.36 1063.84  350.39 1066.34  360.42 1069.42  365.44 1070.46   378.5 1071.92
#Mann= 3 , 0 , 0
       0     .12       0  161.19    .055       0  182.11     .12       0
Bank Sta=161.19,182.11
Exp/Cntr=0.3,0.1

Type RM Length L Ch R = 1 ,7951.217,298.71,301.45,303.85
XS GIS Cut Line= 3
  1351352.869332   787448.925793  1351300.955968   787494.067837
  1351145.216016    787796.51936
#Sta/Elev= 30
       0 1067.41   13.25 1065.69   53.01  1059.1   68.79 1056.66   80.04 1055.99
   85.67 1054.83   91.29 1053.46   96.92  1052.5  108.16 1050.28  119.42 1048.37
  141.91 1043.87  147.53 1042.41  158.78 1038.94  170.03 1036.55  175.65 1035.74
  181.27 1037.24   186.9  1040.5  198.15 1041.72  203.77 1041.89  220.65 1041.99
  231.89 1041.73  243.14 1041.81  254.39 1041.53  282.51  1042.5  299.38 1043.49
   327.5 1043.45  333.12 1043.69  361.24 1045.77  383.74 1047.12  408.99 1049.02
#Mann= 3 , 0 , 0
       0     .12       0  158.78    .055       0   186.9     .12       0
Bank Sta=158.78,186.9
Exp/Cntr=0.3,0.1

Type RM Length L Ch R = 1 ,7649.766,336.77,334.39,330.24
XS GIS Cut Line= 2
  1351057.189082   787354.127539  1350921.762999   787568.552176
#Sta/Elev= 29
       0 1058.69   17.74 1057.31   29.57 1056.19   47.31 1054.17   53.21  1053.4
   59.14 1052.49   65.05 1051.46   88.71 1047.01   94.62 1045.74  112.36 1041.48
  124.19 1038.89   130.1 1037.36  136.02  1035.7  141.93 1033.86  147.84 1032.62
  153.76 1033.25     157 1035.67  165.58 1040.73   171.5 1041.93  177.41 1042.67
  183.33 1042.73  189.24 1042.93  201.07 1044.24  206.98 1044.76  212.88 1045.47
  224.72 1048.36  236.55 1050.79  248.38 1052.05  253.61  1052.7
#Mann= 3 , 0 , 0
       0     .12       0  136.02    .055       0     157     .12       0
Bank Sta=136.02,157
Exp/Cntr=0.3,0.1

Type RM Length L Ch R = 1 ,7315.373,274.72,292.2,308.99
XS GIS Cut Line= 3
  1350826.964745   787035.876268  1350662.196365   787394.755369
  1350671.224746   787516.638812
#Sta/Elev= 30
       0 1043.38    16.5 1042.77   33.01 1042.91      44  1042.4   66.02 1040.82
   82.53 1040.12  110.04 1039.82  143.04 1038.33  165.04    1038  209.07 1036.74
  280.59 1036.77  286.08 1035.58  291.59 1033.62   297.1 1032.15   308.1 1031.06
   313.6    1031  324.61 1032.48  330.11 1033.71  335.61 1035.22  341.11 1036.36
  368.62 1038.53  374.12  1039.4  385.12 1041.58  394.89 1043.26  409.93 1047.32
  424.98 1051.01  480.13 1063.48  505.19 1068.24  510.21 1069.35  517.11  1070.5
#Mann= 3 , 0 , 0
       0     .12       0   297.1    .055       0  324.61     .12       0
Bank Sta=297.1,324.61
Exp/Cntr=0.3,0.1

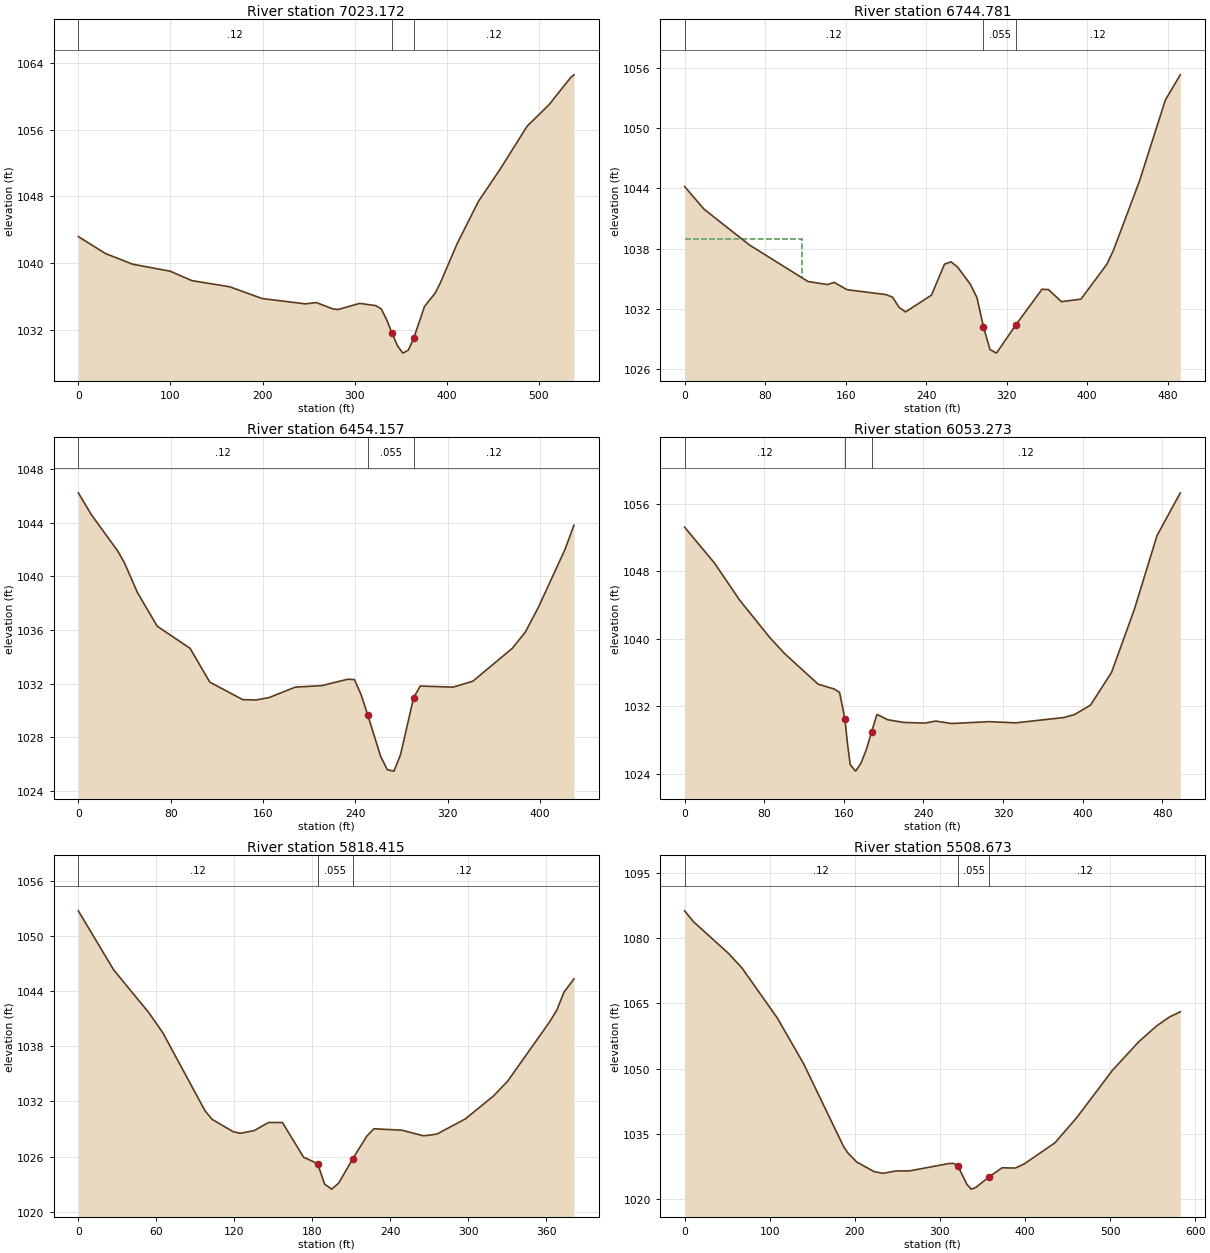
Type RM Length L Ch R = 1 ,7023.172,281.09,278.39,274.64
XS GIS Cut Line= 2
  1350775.051427   786983.962951  1350316.859859   787266.100606
#Sta/Elev= 30
       0 1043.19   29.36 1041.16   58.72 1039.88   99.82 1039.03  123.31  1037.9
  164.41 1037.16  199.64 1035.75  246.62 1035.11  258.36 1035.27  275.98 1034.52
  281.85 1034.43  305.34 1035.17  322.96  1034.9  328.83 1034.51   334.7 1033.22
  340.57 1031.58  346.44 1030.09  352.31  1029.2  358.19 1029.55  364.06 1030.97
   375.8  1034.8  387.54 1036.43  393.42 1037.73  411.03 1042.29  434.52 1047.44
  458.01 1051.29  487.37 1056.46  510.85 1058.99  534.34 1062.26  538.09  1062.6
#Mann= 3 , 0 , 0
       0     .12       0  340.57    .055       0  364.06     .12       0
Bank Sta=340.57,364.06
Exp/Cntr=0.3,0.1

Type RM Length L Ch R = 1 ,6744.781,302.23,290.62,278.94
XS GIS Cut Line= 2
  1350608.025894   786719.882103  1350226.575818   787031.362054
#Sta/Elev= 30
       0 1044.19   19.37 1041.93   64.55 1038.37  122.65 1034.74  142.01 1034.44
  148.47 1034.66  161.38 1033.93  200.11 1033.44  206.57 1033.19  213.02 1032.18
  219.49 1031.72   245.3 1033.39  258.21 1036.47  264.67  1036.7  271.12 1036.19
  284.03 1034.45  290.49 1033.13  296.94 1030.23  303.39 1027.98  309.85 1027.62
  329.23 1030.45  355.05 1033.97  361.49 1033.94   374.4 1032.74  393.77 1032.99
  419.59 1036.47  426.04 1037.84  451.86 1044.71  477.68  1052.8  492.47  1055.3
#Mann= 3 , 0 , 0
       0     .12       0  296.94    .055       0  329.23     .12       0
#XS Ineff= 2 , 0
          116.24 1039.02
Permanent Ineff=
       F       F
Bank Sta=296.94,329.23
Exp/Cntr=0.3,0.1

Type RM Length L Ch R = 1 ,6454.157,403.86,400.88,395.32
XS GIS Cut Line= 2
  1350267.203648   786509.971681  1350061.807439    786886.90759
#Sta/Elev= 30
       0 1046.23   11.39 1044.59   34.16 1041.89   39.86 1041.03   51.25 1038.79
   68.33 1036.29    96.8 1034.64  113.88 1032.12  142.35 1030.82  153.74 1030.79
  165.13 1030.97  187.92 1031.75  210.68 1031.86  233.46 1032.34  239.15 1032.31
  244.85  1031.2  250.54  1029.7  261.93 1026.57  267.62 1025.59  273.33 1025.49
  279.01  1026.7   290.4 1030.97  296.11 1031.83  324.57 1031.75  341.66 1032.19
  375.81 1034.64   387.2 1035.86   398.6 1037.73  421.38 1041.99  429.27 1043.82
#Mann= 3 , 0 , 0
       0     .12       0  250.54    .055       0   290.4     .12       0
Bank Sta=250.54,290.4
Exp/Cntr=0.3,0.1

Type RM Length L Ch R = 1 ,6053.273,231.89,234.86,234.49
XS GIS Cut Line= 4
  1349883.496418   786331.660707  1349869.953824   786449.029936
  1349759.355869   786733.424698  1349723.242253   786798.880656
#Sta/Elev= 30
       0 1053.21    30.2 1048.93   55.37 1044.56   85.56 1040.14  100.66 1038.21
  134.24 1034.61  150.34 1034.04   155.7 1033.64  161.07 1030.49  163.82  1027.4
  166.43 1025.07   171.8 1024.31  177.16 1025.24  182.53 1026.84  187.89 1028.96
  193.25 1031.03  203.99  1030.4  220.08 1030.08  241.54    1030  252.27 1030.24
  268.36 1029.95  305.91 1030.17  332.74 1030.03  381.02 1030.66  391.75 1031.01
  407.85 1032.13     429 1036.01  451.84 1043.45  474.69 1052.22  498.05 1057.28
#Mann= 3 , 0 , 0
       0     .12       0  161.07    .055       0  187.89     .12       0
Bank Sta=161.07,187.89
Exp/Cntr=0.3,0.1

Type RM Length L Ch R = 1 ,5818.415,312.83,309.74,305.68
XS GIS Cut Line= 2
  1349705.185445   786293.289984  1349558.473827   786645.397764
#Sta/Elev= 30
       0 1052.74   27.08 1046.34   54.17 1041.67      65 1039.48    97.5 1030.98
  102.92 1030.05  119.17  1028.7  124.58 1028.53  135.42 1028.82  146.25  1029.7
  157.08  1029.7  173.33 1025.93  184.17 1025.22  189.58 1022.99     195 1022.45
  200.42 1023.11  211.25 1025.77  222.08 1028.23   227.5 1029.02  249.17 1028.86
  265.42 1028.26  270.83 1028.33  276.25 1028.46  297.92  1030.1  319.58  1032.6
  330.42  1034.2  362.92  1040.7  368.33 1041.96  373.75 1043.89  381.46 1045.34
#Mann= 3 , 0 , 0
       0     .12       0  184.17    .055       0  211.25     .12       0
Bank Sta=184.17,211.25
Exp/Cntr=0.3,0.1

Type RM Length L Ch R = 1 ,5508.673,233.65,235.91,237.23
XS GIS Cut Line= 2
  1349427.561957    786067.57986  1349274.079111   786629.598063
#Sta/Elev= 30
       0 1086.29   10.37  1083.8   51.83 1076.46   67.38 1073.16  108.84 1061.69
  139.94 1051.12  186.59  1032.2  191.77 1030.66  202.14 1028.56  222.87 1026.32
  233.24 1025.94  248.79  1026.5  264.34  1026.5  310.99 1028.21  316.17 1028.23
  321.35 1027.59  331.72 1023.43   336.9 1022.31  342.08 1022.67  357.63 1025.09
  373.18 1027.22  388.73 1027.15   399.1  1028.1  435.38 1032.97   461.3 1038.85
  502.76  1049.6  533.86  1056.2  554.59  1059.8  570.14 1061.92   582.6 1063.07
#Mann= 3 , 0 , 0
       0     .12       0  321.35    .055       0  357.63     .12       0
Bank Sta=321.35,357.63
Exp/Cntr=0.3,0.1

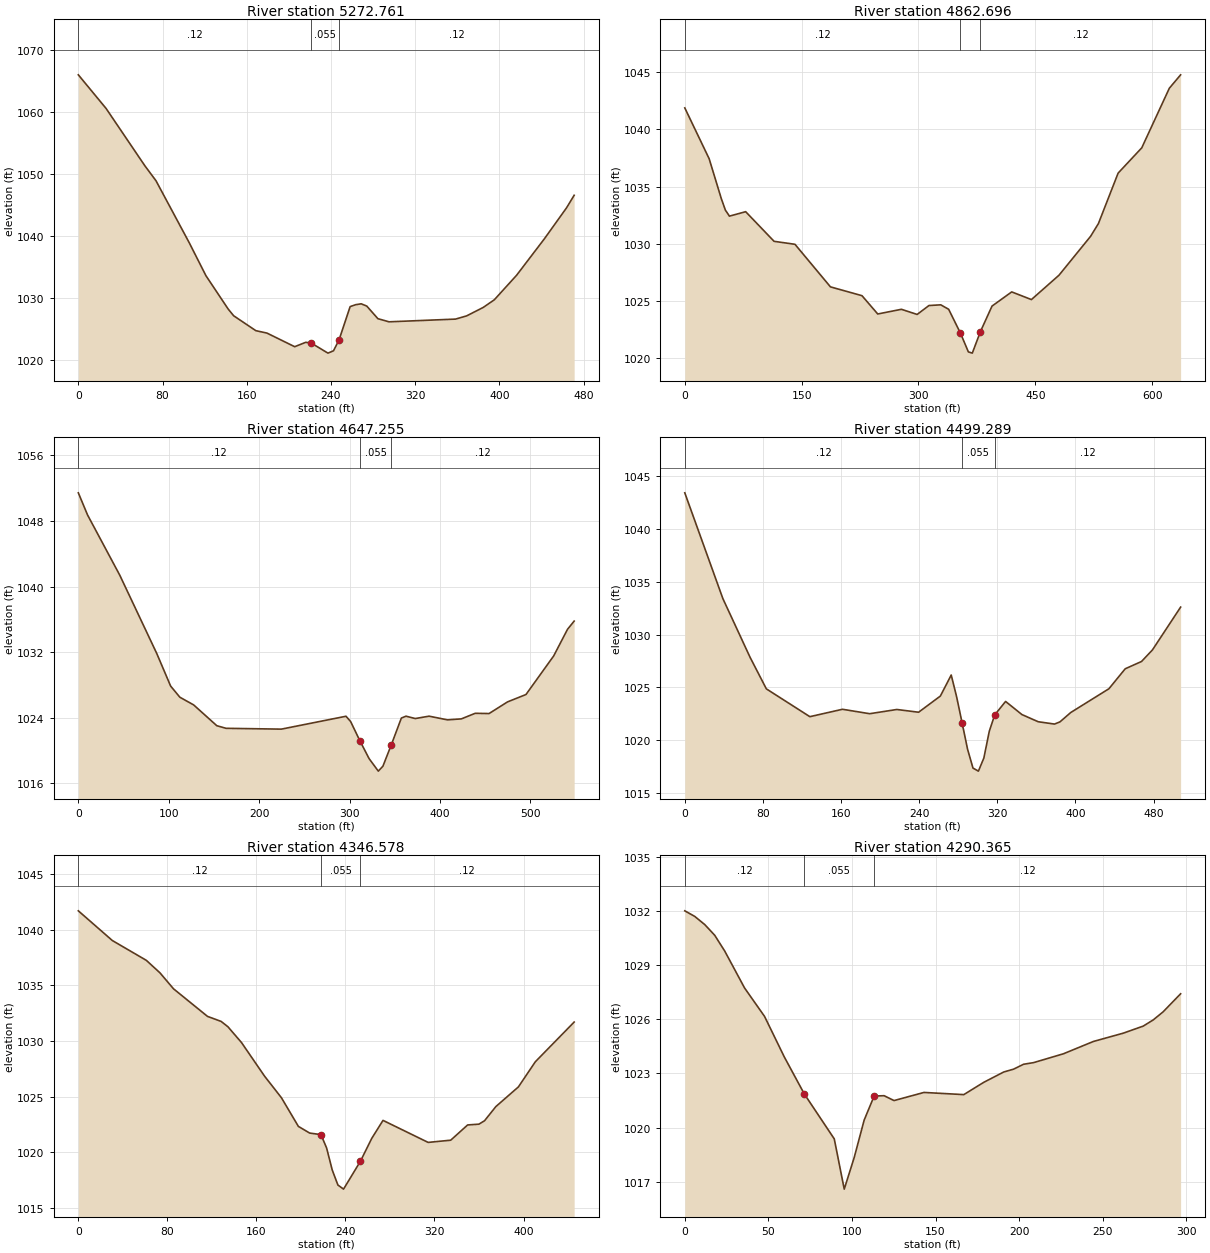
Type RM Length L Ch R = 1 ,5272.761,411.44,410.06,403.34
XS GIS Cut Line= 2
  1349204.108939   786074.351134  1349055.140261   786521.257168
#Sta/Elev= 30
       0 1066.02   26.35 1060.59   63.26 1051.31   73.79  1048.9  105.41 1038.87
  121.22 1033.56   142.3 1028.18  147.57 1027.08  168.65 1024.67  179.21 1024.28
  205.55 1022.08  216.09 1022.79  221.36 1022.66  237.17 1021.04  242.44 1021.42
  247.71 1023.18  258.25 1028.56  263.52 1028.87  268.79 1029.01  274.07 1028.64
  284.61 1026.61  295.16  1026.1  358.39 1026.54  368.93 1027.06  384.74 1028.43
  395.28 1029.67  416.37 1033.62  442.72  1039.5   463.8 1044.51  471.08 1046.55
#Mann= 3 , 0 , 0
       0     .12       0  221.36    .055       0  247.71     .12       0
Bank Sta=221.36,247.71
Exp/Cntr=0.3,0.1

Type RM Length L Ch R = 1 ,4862.696,212.57,215.44,209.69
XS GIS Cut Line= 3
  1348745.917417   785884.754626   1348784.28814   786015.666496
  1348707.546694   786509.971681
#Sta/Elev= 30
       0 1041.87   31.26 1037.43   46.89 1033.94    52.1 1032.94   57.31 1032.41
   78.16  1032.8  114.64 1030.21  141.49 1029.95  187.03 1026.23   227.5 1025.46
  247.75 1023.86   278.1 1024.27  298.34 1023.82  313.52  1024.6   328.7 1024.66
  338.82 1024.27  353.99 1022.18  364.11 1020.55  369.17 1020.44  379.53 1022.31
  394.47 1024.55  419.77 1025.79  445.07 1025.12  480.49 1027.25  520.97 1030.64
  531.09 1031.76  556.39 1036.17  586.75 1038.38  622.17 1043.59  636.65 1044.76
#Mann= 3 , 0 , 0
       0     .12       0  353.99    .055       0  379.53     .12       0
Bank Sta=353.99,379.53
Exp/Cntr=0.3,0.1

Type RM Length L Ch R = 1 ,4647.255,139.58,147.97,155.47
XS GIS Cut Line= 2
  1348639.833629   785853.155223  1348529.235674   786390.345298
#Sta/Elev= 30
       0 1051.43   10.21 1048.73   45.93 1041.37   86.77 1031.84   102.1 1027.87
  112.31 1026.51  127.61 1025.57  153.15 1023.04  163.36 1022.72   224.6 1022.62
  296.07 1024.19  301.19 1023.55   311.4 1021.21  321.61 1019.03  331.82  1017.5
  336.91  1018.1  346.15 1020.69  357.33 1023.97  362.45  1024.2  372.65 1023.91
  387.96  1024.2  408.38 1023.75  423.69 1023.87  439.01 1024.55  454.32 1024.52
  474.74 1025.94  495.16 1026.84  525.79 1031.54  541.11 1034.79  548.46 1035.79
#Mann= 3 , 0 , 0
       0     .12       0   311.4    .055       0  346.15     .12       0
Bank Sta=311.4,346.15
Exp/Cntr=0.3,0.1

Type RM Length L Ch R = 1 ,4499.289,162.1,152.71,143.63
XS GIS Cut Line= 2
  1348558.578016   785905.068541  1348335.124999   786361.003002
#Sta/Elev= 30
       0 1043.41   38.98 1033.41   66.82 1027.86   83.52 1024.87  128.07 1022.24
  161.48 1022.94  189.32 1022.52  217.16 1022.92  239.42 1022.66  261.71 1024.19
  272.84 1026.18  278.41  1024.1  283.98 1021.65  289.55 1019.17  295.11 1017.38
  300.68 1017.09  306.25 1018.33  311.82 1020.86  317.39 1022.41  328.52 1023.68
  345.23 1022.44  361.92 1021.76  378.64 1021.54  384.21 1021.75  395.34 1022.64
  434.32 1024.88  451.02 1026.77  467.73 1027.46  478.87 1028.55  507.75  1032.6
#Mann= 3 , 0 , 0
       0     .12       0  283.98    .055       0  317.39     .12       0
Bank Sta=283.98,317.39
Exp/Cntr=0.3,0.1

Type RM Length L Ch R = 1 ,4346.578,42.82,56.21,68.53
XS GIS Cut Line= 3
  1348389.295423   785920.868242  1348299.011383   786049.523052
  1348251.612232   786333.917767
#Sta/Elev= 30
       0 1041.71   30.55 1039.04   61.08 1037.26    73.3 1036.14   85.52  1034.7
  116.06 1032.22  128.27 1031.77  134.39 1031.29   146.6 1029.87  167.31 1026.85
  182.53  1024.9  197.72 1022.33  207.86 1021.73     218 1021.59  223.07 1020.39
  228.14 1018.41  233.22 1017.06  238.29 1016.69  253.48  1019.2  263.62 1021.25
  273.76 1022.87  314.31 1020.89   334.6 1021.09  349.79 1022.46  359.93 1022.53
     365 1022.84  375.14 1024.11  395.41 1025.88  410.62 1028.14   445.5 1031.71
#Mann= 3 , 0 , 0
       0     .12       0     218    .055       0  253.48     .12       0
Bank Sta=218,253.48
Exp/Cntr=0.3,0.1

Type RM Length L Ch R = 1 ,4290.365,57.07,72.72,86.75
XS GIS Cut Line= 2
  1348293.455345   786014.188813  1348131.918981   786262.978461
#Sta/Elev= 30
       0    1032    5.96 1031.69   11.93 1031.24   17.88 1030.65   23.85 1029.78
   35.77 1027.73    47.7 1026.16   59.61  1023.9   71.54 1021.86   89.42 1019.38
   95.39  1016.6  101.35 1018.35  107.31 1020.42  113.27 1021.75  119.23 1021.77
  125.19  1021.5  143.08 1021.95  166.92 1021.83  178.85 1022.51  190.77 1023.08
  196.73 1023.24  202.69 1023.51  208.65  1023.6  226.54 1024.09  244.42 1024.77
  262.31 1025.23  274.23 1025.62  280.19 1025.96  286.15 1026.41  296.63 1027.41
#Mann= 3 , 0 , 0
       0     .12       0   71.54    .055       0  113.27     .12       0
Bank Sta=71.54,113.27
Exp/Cntr=0.5,0.3