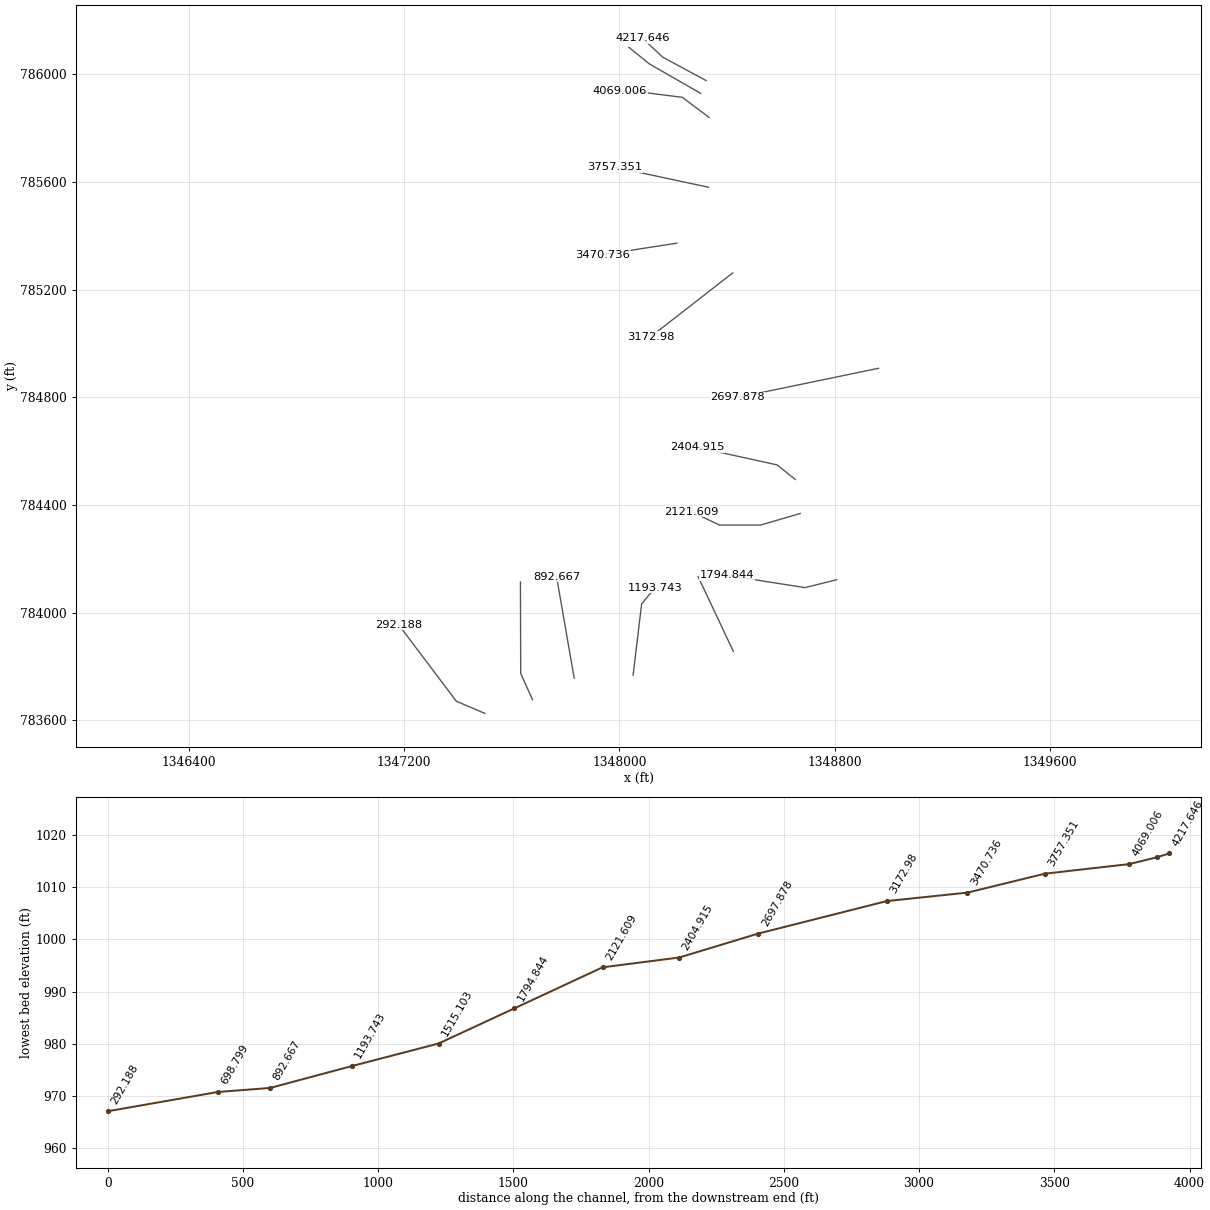
HEC-RAS study StirewaitCr.prj: StirewaitCr

--- StirewaitCr.g01 (geometry) --- (continued)

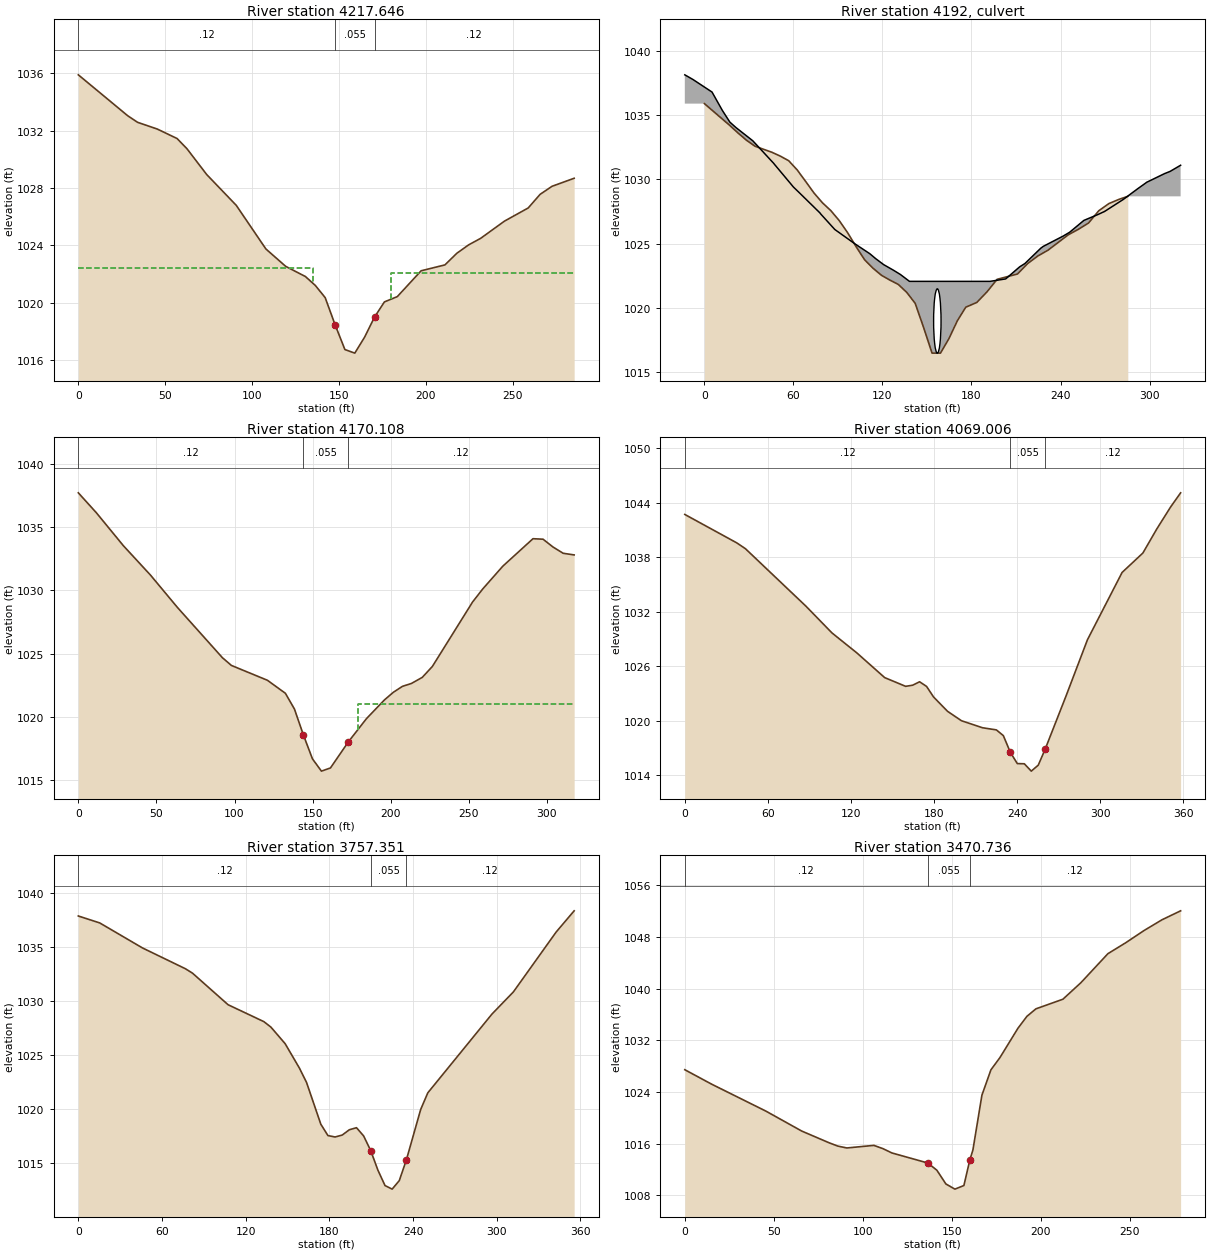
Type RM Length L Ch R = 1 ,4217.646,48.56,47.54,47.96
XS GIS Cut Line= 3
  1348321.753721   785976.457676  1348160.217311   786063.710913
  1348085.934137   786133.277683
#Sta/Elev= 30
       0 1035.89    28.4 1033.04   34.09 1032.58   45.45 1032.11   56.83 1031.45
   62.51 1030.74   73.88 1028.94   90.91 1026.79  107.96 1023.75  119.34 1022.54
  130.69 1021.83  136.39 1021.21  142.07 1020.36  147.74 1018.48  153.42 1016.74
  159.12 1016.49  164.79 1017.61  170.47    1019  176.16 1020.06  183.59 1020.43
  197.29 1022.23  210.99 1022.64  217.84 1023.45  224.69 1024.04  231.54 1024.49
  245.24 1025.69  258.94 1026.61  265.79 1027.56  272.64 1028.12  285.37 1028.68
#Mann= 3 , 0 , 0
       0     .12       0  147.74    .055       0  170.47     .12       0
#XS Ineff= 2 , 0
       0     135 1022.44     180       0 1022.07
Permanent Ineff=
       F       F
Bank Sta=147.74,170.47
Exp/Cntr=0.5,0.3

Type RM Length L Ch R = 2 ,4192    ,,,
BEGIN DESCRIPTION:
37003-0099 Culvert X-ing (Driveway)
END DESCRIPTION:
Bridge Culvert--1,0,-1,-1, 0
Deck Dist Width WeirC Skew NumUp NumDn MinLoCord MaxHiCord MaxSubmerge Is_Ogee
20,25,2.6,0, 57, 57, , , 0.95, 0, 0,0,,
  -13.21   -7.75    5.15   12.11   17.19   21.27   32.63   46.51   47.94   60.04
      64   77.89   78.47   87.52    87.8   88.17  101.55  111.49  115.41  120.84
  127.37  132.16  138.21  147.96   150.7  152.51  156.34   156.9  156.98  163.41
  163.44  176.06  177.22  179.14  184.13  190.32  192.54  203.04  212.48  215.79
  216.22  226.63  228.11  229.18  241.77  246.17  255.75  265.28  269.76  282.31
  283.36  292.11  297.34  297.99  310.15  313.85  320.96
 1038.13 1037.77 1036.79 1035.36 1034.45 1034.03    1033 1031.27 1031.07  1029.4
 1028.96 1027.39  1027.3 1026.15 1026.11 1026.08 1024.98 1024.22 1023.84 1023.37
 1022.94  1022.6 1022.07 1022.07 1022.07 1022.07 1022.07 1022.07 1022.07 1022.07
 1022.07 1022.07 1022.07 1022.07 1022.07 1022.07 1022.07 1022.26  1023.2 1023.44
 1023.48 1024.64 1024.77 1024.84 1025.59 1025.89 1026.81 1027.27 1027.51 1028.44
 1028.53 1029.28 1029.71 1029.77 1030.45 1030.62  1031.1
                                                                                
                                                                                
                                                                                
                                                                                
                                                                                
                                                        
  -13.78   -8.32    4.58   11.54   16.62    20.7   32.06   45.94   47.37   59.47
   63.43   77.32    77.9   86.95   87.23    87.6  100.98  110.92  114.84  120.27
   126.8  131.59  137.64  147.39  150.13  151.94  155.77  156.33  156.41  162.84
  162.87  175.49  176.65  178.57  183.56  189.75  191.97  202.47  211.91  215.22
  215.65  226.06  227.54  228.61   241.2   245.6  255.18  264.71  269.19  281.74
  282.79  291.54  296.77  297.42  309.58  313.28  320.39
 1038.13 1037.77 1036.79 1035.36 1034.45 1034.03    1033 1031.27 1031.07  1029.4
 1028.96 1027.39  1027.3 1026.15 1026.11 1026.08 1024.98 1024.22 1023.84 1023.37
 1022.94  1022.6 1022.07 1022.07 1022.07 1022.07 1022.07 1022.07 1022.07 1022.07
 1022.07 1022.07 1022.07 1022.07 1022.07 1022.07 1021.66 1022.26  1023.2 1023.44
 1023.48 1024.64 1024.77 1024.84 1025.59 1025.89 1026.81 1027.27 1027.51 1028.44
 1028.53 1029.28 1029.71 1029.77 1030.45 1030.62  1031.1
                                                                                
                                                                                
                                                                                
                                                                                
                                                                                
                                                        
BR Coef=-1 , 0 , 0 ,, 0 ,,,0.8,-1,,0,
WSPro=,,,, 1 ,,,, 0 ,,,, 0 ,,,,-1 ,-1 ,-1 , 0 , 0 , 0 , 0 , 0
Culvert=1,5,,12,0.024,0.9,1,2,3,1016.49,156.98,1015.73,157.14,Culvert #1  , 0 ,27
Culvert Bottom n=0.024
BR U #Sta/Elev= 43
       0 1035.89   17.05  1034.2   22.73  1033.6    28.4 1033.04   34.09 1032.58
   45.45 1032.11   51.15 1031.81   56.83 1031.45   62.51 1030.74   68.18 1029.85
   73.88 1028.94   79.56 1028.18   85.23 1027.57   90.91 1026.79   96.61 1025.84
  102.29 1024.76  107.96 1023.75  113.65 1023.09  119.34 1022.54  125.01 1022.17
  130.69 1021.83  136.39 1021.21  142.07 1020.36  147.74 1018.48  153.42 1016.49
  159.12 1016.49  164.79 1017.61  170.47    1019  176.16 1020.06  183.59 1020.43
  190.44 1021.25  197.29 1022.23  210.99 1022.64  217.84 1023.45  224.69 1024.04
  231.54 1024.49  245.24 1025.69  252.09 1026.12  258.94 1026.61  265.79 1027.56
  272.64 1028.12  279.49 1028.45  285.37 1028.68
BR U #Mann= 3
       0      .1  147.74    .055  164.79      .1
BR D #Sta/Elev= 50
       0 1037.69    5.77 1036.92   11.53 1036.12   23.06 1034.37   28.83 1033.52
   34.59 1032.74   46.12 1031.21   51.89 1030.38   57.65 1029.48   63.43 1028.65
   69.18 1027.92   74.96 1027.12   80.71 1026.25   86.48 1025.44   92.26 1024.68
   98.01 1024.07  103.79 1023.72  115.32 1023.24  121.07  1022.9  126.85 1022.43
   132.6 1021.87  138.38 1020.63  144.13 1018.58  149.91  1016.7  155.66 1015.73
  161.44 1015.73  167.19 1017.04  172.97 1018.05  178.73 1018.97  184.49 1019.87
  190.27 1020.62  196.02 1021.35   201.8 1021.96  207.55 1022.42  213.33 1022.65
  220.26 1023.13   226.7 1023.99  233.14 1025.22  239.59 1026.55  246.03 1027.85
  252.47 1029.08  258.92  1030.1  265.36 1030.99   271.8  1031.9  278.24 1032.66
  291.13 1034.07  297.57 1034.03  304.01 1033.41  310.45 1032.92  317.49 1032.79
BR D #Mann= 3
       0      .1  149.91    .055  167.19      .1
BC Design=,, 0 ,, 0 ,,,,,,

Type RM Length L Ch R = 1 ,4170.108,88.7,101.1,112.3
XS GIS Cut Line= 3
  1348301.525954   785928.990166  1348110.512112   786038.646275
  1348035.049838   786099.959385
#Sta/Elev= 30
       0 1037.69   11.53 1036.12   28.83 1033.52   46.12 1031.21   63.43 1028.65
   92.26 1024.68   98.01 1024.07  121.07  1022.9   132.6 1021.87  138.38 1020.63
  144.13 1018.58  149.91  1016.7  155.66 1015.73  161.44 1015.98  172.97 1018.05
  184.49 1019.87  196.02 1021.35   201.8 1021.96  207.55 1022.42  213.33 1022.65
  220.26 1023.13   226.7 1023.99  252.47 1029.08  258.92  1030.1   271.8  1031.9
  291.13 1034.07  297.57 1034.03  304.01 1033.41  310.45 1032.92  317.49 1032.79
#Mann= 3 , 0 , 0
       0     .12       0  144.13    .055       0  172.97     .12       0
#XS Ineff= 2 , 0
       0     135    1021     179       0    1021
Permanent Ineff=
       F       F
Bank Sta=144.13,172.97
Exp/Cntr=0.5,0.3

Type RM Length L Ch R = 1 ,4069.006,313.89,311.65,308.88
XS GIS Cut Line= 4
  1348332.867892   785839.612629  1348233.555424   785914.096968
  1348073.301259   785934.410883  1348001.074026    785936.66799
#Sta/Elev= 30
       0 1042.71    37.5 1039.58   43.75 1038.94    87.5  1032.6  106.25 1029.66
  124.14 1027.47   144.3 1024.74  159.42 1023.78  164.46  1023.9   169.5 1024.28
  174.54 1023.77  179.58 1022.61  189.66 1021.03  199.74 1019.99  214.86 1019.22
  224.94 1018.98  229.98 1018.35  235.02 1016.51  240.06 1015.27   245.1 1015.25
  250.14 1014.44  255.18  1015.1  260.22 1016.88  275.34 1022.76  290.69 1028.91
   315.7 1036.32  330.71 1038.46   340.7  1041.1  350.72 1043.53  357.95 1045.09
#Mann= 3 , 0 , 0
       0     .12       0  235.02    .055       0  260.22     .12       0
Bank Sta=235.02,260.22
Exp/Cntr=0.3,0.1

Type RM Length L Ch R = 1 ,3757.351,275.43,286.62,297.37
XS GIS Cut Line= 2
  1348330.610785   785580.045995  1347983.017218   785654.530335
#Sta/Elev= 30
       0  1037.9   15.34 1037.26   46.02 1034.94    76.7 1033.02   81.82 1032.61
  107.38 1029.68  132.95 1028.12  138.06 1027.61  148.29 1026.07  158.52 1023.81
  163.63 1022.48  173.86 1018.61  178.97 1017.56   184.1 1017.43   189.2 1017.61
  194.31  1018.1  199.43 1018.29  204.54 1017.53  209.65 1016.16  214.77 1014.36
  219.88 1012.93  224.99  1012.6  230.11 1013.39  235.22 1015.32  245.45 1019.98
  250.56 1021.52  296.58 1028.82  311.92 1030.87   342.6 1036.42  355.48 1038.38
#Mann= 3 , 0 , 0
       0     .12       0  209.65    .055       0  235.22     .12       0
Bank Sta=209.65,235.22
Exp/Cntr=0.3,0.1

Type RM Length L Ch R = 1 ,3470.736,282.23,297.76,312.65
XS GIS Cut Line= 2
  1348213.241509   785372.392679  1347937.875175   785329.507743
#Sta/Elev= 30
       0 1027.45   15.18  1025.2   45.54 1021.05   65.77 1017.95   80.95 1016.16
   86.01 1015.63   91.07 1015.34  106.27 1015.74  111.33 1015.24  116.39 1014.57
  136.63 1013.01  141.69 1011.89  146.75 1009.77  151.81 1008.97  156.87 1009.53
  160.23 1013.51  161.93 1015.02  166.99  1023.5  172.05 1027.43  177.11 1029.32
  187.23 1033.86  192.29 1035.71  197.34 1036.87  212.52 1038.36  222.64 1040.92
  237.82 1045.41  247.94 1047.12  258.06 1048.98  268.18 1050.65  278.68 1052.04
#Mann= 3 , 0 , 0
       0     .12       0  136.63    .055       0  160.23     .12       0
Bank Sta=136.63,160.23
Exp/Cntr=0.3,0.1

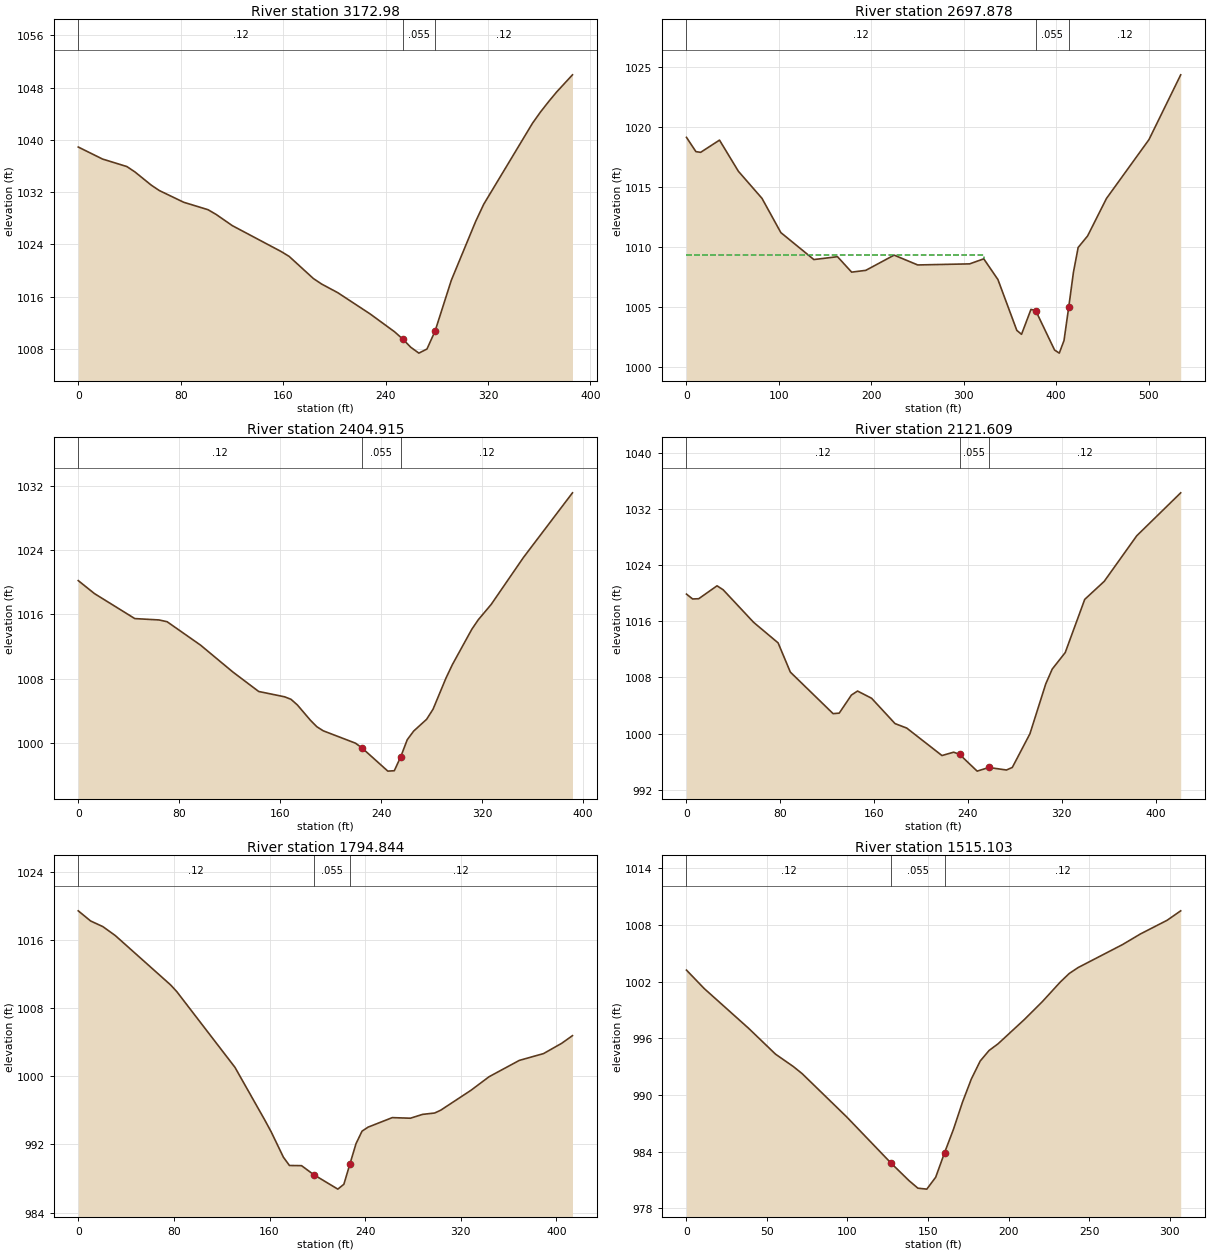
Type RM Length L Ch R = 1 ,3172.98 ,488.54,475.1,459.95
XS GIS Cut Line= 2
  1348420.894825   785261.794724  1348116.186149   785024.799066
#Sta/Elev= 30
       0 1038.89   18.99 1037.05      38  1035.9   44.34 1035.07   57.01 1033.06
   63.33 1032.23   82.34 1030.44  101.35  1029.3  107.67 1028.58  120.34 1026.86
  158.36 1022.91  164.68 1022.16  183.68 1018.76  190.03 1017.93   202.7  1016.6
  228.04 1013.34  247.03 1010.62  253.37 1009.52   259.7 1008.25  266.04 1007.35
  272.37 1007.98  278.71 1010.73  291.38  1018.5  310.38  1027.5  316.71 1030.14
  354.72 1042.51  361.06 1044.26  367.39 1045.84  373.71 1047.33  386.01 1049.94
#Mann= 3 , 0 , 0
       0     .12       0  253.37    .055       0  278.71     .12       0
Bank Sta=253.37,278.71
Exp/Cntr=0.3,0.1

Type RM Length L Ch R = 1 ,2697.878,304.98,292.96,279.89
XS GIS Cut Line= 2
  1348962.599114   784907.429837  1348438.951634   784799.088942
#Sta/Elev= 30
       0 1019.13   10.21 1017.94   15.32 1017.88   35.74  1018.9   56.16  1016.3
   81.69 1014.04  102.12 1011.18  137.86 1008.93  163.39 1009.17  178.71 1007.88
  194.02 1008.03  224.66  1009.3  250.19 1008.48  306.35 1008.57  321.67 1008.99
  336.99 1007.26  357.41 1003.02  362.52 1002.69  372.73 1004.77  377.84 1004.67
  398.26 1001.38  403.36 1001.12  408.47 1002.17  413.58 1004.95  418.68 1007.87
  423.79 1009.94     434  1010.9  454.42 1014.03  500.38 1018.94  534.74 1024.35
#Mann= 3 , 0 , 0
       0     .12       0  377.84    .055       0  413.58     .12       0
#XS Ineff= 2 , 0
          322.14 1009.28
Permanent Ineff=
       F       F
Bank Sta=377.84,413.58
Exp/Cntr=0.3,0.1

Type RM Length L Ch R = 1 ,2404.915,274.71,283.31,287.65
XS GIS Cut Line= 3
   1348653.37627   784494.380312  1348585.663205   784548.550736
  1348287.725849   784614.006648
#Sta/Elev= 30
       0  1020.2   12.81 1018.59   44.82 1015.48   64.03 1015.31   70.43 1015.09
   96.95 1012.18  122.56 1008.84  143.03 1006.42   163.5 1005.76  168.62 1005.45
  173.74 1004.74  183.99 1002.85  189.11 1002.04  194.22 1001.53  219.82  999.99
  224.93   999.4  245.41  996.52  250.53  996.57  255.66  998.32  260.77 1000.42
  265.89  1001.5  276.13 1002.96  281.25 1004.22  291.48 1008.08   296.6 1009.77
  311.96 1014.15  317.08 1015.33  327.32 1017.24  352.92 1023.08  391.76 1031.11
#Mann= 3 , 0 , 0
       0     .12       0  224.93    .055       0  255.66     .12       0
Bank Sta=224.93,255.66
Exp/Cntr=0.3,0.1

Type RM Length L Ch R = 1 ,2121.609,328.2,326.76,321.17
XS GIS Cut Line= 4
  1348671.433078   784367.982609  1348524.721507   784325.097718
  1348371.238615   784325.097718  1348267.411934   784374.753929
#Sta/Elev= 30
       0 1019.86    5.21 1019.17   10.42  1019.2   26.05 1021.04   31.26 1020.48
    57.3 1015.83   78.14 1012.91   88.56 1008.75  125.02 1002.83  130.23  1002.9
  140.65 1005.48  145.86 1006.05  157.85 1005.02  177.85 1001.41  187.85 1000.77
  217.85  996.86  227.85  997.34  232.85  997.03  247.85  994.64  257.85  995.16
  272.85   994.8  277.85  995.17  292.85  999.96  306.33 1007.06  311.88 1009.18
  322.95 1011.53  339.59 1019.11  356.22 1021.68  383.93 1028.17  421.42 1034.29
#Mann= 3 , 0 , 0
       0     .12       0  232.85    .055       0  257.85     .12       0
Bank Sta=232.85,257.85
Exp/Cntr=0.3,0.1

Type RM Length L Ch R = 1 ,1794.844,309.05,279.74,249.95
XS GIS Cut Line= 3
  1348806.859162    784121.95857  1348689.489886   784092.616274
  1348400.580911   784137.758317
#Sta/Elev= 30
       0 1019.48   10.31 1018.29   20.62 1017.62   30.92 1016.58   77.31 1010.76
   82.46 1009.97   131.1 1001.07  156.41  994.78  161.47  993.46  171.59  990.51
  176.65  989.53  186.77  989.51  196.89  988.46  217.12  986.75  222.18  987.32
  227.25  989.71  232.32  992.09  237.38  993.57  242.44  994.04  262.68  995.16
  277.86  995.09  287.97  995.54  298.09   995.7  303.16  996.03  328.47  998.37
  343.65  999.97  368.94 1001.89   389.2 1002.69  404.38  1003.9   413.4  1004.8
#Mann= 3 , 0 , 0
       0     .12       0  196.89    .055       0  227.25     .12       0
Bank Sta=196.89,227.25
Exp/Cntr=0.3,0.1

Type RM Length L Ch R = 1 ,1515.103,337.57,321.36,303.44
XS GIS Cut Line= 2
  1348423.151932   783855.620662  1348292.240062   784133.244104
#Sta/Elev= 28
       0 1003.22   11.06 1001.26   38.69  997.04   55.28  994.32   66.33  993.01
   71.86  992.25    99.5  987.67  127.14  982.76   138.2  980.92  143.73  980.12
  149.26  980.02  154.78  981.28  160.31  983.89  165.84  986.37  171.37  989.21
   176.9  991.68  182.42  993.59  187.95  994.71  193.48  995.41  210.06  998.02
  221.12   999.9  232.17 1001.96   237.7 1002.86  243.23 1003.49  270.87 1005.93
  281.93 1007.05  298.51  1008.5  306.94  1009.5
#Mann= 3 , 0 , 0
       0     .12       0  127.14    .055       0  160.31     .12       0
Bank Sta=127.14,160.31
Exp/Cntr=0.3,0.1

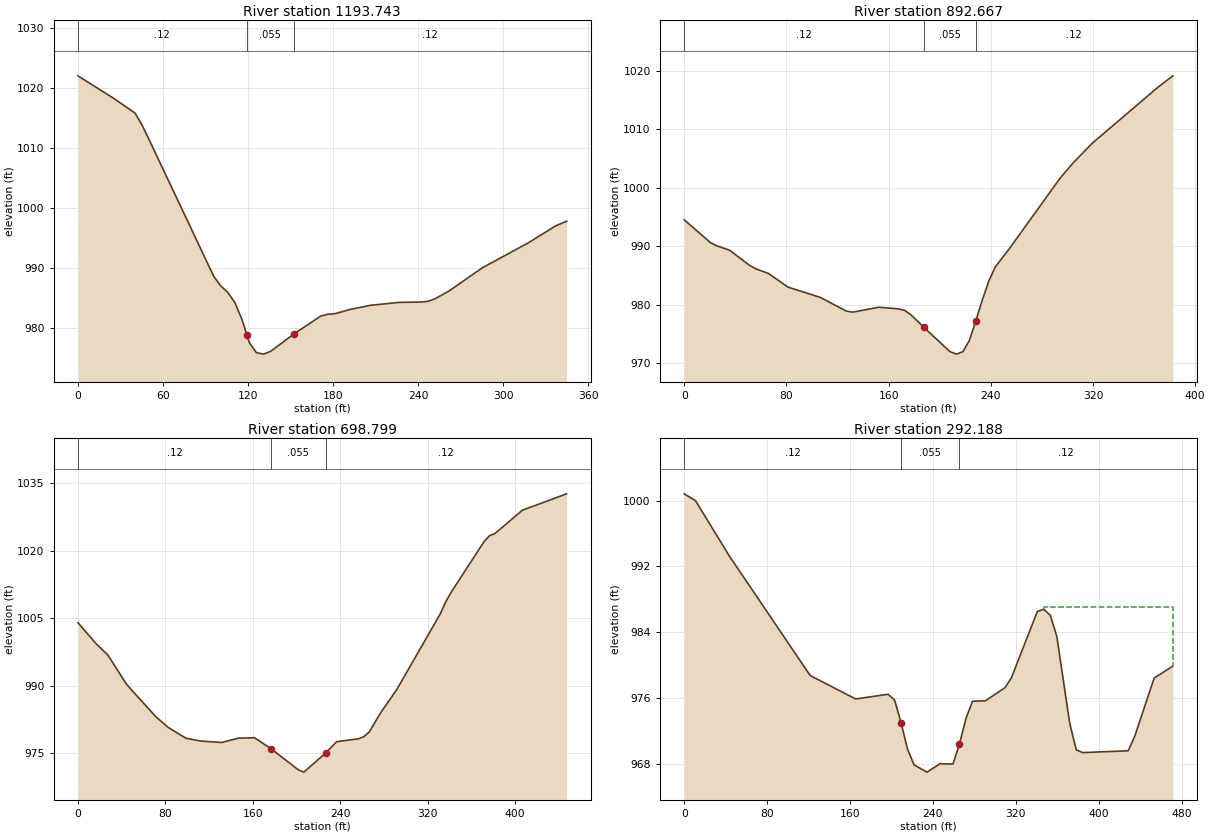
Type RM Length L Ch R = 1 ,1193.743,292.27,301.08,309.42
XS GIS Cut Line= 3
  1348050.730237   783767.593682  1348082.329639   784031.674529
  1348131.985896   784092.616274
#Sta/Elev= 30
       0 1022.09   25.18 1018.34    40.3 1015.87   45.32 1013.81   50.37 1011.35
   95.68  988.69  100.71  987.05  105.75  985.97  110.78  984.23  115.82  981.38
  119.01  978.95  120.87   977.6  125.89  975.93  130.93  975.69  135.96  976.17
  152.16  979.03  171.21  982.04  176.25  982.34  181.28  982.43  191.37  983.11
  206.46  983.84  226.61  984.32  241.71  984.37  246.75  984.49  251.78  984.91
  261.85  986.24  285.31   990.1  317.56  994.24  336.91  997.08  344.58  997.85
#Mann= 3 , 0 , 0
       0     .12       0  119.01    .055       0  152.16     .12       0
Bank Sta=119.01,152.16
Exp/Cntr=0.3,0.1

Type RM Length L Ch R = 1 ,892.667 ,198.55,193.87,187.99
XS GIS Cut Line= 2
  1347831.791433   783756.308195  1347766.335475   784133.244104
#Sta/Elev= 30
       0  994.51    20.3  990.64   25.36  990.06   35.51  989.31   50.75  986.77
   55.81  986.14   65.96  985.32    81.2  982.99  106.57  981.22  126.87  978.88
  131.94   978.7  152.24  979.54  167.47  979.27  172.53  979.01  177.62  978.22
  187.77  976.07  208.07  971.94  213.13  971.51  218.22  971.93  223.28  973.86
  228.37  977.25  233.43   980.8  238.52  984.05  243.58  986.45  253.73  989.32
  294.34 1001.65  304.49 1004.25   319.7 1007.66  370.45 1017.12  382.57 1019.16
#Mann= 3 , 0 , 0
       0     .12       0  187.77    .055       0  228.37     .12       0
Bank Sta=187.77,228.37
Exp/Cntr=0.3,0.1

Type RM Length L Ch R = 1 ,698.799 ,382.21,406.61,421.02
XS GIS Cut Line= 3
  1347676.986063   783676.417575  1347633.124123   783773.540363
  1347632.079831   784113.992362
#Sta/Elev= 30
       0 1003.99   16.46  999.35   27.43  996.77   43.89  990.48   49.38  988.91
   71.32  983.06   82.28  980.73   98.75  978.28  111.57  977.67  131.57  977.33
  146.57  978.29  161.57  978.38  176.57  975.94  201.57  971.25  206.57  970.73
  226.57  974.96  236.57   977.5  256.57  978.14  261.57  978.61  266.57  979.68
  276.57  983.82  291.57  989.07  331.57 1005.99  336.57 1008.67  341.57 1010.81
  371.57 1022.05  376.57 1023.36  381.57 1023.85  406.57 1029.02  447.02 1032.67
#Mann= 3 , 0 , 0
       0     .12       0  176.57    .055       0  226.57     .12       0
Bank Sta=176.57,226.57
Exp/Cntr=0.3,0.1

Type RM Length L Ch R = 1 ,292.188 ,285.67,292.18,299.01
XS GIS Cut Line= 3
  1347499.997521   783625.396324  1347393.913779   783670.538368
  1347179.489143   783954.933083
#Sta/Elev= 30
       0 1000.82   10.87  999.99   43.47  993.28  121.56  978.76  165.38  975.92
  196.69  976.49  202.96  975.79  209.22  973.04  215.48  969.82  221.74  967.93
  234.27  967.04  246.79  968.06  259.31  968.02  265.58  970.46  271.84  973.54
   278.1  975.64  290.62   975.7  309.41  977.28  315.67  978.48  340.72  986.54
  346.98   986.8  353.24  986.07  359.51  983.52  372.03  972.91  378.29  969.74
  384.56  969.41  428.39  969.63  434.65  971.38  453.44  978.46  471.46   979.9
#Mann= 3 , 0 , 0
       0     .12       0  209.22    .055       0  265.58     .12       0
#XS Ineff= 2 , 0
                          346.68          987.03
Permanent Ineff=
       F       F
Bank Sta=209.22,265.58
Exp/Cntr=0.3,0.1

Chan Stop Cuts=-1
Use User Specified Reach Order=0
User Specified Reach Order=StirewaitCr     ,Main