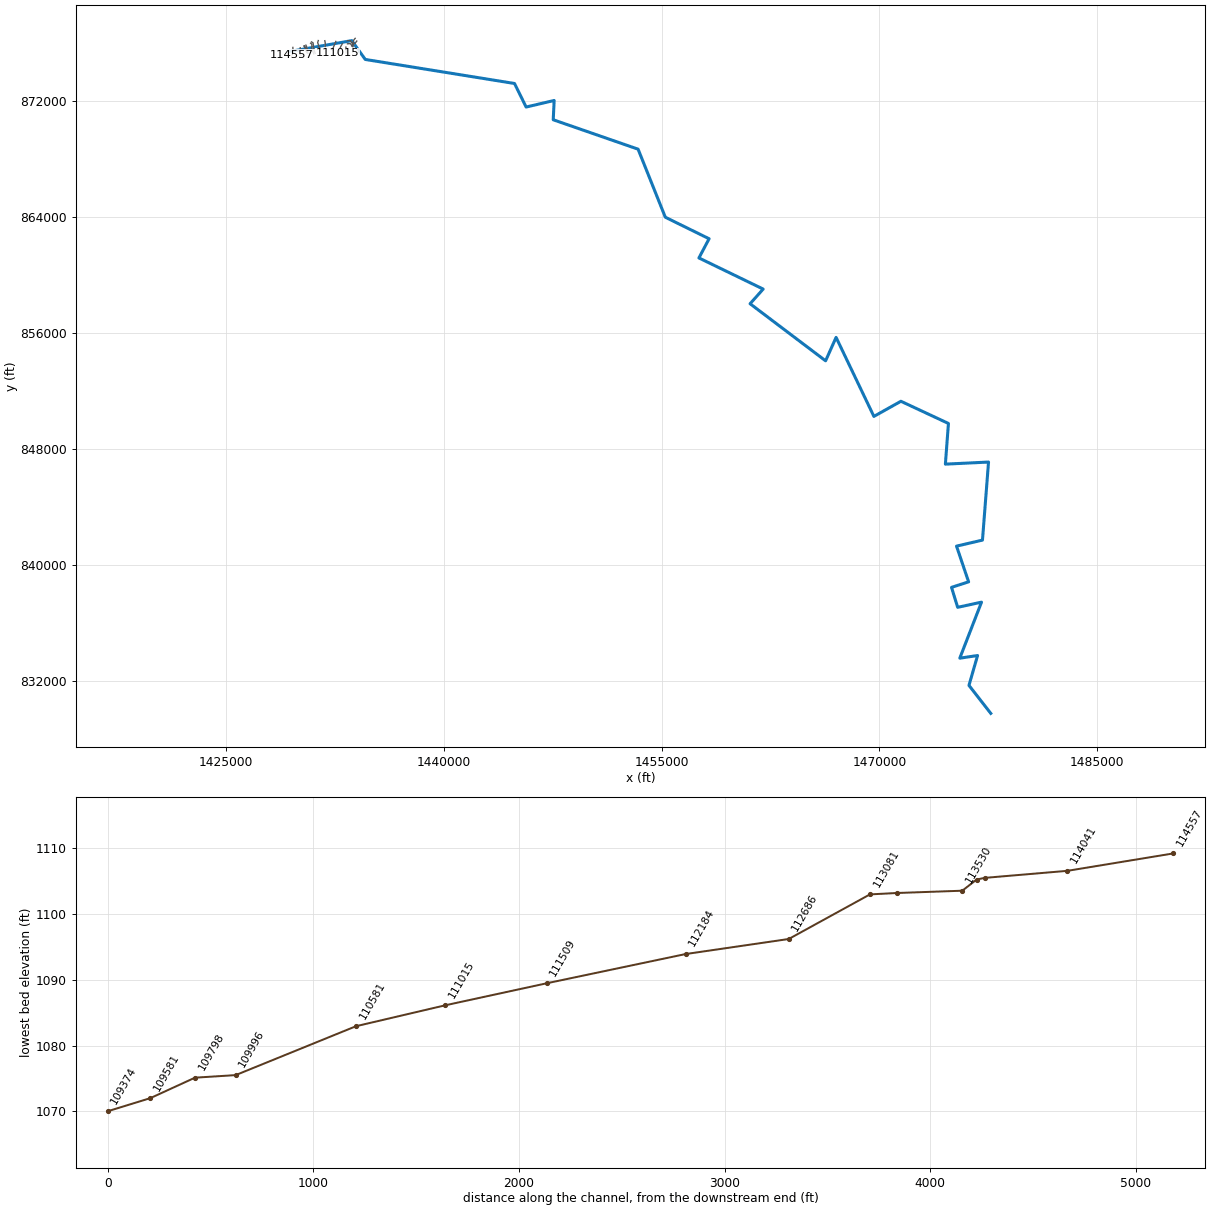
--- North Little Hunting Creek.prj (project) ---

Proj Title=North Little Hunting Creek Limited Detail Study
Current Plan=p01
Default Exp/Contr=0.3,0.1
English Units
Geom File=g01
Flow File=f01
Plan File=p01
Y Axis Title=Elevation
X Axis Title(PF)=Main Channel Distance
X Axis Title(XS)=Station
BEGIN DESCRIPTION:
North Little Hunting Creek
END DESCRIPTION:
DSS Export Rating Curves= 0
DSS Export Rating Curve Sorted= 0
DSS Export Volume Flow Curves= 0
DXF OffsetX= 0
DXF OffsetY= 0
DXF ScaleX= 1
DXF ScaleY= 10

--- North Little Hunting Creek.p01 (plan) ---

Plan Title=Floodway Run
Program Version=3.12
Short Identifier=Floodway
Geom File=g01
Flow File=f01
Subcritical Flow
K Sum by GR= 0
Std Step Tol= 0.01
Critical Tol= 0.01
Num of Std Step Trials= 20
Max Error Tol= 0.3
Flow Tol Ratio= 0.001
Split Flow NTrial= 30
Split Flow Tol= 0.02
Split Flow Ratio= 0.02
Log Output Level= 0
Friction Slope Method= 1
Unsteady Friction Slope Method= 2
Unsteady Bridges Friction Slope Method= 1
Parabolic Critical Depth
Global Vel Dist= 0 , 0 , 0
Global Log Level= 0
CheckData=True
Encroach Param=-1 ,0,0, 2
Encroach River=North Little Hun
Encroach Reach=Reach-1
Encroach Node=114557
       1    4915    5025
Encroach Node=114041
       1    4990    5040
Encroach Node=113639
       1  4985.5  5019.5
Encroach Node=113600
       1  4985.1  5017.4
Encroach Node=113530
       1 4933.96 5014.78
Encroach Node=113211
       1    4978    5022
Encroach Node=113081
       1    4978  5018.7
Encroach Node=112686
       1 4920.99 5078.67
Encroach Node=112184
       1 4983.54 5031.15
Encroach Node=111509
       1 4980.12  5014.2
Encroach Node=111015
       1  4985.8 5112.64
Encroach Node=110581
       1  4985.8 5018.43
Encroach Node=109996
       1  4985.8  5014.2
Encroach Node=109798
       1  4965.8    5200
Encroach Node=109581
       1  4985.5    5023
Encroach Node=109374
       1 4970.79  5014.9
Encroach Node=109114
       1  4985.1  5014.9
Encroach Node=108862
       1    4981 5038.28
Encroach Node=108332
       1    4984  5014.9
Encroach Node=107934
       1  4985.1    5010
Encroach Node=107384
       1  4982.2  5072.5
Encroach Node=107147
       1  4982.2  5017.8
Encroach Node=106776
       1  4982.2  5031.9
Encroach Node=106286
       1  4982.2 5087.69
Encroach Node=105695
       1 4980.91 5087.34
Encroach Node=105138
       1  4982.2 5039.76
Encroach Node=104708
       1 4864.14  5017.8
Encroach Node=104189
       1 4978.03 5130.19
Encroach Node=103731
       1  4981.9 5172.08
Encroach Node=103233
       1  4981.9 5022.18
Encroach Node=102582
       1 4967.51 5165.13
Encroach Node=102134
       1  4981.9  5018.1
Encroach Node=101694
       1  4981.7  5018.3
Encroach Node=101187
       1  4981.7  5018.3
Encroach Node=100538
       1  4976.3 5069.35
Encroach Node=100251
       1    4967    5018
Encroach Node=100180
       1  4984.8    5024
Encroach Node=99888
       1  4981.7 5180.38
Encroach Node=99198
       1  4981.7 5172.65
Encroach Node=98330
       1  4985.6 5320.27
Encroach Node=97637
       1 4969.07 5214.46
Encroach Node=97148
       1 4947.26 5123.42
Encroach Node=96713
       1  4979.4 5110.61
Encroach Node=96053
       1  4979.4 5105.82
Encroach Node=95689
       1  4921.5 5097.07
Encroach Node=95338
       1 4975.54 5140.76
Encroach Node=94699
       1  4979.4 5093.73
Encroach Node=94163
       1 4972.44 5081.42
Encroach Node=93714
       1 4976.09  5020.6
Encroach Node=93253
       1  4979.4    5018
Encroach Node=92711
       1 4943.09  5020.6
Encroach Node=92334
       1 4847.15  5020.6
Encroach Node=91954
       1  4979.4  5020.6
Encroach Node=91365
       1 4829.05  5034.3
Encroach Node=90832
       1  4904.3  5020.8
Encroach Node=90373
       1    4972    5028
Encroach Node=90288
       1    4972    5028
Encroach Node=89702
       1    4880 5185.35
Encroach Node=89407
       1 4971.92 5289.25
Encroach Node=88917
       1  4979.2  5107.6
Encroach Node=88575
       1  4987.8  5020.8
Encroach Node=88111
       1 4973.68  5020.8
Encroach Node=87570
       1    4955  5021.8
Encroach Node=87232
       1 4856.58  5021.8
Encroach Node=86880
       1 4776.21 5082.37
Encroach Node=86363
       1 4872.89  5021.8
Encroach Node=85673
       1  4978.2  5162.4
Encroach Node=85135
       1  4978.2 5121.16
Encroach Node=84568
       1  4977.9 5033.18
Encroach Node=83942
       1 4978.48 5049.47
Encroach Node=83479
       1    4973    5060
Encroach Node=83211
       1  4963.4    5037
Encroach Node=83144
       1    4971  5038.9
Encroach Node=82896
       1    4938  5018.5
Encroach Node=82582
       1  4961.5    5025
Encroach Node=82308
       1    4970  5022.1
Encroach Node=81923
       1  4977.9  5022.1
Encroach Node=81551
       1  4977.9  5022.1
Encroach Node=81046
       1  4972.5  5027.5
Encroach Node=80866
       1  4958.5  5041.5
Encroach Node=80700
       1  4958.5  5032.4
Encroach Node=80514
       1  4972.5  5027.5
Encroach Node=79939
       1  4972.5  5027.5
Encroach Node=79377
       1  4972.5  5027.5
Encroach Node=78770
       1  4972.5  5027.5
Encroach Node=78208
       1  4972.5    5026
Encroach Node=77675
       1  4972.5  5027.5
Encroach Node=77079
       1  4972.2  5027.8
Encroach Node=76500
       1    4965  5027.4
Encroach Node=75907
       1  4972.2  5027.8
Encroach Node=75420
       1 4858.72 5086.44
Encroach Node=75197
       1  4974.3  5027.8
Encroach Node=74750
       1  4974.9  5027.8
Encroach Node=74113
       1  4972.2  5027.8
Encroach Node=73766
       1 4965.03  5027.8
Encroach Node=73519
       1  4972.2  5027.8
Encroach Node=72982
       1  4971.1  5028.9
Encroach Node=72332
       1  4971.1  5025.3
Encroach Node=71760
       1  4971.1  5028.9
Encroach Node=71222
       1  4971.1  5028.9
Encroach Node=70594
       1  4971.1  5027.8
Encroach Node=70043
       1  4971.1  5028.9
Encroach Node=69344
       1  4969.5  5030.5
Encroach Node=69106
       1  4969.5  5030.5
Encroach Node=68459
       1 4966.44 5060.56
Encroach Node=67790
       1 4960.26 5182.48
Encroach Node=67171
       1 4957.68 5075.45
Encroach Node=66776
       1 4948.37  5030.5
Encroach Node=66438
       1  4925.2  5030.5
Encroach Node=65948
       1 4628.95  5030.5
Encroach Node=65609
       1 4772.93 5031.91
Encroach Node=65128
       1 4829.23 5032.88
Encroach Node=64696
       1 4895.43  5030.7
Encroach Node=64316
       1    4809 5102.06
Encroach Node=64019
       1 4964.84 5210.17
Encroach Node=63563
       1 4958.25 5145.99
Encroach Node=62996
       1  4969.3 5083.48
Encroach Node=62734
       1 4949.42 5049.48
Encroach Node=62618
       1    4900    5050
Encroach Node=62583
       1    4912  5046.5
Encroach Node=62400
       1  4944.8    5100
Encroach Node=62159
       1    4965    5034
Encroach Node=62032
       1  4967.5    5034
Encroach Node=61818
       1  4967.8    5050
Encroach Node=61156
       1  4968.4  5031.6
Encroach Node=60827
       1    4955    5068
Encroach Node=60586
       1  4968.4 5039.17
Encroach Node=60097
       1  4968.4  5031.6
Encroach Node=59726
       1 4966.06  5031.8
Encroach Node=59231
       1    4968    5032
Encroach Node=59032
       1    4957    5043
Encroach Node=58755
       1    4957    5043
Encroach Node=58565
       1    4968    5032
Encroach Node=58340
       1    4968 5035.46
Encroach Node=58010
       1    4968    5032
Encroach Node=57432
       1  4967.9  5032.1
Encroach Node=57068
       1  4967.9  5032.1
Encroach Node=56720
       1  4967.9  5032.1
Encroach Node=56086
       1  4967.9  5032.1
Encroach Node=55768
       1 4956.79 5028.87
Encroach Node=55258
       1  4967.9 5039.62
Encroach Node=54676
       1  4967.9  5032.1
Encroach Node=54070
       1 4925.98 5034.57
Encroach Node=53595
       1 4969.27    5036
Encroach Node=53272
       1  4969.1  5033.4
Encroach Node=53001
       1 4962.03 5046.36
Encroach Node=52360
       1 4952.27 5048.27
Encroach Node=51759
       1 4961.37 5083.98
Encroach Node=51152
       1 4958.44 5071.59
Encroach Node=50918
       1  4945.3  5054.7
Encroach Node=50706
       1  4966.7 5044.05
Encroach Node=50525
       1  4965.3  5034.7
Encroach Node=50202
       1  4965.3  5034.7
Encroach Node=49604
       1  4965.3  5032.8
Encroach Node=49092
       1  4965.3  5034.7
Encroach Node=48582
       1  4965.3  5034.7
Encroach Node=47974
       1  4965.1  5034.9
Encroach Node=47461
       1  4965.1  5034.9
Encroach Node=47104
       1  4965.1  5034.9
Encroach Node=46695
       1  4965.1  5034.9
Encroach Node=46610
       1  4959.5  5040.5
Encroach Node=46568
       1  4959.5  5039.4
Encroach Node=46149
       1  4965.1  5034.9
Encroach Node=45859
       1    4965    5035
Encroach Node=45356
       1    4965  5026.7
Encroach Node=45162
       1    4965    5035
Encroach Node=44619
       1    4965 5100.13
Encroach Node=44034
       1    4965    5035
Encroach Node=43542
       1    4965    5035
Encroach Node=43246
       1  4966.2    5035
Encroach Node=42957
       1    4965    5035
Encroach Node=42516
       1    4965    5035
Encroach Node=42061
       1  4966.2    5035
Encroach Node=41770
       1 4915.88 5048.27
Encroach Node=41532
       1 4949.79  5041.9
Encroach Node=41310
       1    4959    5041
Encroach Node=41271
       1    4959    5041
Encroach Node=41045
       1    4968  5037.1
Encroach Node=40567
       1  4962.9  5037.1
Encroach Node=40141
       1  4962.9  5037.1
Encroach Node=39478
       1  4968.3  5037.1
Encroach Node=38693
       1  4962.9  5037.1
Encroach Node=37906
       1  4962.9  5037.1
Encroach Node=37218
       1  4562.3 5043.82
Encroach Node=36582
       1 4692.67  5037.2
Encroach Node=36000
       1 4529.63 5038.13
Encroach Node=35604
       1  4962.6 5040.04
Encroach Node=35270
       1  4962.6  5037.4
Encroach Node=34664
       1  4969.2  5037.4
Encroach Node=34320
       1  4962.6  5037.4
Encroach Node=33881
       1  4962.6  5037.4
Encroach Node=33268
       1  4961.9  5038.1
Encroach Node=32922
       1  4961.9  5038.1
Encroach Node=32302
       1  4961.9  5038.1
Encroach Node=31780
       1  4961.9  5038.1
Encroach Node=31269
       1  4961.9  5038.1
Encroach Node=30773
       1  4961.3  5038.7
Encroach Node=30274
       1  4961.3  5038.7
Encroach Node=29883
       1  4961.3  5038.7
Encroach Node=29383
       1  4961.3  5038.7
Encroach Node=28974
       1  4961.3  5038.7
Encroach Node=28530
       1  4961.3  5038.7
Encroach Node=27980
       1  4961.3  5035.3
Encroach Node=27478
       1  4961.3  5038.7
Encroach Node=27035
       1  4961.3  5038.7
Encroach Node=26587
       1  4961.3  5038.7
Encroach Node=25985
       1  4960.7  5039.3
Encroach Node=25428
       1  4960.7  5039.3
Encroach Node=24914
       1  4960.7  5039.3
Encroach Node=24399
       1  4960.7  5039.3
Encroach Node=23992
       1  4960.7  5039.3
Encroach Node=23922
       1    4944  5049.5
Encroach Node=23880
       1    4944    5056
Encroach Node=23584
       1  4960.7  5039.3
Encroach Node=23417
       1  4960.7  5039.3
Encroach Node=23116
       1  4944.2 5065.69
Encroach Node=22676
       1 4952.72 5044.19
Encroach Node=22239
       1  4960.7  5039.3
Encroach Node=21774
       1 4948.11  5039.7
Encroach Node=21331
       1 4955.27  5039.7
Encroach Node=20863
       1  4960.3  5039.7
Encroach Node=20463
       1  4960.3  5039.7
Encroach Node=20008
       1  4960.3  5039.7
Encroach Node=19527
       1  4963.5  5039.7
Encroach Node=18911
       1  4960.3  5039.7
Encroach Node=18585
       1  4960.3  5039.7
Encroach Node=18214
       1  4960.3  5036.3
Encroach Node=18024
       1  4964.3  5039.8
Encroach Node=17577
       1  4960.2  5039.8
Encroach Node=17232
       1  4965.6  5039.8
Encroach Node=16723
       1  4960.2  5039.8
Encroach Node=16244
       1  4960.2  5039.8
Encroach Node=15881
       1  4960.2  5039.8
Encroach Node=15420
       1  4960.2  5039.8
Encroach Node=14804
       1 4483.08 5045.48
Encroach Node=14120
       1 4829.15 5043.85
Encroach Node=13507
       1 4902.35  5039.8
Encroach Node=13145
       1 4951.55  5382.6
Encroach Node=12753
       1 4786.78  5039.8
Encroach Node=12377
       1  4960.2  5039.8
Encroach Node=11731
       1  4959.9  5186.9
Encroach Node=11397
       1  4959.9 5289.86
Encroach Node=10984
       1  4959.9  5042.2
Encroach Node=10540
       1 4900.92  5040.1
Encroach Node=9967
       1 4584.05 5093.37
Encroach Node=9300
       1 4942.31  5754.2
Encroach Node=9085
       1  4959.9  5040.1
Encroach Node=8581
       1  4959.9  5040.1
Encroach Node=8001
       1  4959.9  5040.1
Encroach Node=7600
       1  4959.2  5040.8
Encroach Node=7062
       1  4959.2  5035.1
Encroach Node=6679
       1  4959.2  5040.8
Encroach Node=6342
       1  4959.2  5040.8
Encroach Node=5706
       1  4959.2  5040.8
Encroach Node=5419
       1    4945  5052.9
Encroach Node=5065
       1  4959.2 5141.45
Encroach Node=4705
       1  4945.2 5202.25
Encroach Node=4314
       1 4678.46 5117.23
Encroach Node=3931
       1 4571.64 5241.79
Encroach Node=3296
       1  4597.6    5045
Encroach Node=2793
       1    4787  5068.4
Encroach Node=2400
       1 4899.82 5101.09
Encroach Node=1862
       1  4930.9  5066.2
Encroach Node=1420
       1  4935.8  5043.6
Encroach Node=1354
       1    4924    5076
Encroach Node=1272
       1  4938.2    5076
Encroach Node=778
       1  4951.3  5051.7
Encroach Node=196
       1  4953.6  5051.1
BEGIN DESCRIPTION:
Floodway Run
END DESCRIPTION:
Computation Interval=1HOUR
Output Interval=1HOUR
Run HTab= 0
Run UNet= 0
Run PostProcess= 0
UNET Theta= 1
UNET Theta Warmup= 1
UNET ZTol= 0.02
UNET ZSATol= 0.05
UNET MxIter= 20
UNET MaxInSteps= 0
UNET DtIC= 0
UNET DtMin= 0
UNET MaxCRTS= 20
UNET WFStab= 2
UNET SFStab= 1
UNET WFX= 1
UNET SFX= 1
UNET DSS MLevel= 4
UNET DZMax Abort= 100
UNET Convert EG Bridges=-1
UNET Use Existing IB Tables=-1
UNET Froude Reduction=False
UNET Froude Limit= 1
UNET Froude Power= 10
Instantaneous Interval=1HOUR
Write IC File= 0
Echo Input=False
Echo Output=False
Write Detailed= 0
Detailed Automatic Start=False, 10

--- North Little Hunting Creek.f01 (steady flow) ---

Flow Title=Floodway
Number of Profiles=2
Profile Names=100-year,100-FW
River Rch & RM= North Little Hun,Reach-1,114557
    1192    1192
River Rch & RM= North Little Hun,Reach-1,112686
    1477    1477
River Rch & RM= North Little Hun,Reach-1,109374
    1635    1635
River Rch & RM= North Little Hun,Reach-1,107147
    2364    2364
River Rch & RM= North Little Hun,Reach-1,103731
    2478    2478
River Rch & RM= North Little Hun,Reach-1,101694
    2537    2537
River Rch & RM= North Little Hun,Reach-1,97637
    3050    3050
River Rch & RM= North Little Hun,Reach-1,97148
    3297    3297
River Rch & RM= North Little Hun,Reach-1,91365
    3376    3376
River Rch & RM= North Little Hun,Reach-1,87232
    3673    3673
River Rch & RM= North Little Hun,Reach-1,84568
    3753    3753
River Rch & RM= North Little Hun,Reach-1,81046
    5156    5156
River Rch & RM= North Little Hun,Reach-1,77079
    5226    5226
River Rch & RM= North Little Hun,Reach-1,72982
    5478    5478
River Rch & RM= North Little Hun,Reach-1,69106
    5932    5932
River Rch & RM= North Little Hun,Reach-1,65609
    5994    5994
River Rch & RM= North Little Hun,Reach-1,63563
    6020    6020
River Rch & RM= North Little Hun,Reach-1,62618
    6278    6278
River Rch & RM= North Little Hun,Reach-1,59726
    6344    6344
River Rch & RM= North Little Hun,Reach-1,59231
    6390    6390
River Rch & RM= North Little Hun,Reach-1,57432
    6422    6422
River Rch & RM= North Little Hun,Reach-1,53001
    6809    6809
River Rch & RM= North Little Hun,Reach-1,50706
    7168    7168
River Rch & RM= North Little Hun,Reach-1,47974
    7228    7228
River Rch & RM= North Little Hun,Reach-1,45859
    7257    7257
River Rch & RM= North Little Hun,Reach-1,41532
    7797    7797
River Rch & RM= North Little Hun,Reach-1,36582
    7827    7827
River Rch & RM= North Little Hun,Reach-1,36000
    7884    7884
River Rch & RM= North Little Hun,Reach-1,33268
    8078    8078
River Rch & RM= North Little Hun,Reach-1,30773
    8230    8230
River Rch & RM= North Little Hun,Reach-1,25985
    8360    8360
River Rch & RM= North Little Hun,Reach-1,21774
    8468    8468
River Rch & RM= North Little Hun,Reach-1,18024
    8510    8510
River Rch & RM= North Little Hun,Reach-1,11731
    8565    8565
River Rch & RM= North Little Hun,Reach-1,7600
    9047    9047
River Rch & RM= North Little Hun,Reach-1,2400
    9074    9074
Boundary for River Rch & Prof#=North Little Hun,Reach-1,1
Up Type=0
Dn Type=3
Dn Slope=0.0009
Boundary for River Rch & Prof#=North Little Hun,Reach-1,2
Up Type=0
Dn Type=3
Dn Slope=0.0009

--- North Little Hunting Creek.g01 (geometry) ---

Geom Title=Existing Conditions

River Reach=North Little Hun,Reach-1
Reach XY= 30
      1429442.75       875410.75      1433667.38       876152.06
      1434597.13       874854.75      1444873.63       873197.94
      1445673.75       871574.31      1447604.13       872027.25
      1447540.75       870697.63      1453384.64       868669.48
      1455259.75       863979.25      1458274.21       862495.64
      1457573.57       861172.36      1461997.38       859027.13
      1461096.75       858016.50      1466296.63       854083.00
      1467020.13       855697.13      1469623.16       850251.06
      1471483.25       851293.50      1474756.25       849764.69
      1474546.00       846961.06      1477517.88       847103.94
      1477100.38       841724.75      1475313.63       841308.44
      1476145.38       838847.94      1474968.80       838467.01
      1475392.00       837090.81      1477035.18       837448.78
      1475538.38       833585.81      1476763.35       833770.12
      1476169.88       831709.75      1477671.75       829781.63

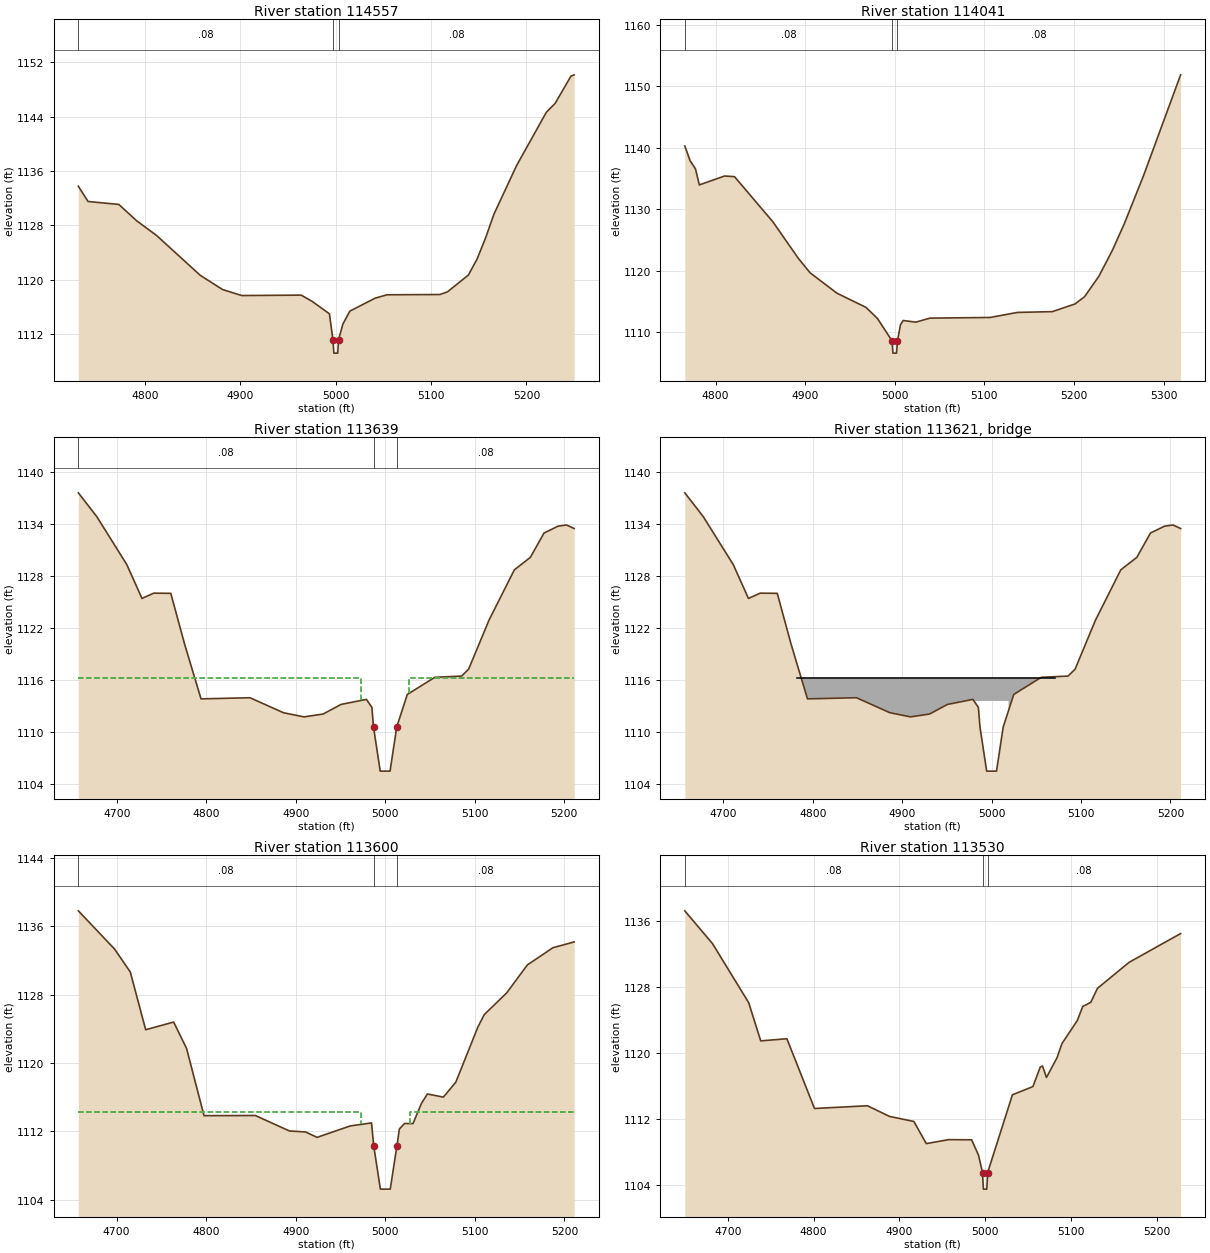
Type RM Length L Ch R = 1,114557,516,516,516
BEGIN DESCRIPTION:
North Hunting Creek 199.0
END DESCRIPTION:
XS GIS Cut Line= 4
      1429610.72       875683.14      1429614.86       875515.38
      1429596.22       875304.18      1429550.66       875171.63
#Sta/Elev= 30
  4730.0 1133.77  4740.2 1131.52  4772.5 1131.09  4791.3 1128.67  4812.1 1126.52
  4857.9 1120.66  4881.3 1118.57  4901.4 1117.69  4963.7 1117.75  4975.0 1116.85
  4993.3 1115.01  4997.0 1111.22  4998.0 1109.22  5002.0 1109.22  5003.0 1111.22
  5007.4 1113.47  5014.7 1115.39  5041.2 1117.30  5053.7 1117.80  5109.3 1117.84
  5117.2 1118.24  5139.1 1120.71  5148.1 1123.03  5157.0 1126.12  5165.8 1129.63
  5189.6 1136.80  5220.9 1144.66  5230.1 1145.96  5246.6 1149.95  5250.0 1150.15
#Mann=3,-1,0
  4730.0    0.08       0  4997.0    0.04       0  5003.0    0.08       0
Bank Sta=4997,5003
XS Rating Curve= 0
Exp/Cntr=0.3,0.1

Type RM Length L Ch R = 1,114041,402,402,402
BEGIN DESCRIPTION:
North Hunting Creek 198.0
END DESCRIPTION:
XS GIS Cut Line= 4
      1430118.02       875664.43      1430111.81       875509.17
      1430142.87       875213.07      1430173.93       875117.82
#Sta/Elev= 30
  4765.7 1140.32  4771.7 1137.89  4777.6 1136.59  4781.9 1133.97  4810.1 1135.42
  4821.2 1135.31  4863.9 1127.98  4892.3 1122.03  4905.5 1119.66  4935.5 1116.33
  4967.8 1114.03  4980.7 1112.21  4997.0 1108.57  4998.0 1106.57  5002.0 1106.57
  5003.0 1108.57  5006.4 1111.21  5009.4 1111.88  5023.5 1111.62  5039.3 1112.27
  5106.6 1112.38  5136.8 1113.20  5175.8 1113.33  5201.2 1114.58  5211.8 1115.76
  5227.8 1119.09  5242.9 1123.33  5256.0 1127.59  5277.7 1135.51  5319.0 1151.90
#Mann=3,-1,0
  4765.7    0.08       0  4997.0    0.04       0  5003.0    0.08       0
Bank Sta=4997,5003
XS Rating Curve= 0
Exp/Cntr=0.5,0.3

Type RM Length L Ch R = 1,113639,39,39,39
BEGIN DESCRIPTION:
Private Rd (2) - US
END DESCRIPTION:
XS GIS Cut Line= 4
      1430370.64       875776.30      1430511.45       875548.51
      1430518.47       875419.39      1430604.60       875287.65
#Sta/Elev= 30
  4656.9 1137.62  4677.5 1134.88  4711.1 1129.34  4728.1 1125.43  4741.2 1126.04
  4760.3 1126.02  4775.7 1120.18  4794.1 1113.84  4848.9 1113.97  4886.3 1112.24
  4909.4 1111.76  4930.7 1112.09  4950.7 1113.20  4979.1 1113.78  4985.2 1112.86
  4987.0 1110.60  4994.5 1105.50  5005.5 1105.50  5013.0 1110.60  5024.8 1114.35
  5055.6 1116.33  5085.5 1116.47  5093.4 1117.27  5116.2 1122.93  5144.5 1128.73
  5162.4 1130.17  5177.7 1132.98  5193.4 1133.77  5202.9 1133.91  5211.4 1133.50
#Mann=3,-1,0
  4656.9    0.08       0  4987.0    0.04       0  5013.0    0.08       0
#XS Ineff=2,0
    0.00 4973.00 1116.30 5027.00    0.00 1116.30
Permanent Ineff=
       F       F
Bank Sta=4987,5013
XS Rating Curve= 0
Exp/Cntr=0.5,0.3

Type RM Length L Ch R =3,113621,,,
BEGIN DESCRIPTION:
Private Rd (2) - TOR
Structure ID: LDS_NLHC_17
Approximate Survey Structure
END DESCRIPTION:
Bridge Culvert--1,0,-1,-1,0
Deck Dist Width WeirC Skew NumUp NumDn MinLoCord MaxHiCord MaxSubmerge Is_Ogee
8,20,3,,7,7,,,,0,1,1,,,
  4782.8  4981.0  4981.0  5019.0  5019.0  5038.3  5070.9
 1116.30 1116.30 1116.30 1116.30 1116.30 1116.30 1116.30
 1085.50 1085.50 1113.60 1113.60 1085.50 1085.50 1085.50
  4782.8  4981.0  4981.0  5019.0  5019.0  5038.3  5070.9
 1116.30 1116.30 1116.30 1116.30 1116.30 1116.30 1116.30
 1085.50 1085.50 1113.60 1113.60 1085.50 1085.50 1085.50
BR Coef=1,1,0,1.25,0,,,0.8,0,2,0,
WSPro=,,,, 1 ,,,, 0 ,,,, 0 ,,,,-1 ,-1 ,-1 , 0 , 0 , 0 , 0 , 0
BC Design=,,0,,0,,,,,,

Type RM Length L Ch R = 1,113600,70,70,70
BEGIN DESCRIPTION:
Private Rd (2) - DS
END DESCRIPTION:
XS GIS Cut Line= 4
      1430412.06       875794.92      1430544.58       875558.87
      1430556.31       875432.14      1430627.41       875293.81
#Sta/Elev= 30
  4657.3 1137.83  4697.8 1133.35  4715.3 1130.67  4732.5 1123.91  4763.7 1124.81
  4778.1 1121.73  4797.6 1113.85  4854.9 1113.87  4892.9 1112.06  4911.1 1111.94
  4923.8 1111.31  4960.9 1112.65  4984.6 1113.00  4987.0 1110.35  4994.5 1105.25
  5005.5 1105.25  5013.0 1110.35  5015.7 1112.29  5021.4 1112.93  5030.9 1112.92
  5040.3 1115.28  5047.0 1116.39  5064.8 1116.02  5078.7 1117.77  5103.3 1124.22
  5110.5 1125.69  5135.3 1128.20  5158.6 1131.50  5187.1 1133.51  5210.8 1134.19
#Mann=3,-1,0
  4657.3    0.08       0  4987.0    0.04       0  5013.0    0.08       0
#XS Ineff=2,0
    0.00 4973.00 1114.30 5027.00    0.00 1114.30
Permanent Ineff=
       F       F
Bank Sta=4987,5013
XS Rating Curve= 0
Exp/Cntr=0.5,0.3

Type RM Length L Ch R = 1,113530,319,319,319
BEGIN DESCRIPTION:
North Hunting Creek 197.0
END DESCRIPTION:
XS GIS Cut Line= 4
      1430507.30       875840.49      1430571.50       875699.67
      1430633.62       875442.91      1430635.69       875283.45
#Sta/Elev= 30
  4649.7 1137.23  4682.1 1133.25  4724.2 1126.12  4738.3 1121.49  4768.8 1121.75
  4801.0 1113.31  4862.8 1113.64  4888.5 1112.35  4916.9 1111.74  4931.4 1109.06
  4957.6 1109.54  4984.3 1109.52  4992.3 1107.67  4997.0 1105.55  4998.0 1103.55
  5002.0 1103.55  5003.0 1105.55  5031.9 1114.97  5055.8 1115.96  5064.4 1118.33
  5067.0 1118.45  5071.6 1117.06  5083.9 1119.45  5089.7 1121.17  5107.5 1123.94
  5113.9 1125.65  5123.3 1126.16  5131.1 1127.85  5167.9 1130.99  5228.1 1134.48
#Mann=3,-1,0
  4649.7    0.08       0  4997.0    0.04       0  5003.0    0.08       0
Bank Sta=4997,5003
XS Rating Curve= 0
Exp/Cntr=0.5,0.3

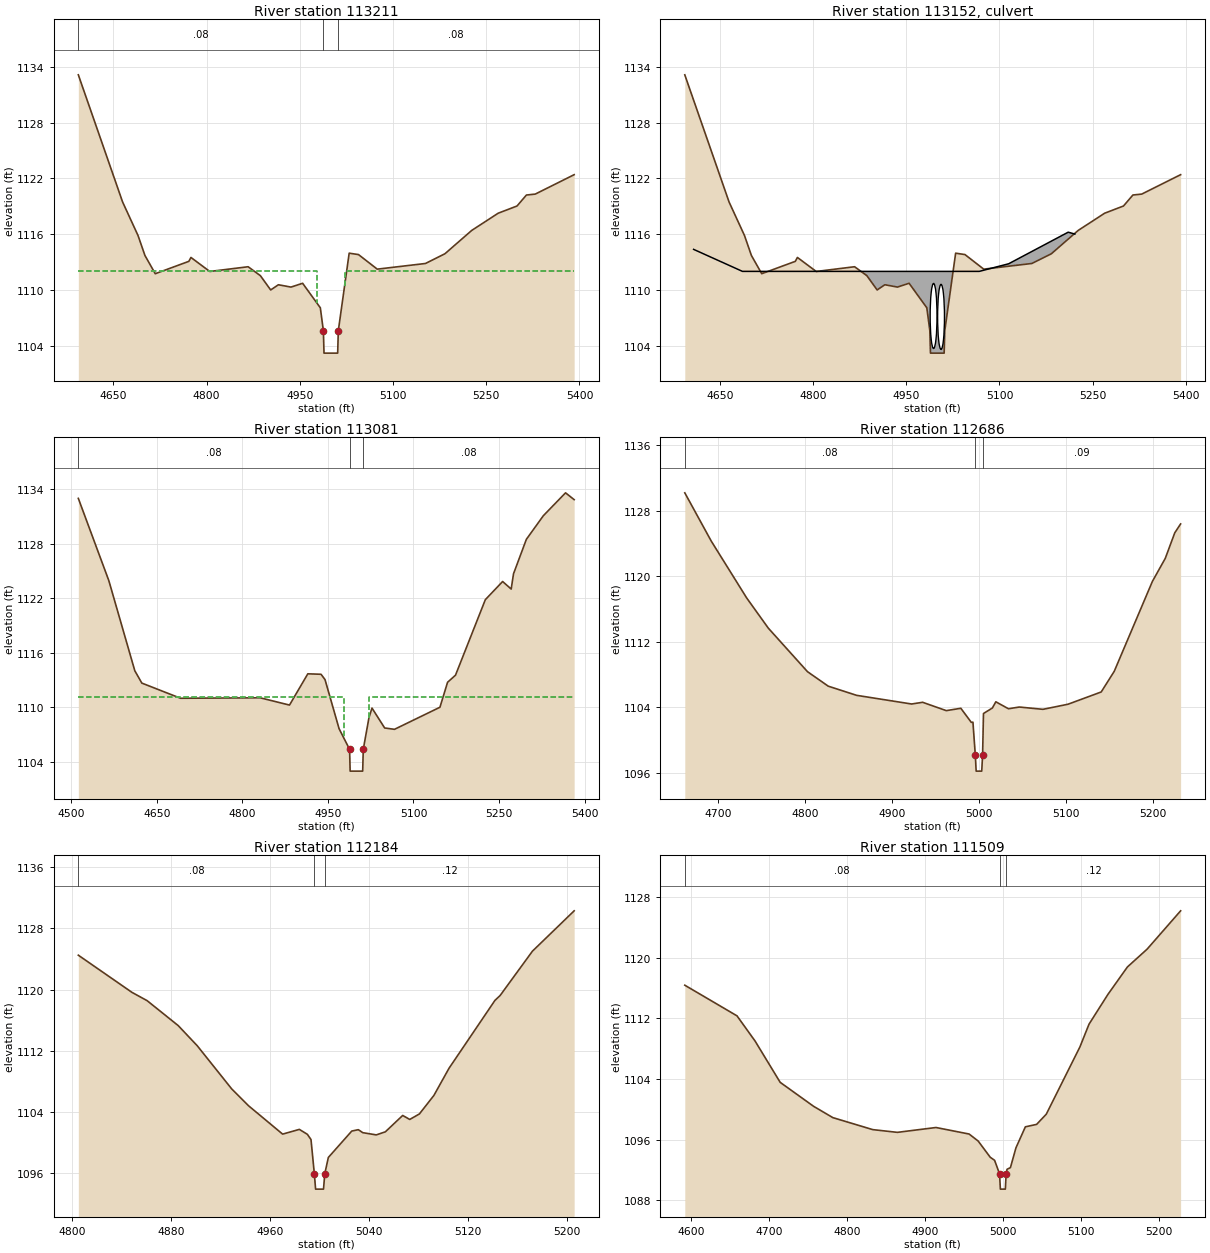
Type RM Length L Ch R = 1,113211,130,130,130
BEGIN DESCRIPTION:
Clingman Rd - US
END DESCRIPTION:
XS GIS Cut Line= 4
      1430831.84       875971.94      1430918.09       875908.28
      1430920.14       875587.99      1431049.49       875241.00
#Sta/Elev= 30
  4593.7 1133.16  4665.0 1119.46  4689.7 1115.87  4700.9 1113.71  4717.5 1111.75
  4771.5 1113.08  4774.9 1113.50  4805.2 1111.99  4866.9 1112.50  4886.6 1111.54
  4903.2 1110.00  4915.6 1110.56  4935.9 1110.31  4954.6 1110.72  4983.1 1108.08
  4988.0 1105.60  4989.0 1103.20  5011.0 1103.20  5012.0 1105.60  5029.5 1113.96
  5044.5 1113.81  5074.7 1112.24  5152.2 1112.85  5183.6 1113.90  5226.7 1116.41
  5269.2 1118.26  5299.6 1119.04  5314.7 1120.22  5328.9 1120.32  5391.5 1122.41
#Mann=3,-1,0
  4593.7    0.08       0  4988.0    0.04       0  5012.0    0.08       0
#XS Ineff=2,0
    0.00 4978.00 1112.00 5022.00    0.00 1112.00
Permanent Ineff=
       F       F
Bank Sta=4988,5012
XS Rating Curve= 0
Exp/Cntr=0.5,0.3

Type RM Length L Ch R =2,113152,,,
BEGIN DESCRIPTION:
Clingman Rd - TOR
Structure ID: LDS_NLHC_16
Approximate Survey Structure
END DESCRIPTION:
Bridge Culvert--1,0,-1,-1,0
Deck Dist Width WeirC Skew NumUp NumDn MinLoCord MaxHiCord MaxSubmerge Is_Ogee
38,42,3,,6,6,,,,0,1,1,,,
  4607.9  4686.5  5067.5  5114.8  5210.6  5221.3
 1114.37 1112.00 1112.00 1112.82 1116.22 1116.02
 1083.20 1083.20 1083.20 1083.20 1083.20 1083.20
  4607.9  4686.5  5067.5  5114.8  5210.6  5221.3
 1114.37 1112.00 1112.00 1112.82 1116.22 1116.02
 1082.99 1082.99 1082.99 1082.99 1082.99 1082.99
Culvert=4,7,11,42,0.013,0.5,1,29,1,1103.7,4994,1102.99,4994,Culvert #1,0,38
Culvert Bottom n=0.013
Culvert Bottom Depth=0
Culvert Depth Blocked=0
Culvert=4,7,11,42,0.013,0.5,1,29,1,1103.6,5006,1102.99,5006,Culvert #2,0,38
Culvert Bottom n=0.013
Culvert Bottom Depth=0
Culvert Depth Blocked=0
BC Design=,,0,,0,,,,,,

Type RM Length L Ch R = 1,113081,395,395,395
BEGIN DESCRIPTION:
Clingman Rd - DS
END DESCRIPTION:
XS GIS Cut Line= 4
      1430889.37       876064.30      1431002.27       876000.67
      1431059.75       875509.97      1431145.97       875280.06
#Sta/Elev= 30
  4512.5 1133.01  4566.0 1123.95  4611.5 1114.04  4623.8 1112.68  4691.7 1111.01
  4831.3 1111.06  4882.7 1110.26  4914.8 1113.70  4938.0 1113.65  4945.0 1113.06
  4969.6 1107.66  4988.0 1105.39  4989.0 1102.99  5011.0 1102.99  5012.0 1105.39
  5022.0 1108.87  5027.3 1109.93  5049.5 1107.74  5066.7 1107.59  5146.4 1110.02
  5159.8 1112.77  5173.7 1113.55  5226.0 1121.86  5256.3 1123.86  5271.3 1123.03
  5275.4 1124.71  5297.9 1128.50  5327.7 1131.10  5366.6 1133.62  5381.7 1132.87
#Mann=3,-1,0
  4512.5    0.08       0  4988.0    0.04       0  5012.0    0.08       0
#XS Ineff=2,0
    0.00 4978.00 1111.10 5022.00    0.00 1111.10
Permanent Ineff=
       F       F
Bank Sta=4988,5012
XS Rating Curve= 0
Exp/Cntr=0.5,0.3

Type RM Length L Ch R = 1,112686,502,502,502
BEGIN DESCRIPTION:
North Hunting Creek 196.0
END DESCRIPTION:
XS GIS Cut Line= 4
      1431360.41       876157.28      1431319.00       876018.55
      1431420.46       875701.74      1431468.08       875623.06
#Sta/Elev= 30
  4662.2 1130.21  4692.6 1124.31  4733.3 1117.36  4758.1 1113.68  4803.1 1108.36
  4826.9 1106.59  4859.5 1105.47  4922.7 1104.41  4935.3 1104.62  4962.5 1103.60
  4979.2 1103.89  4991.2 1102.17  4993.1 1102.19  4995.8 1098.21  4996.8 1096.21
  5003.2 1096.21  5004.2 1098.21  5005.2 1103.25  5015.4 1103.92  5019.4 1104.68
  5033.9 1103.83  5046.4 1104.04  5073.5 1103.76  5102.2 1104.38  5140.4 1105.88
  5155.4 1108.41  5199.2 1119.39  5214.0 1122.21  5224.9 1125.33  5231.6 1126.41
#Mann=3,-1,0
  4662.2    0.08       0  4995.8    0.04       0  5004.2    0.09       0
Bank Sta=4995.8,5004.2
XS Rating Curve= 0
Exp/Cntr=0.3,0.1

Type RM Length L Ch R = 1,112184,675,675,675
BEGIN DESCRIPTION:
North Hunting Creek 195.0
END DESCRIPTION:
XS GIS Cut Line= 4
      1431809.75       876146.89      1431836.66       876006.13
      1431838.73       875904.67      1431832.52       875749.38
#Sta/Elev= 30
  4805.3 1124.50  4848.6 1119.64  4860.8 1118.56  4885.9 1115.30  4901.3 1112.66
  4929.1 1107.02  4942.6 1104.83  4970.2 1101.11  4983.7 1101.73  4990.2 1101.08
  4993.1 1100.40  4995.8 1095.92  4996.8 1093.92  5003.2 1093.92  5004.2 1095.92
  5007.1 1098.06  5026.0 1101.51  5031.3 1101.69  5034.9 1101.30  5045.8 1101.01
  5053.1 1101.41  5067.1 1103.55  5072.8 1103.03  5080.6 1103.75  5092.3 1106.17
  5104.5 1109.72  5141.6 1118.60  5145.7 1119.22  5171.8 1125.02  5205.5 1130.30
#Mann=3,-1,0
  4805.3    0.08       0  4995.8    0.04       0  5004.2    0.12       0
Bank Sta=4995.8,5004.2
XS Rating Curve= 0
Exp/Cntr=0.3,0.1

Type RM Length L Ch R = 1,111509,494,494,494
BEGIN DESCRIPTION:
North Hunting Creek 194.0
END DESCRIPTION:
XS GIS Cut Line= 4
      1432567.61       876097.26      1432509.62       875948.15
      1432399.88       875685.18      1432335.68       875505.02
#Sta/Elev= 30
  4591.9 1116.35  4658.9 1112.31  4682.1 1108.99  4714.3 1103.55  4757.2 1100.39
  4781.9 1098.90  4833.1 1097.32  4864.7 1096.96  4914.2 1097.60  4956.7 1096.74
  4968.3 1095.82  4983.9 1093.67  4989.4 1093.28  4995.8 1091.48  4996.8 1089.48
  5003.2 1089.48  5004.2 1091.48  5004.7 1091.48  5005.3 1092.09  5009.7 1092.31
  5016.8 1094.92  5028.9 1097.69  5043.3 1098.01  5055.7 1099.35  5098.9 1108.22
  5110.6 1111.22  5134.7 1115.12  5159.8 1118.75  5185.1 1121.10  5228.1 1126.15
#Mann=3,-1,0
  4591.9    0.08       0  4995.8    0.04       0  5004.2    0.12       0
Bank Sta=4995.8,5004.2
XS Rating Curve= 0
Exp/Cntr=0.3,0.1

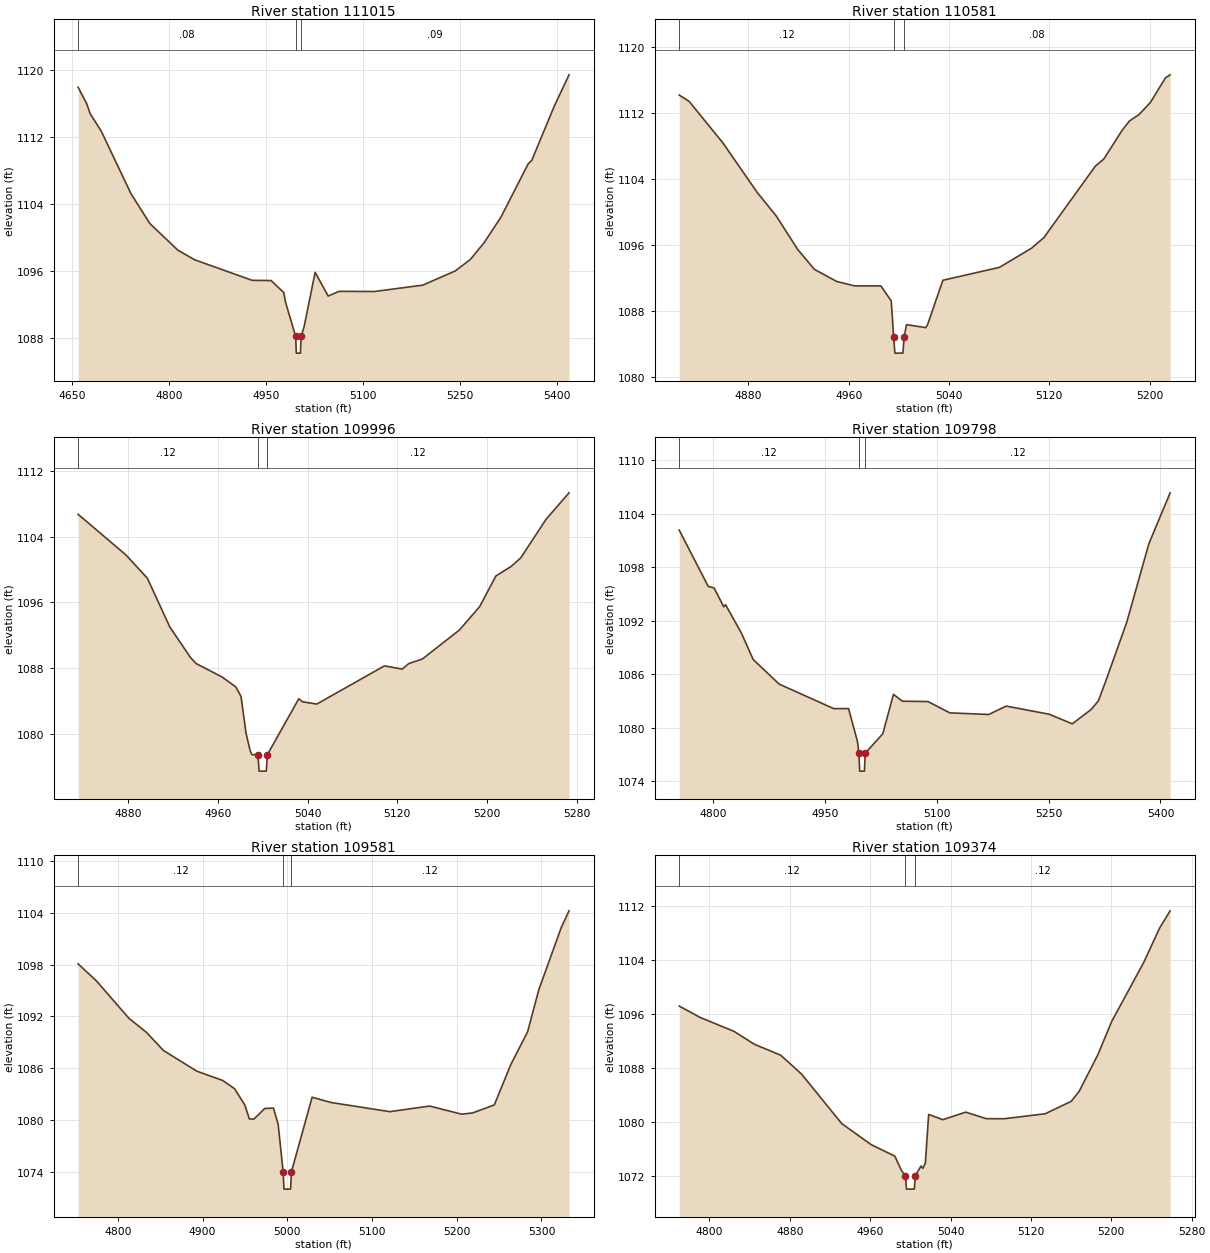
Type RM Length L Ch R = 1,111015,434,434,434
BEGIN DESCRIPTION:
North Hunting Creek 193.0
END DESCRIPTION:
XS GIS Cut Line= 4
      1433018.99       875941.92      1432905.12       875743.16
      1432787.09       875411.85      1432677.34       875271.04
#Sta/Elev= 30
  4659.3 1117.97  4672.3 1116.06  4678.1 1114.79  4695.1 1112.72  4741.0 1105.24
  4770.3 1101.65  4813.8 1098.45  4839.9 1097.30  4928.5 1094.85  4957.8 1094.82
  4977.5 1093.38  4980.1 1092.24  4995.8 1088.13  4996.8 1086.13  5003.2 1086.13
  5004.2 1088.13  5008.8 1089.27  5025.9 1095.80  5046.1 1092.97  5063.2 1093.53
  5117.4 1093.51  5192.3 1094.27  5242.6 1095.97  5265.9 1097.34  5287.4 1099.37
  5313.2 1102.40  5355.3 1108.78  5361.0 1109.22  5396.0 1115.75  5418.6 1119.46
#Mann=3,-1,0
  4659.3    0.08       0  4995.8    0.04       0  5004.2    0.09       0
Bank Sta=4995.8,5004.2
XS Rating Curve= 0
Exp/Cntr=0.3,0.1

Type RM Length L Ch R = 1,110581,585,585,585
BEGIN DESCRIPTION:
North Hunting Creek 192.0
END DESCRIPTION:
XS GIS Cut Line= 4
      1433263.34       875707.95      1433267.48       875587.86
      1433275.76       875444.98      1433275.76       875316.56
#Sta/Elev= 30
  4824.7 1114.22  4832.6 1113.46  4859.6 1108.42  4887.0 1102.41  4902.2 1099.56
  4919.0 1095.57  4932.5 1093.11  4950.3 1091.64  4964.5 1091.10  4985.6 1091.10
  4993.9 1089.27  4995.8 1084.95  4996.8 1082.95  5003.2 1082.95  5004.2 1084.95
  5006.1 1086.40  5021.4 1086.04  5022.8 1086.36  5035.1 1091.78  5080.2 1093.34
  5105.8 1095.66  5115.7 1096.95  5156.7 1105.60  5163.5 1106.47  5178.3 1109.99
  5183.9 1111.07  5191.6 1111.86  5200.6 1113.31  5212.7 1116.31  5216.4 1116.67
#Mann=3,-1,0
  4824.7    0.12       0  4995.8    0.04       0  5004.2    0.08       0
Bank Sta=4995.8,5004.2
XS Rating Curve= 0
Exp/Cntr=0.3,0.1

Type RM Length L Ch R = 1,109996,198,198,198
BEGIN DESCRIPTION:
North Hunting Creek 191.0
END DESCRIPTION:
XS GIS Cut Line= 4
      1433369.31       875933.33      1433503.09       875944.35
      1433578.66       875941.20      1433704.38       875751.44
#Sta/Elev= 30
  4835.5 1106.71  4878.2 1101.76  4897.2 1098.95  4917.3 1093.01  4935.7 1089.31
  4940.6 1088.59  4963.8 1086.95  4976.1 1085.74  4980.7 1084.59  4985.2 1080.10
  4988.8 1078.03  4990.4 1077.52  4995.8 1077.52  4996.8 1075.52  5003.2 1075.52
  5004.2 1077.52  5032.2 1084.31  5035.5 1083.94  5048.2 1083.66  5108.5 1088.30
  5124.3 1087.91  5130.1 1088.57  5142.4 1089.14  5175.3 1092.65  5193.4 1095.50
  5207.8 1099.21  5221.4 1100.37  5230.0 1101.42  5252.6 1106.11  5273.0 1109.31
#Mann=3,-1,0
  4835.5    0.12       0  4995.8    0.04       0  5004.2    0.12       0
Bank Sta=4995.8,5004.2
XS Rating Curve= 0
Exp/Cntr=0.3,0.1

Type RM Length L Ch R = 1,109798,217,217,217
BEGIN DESCRIPTION:
North Little Hunting Creek 190.5
END DESCRIPTION:
XS GIS Cut Line= 4
      1433349.43       876142.34      1433557.42       876156.48
      1433729.07       875934.34      1433708.88       875766.76
#Sta/Elev= 30
  4754.9 1102.19  4793.9 1095.86  4801.7 1095.69  4814.6 1093.58  4817.0 1093.82
  4838.2 1090.64  4854.0 1087.67  4888.9 1084.90  4962.2 1082.14  4981.9 1082.15
  4993.8 1078.48  4995.8 1077.13  4996.8 1075.13  5003.2 1075.13  5004.2 1077.13
  5027.8 1079.32  5042.1 1083.75  5054.1 1082.98  5088.4 1082.94  5117.6 1081.67
  5169.9 1081.49  5193.2 1082.43  5250.7 1081.52  5281.8 1080.44  5306.9 1082.04
  5316.6 1082.99  5326.0 1085.09  5354.7 1091.82  5384.4 1100.65  5412.9 1106.37
#Mann=3,-1,0
  4754.9    0.12       0  4995.8    0.04       0  5004.2    0.12       0
Bank Sta=4995.8,5004.2
XS Rating Curve= 0
Exp/Cntr=0.3,0.1

Type RM Length L Ch R = 1,109581,207,207,207
BEGIN DESCRIPTION:
North Little Hunting Creek 190.4
END DESCRIPTION:
XS GIS Cut Line= 4
      1433900.73       876309.97      1433801.77       876190.81
      1433739.17       875942.42      1433723.02       875774.84
#Sta/Elev= 30
  4753.1 1098.08  4774.9 1096.09  4813.1 1091.78  4833.7 1090.16  4853.8 1088.06
  4893.3 1085.66  4923.8 1084.59  4937.8 1083.63  4949.9 1081.75  4955.2 1080.14
  4960.6 1080.12  4973.4 1081.35  4983.7 1081.39  4989.2 1079.54  4995.1 1074.02
  4996.1 1072.02  5003.9 1072.02  5004.9 1074.02  5029.3 1082.65  5051.6 1082.04
  5121.0 1080.98  5168.0 1081.63  5205.7 1080.69  5218.7 1080.83  5244.3 1081.76
  5263.8 1086.43  5283.6 1090.21  5296.8 1095.07  5323.3 1102.27  5332.5 1104.21
#Mann=3,-1,0
  4753.1    0.12       0  4995.1    0.04       0  5004.9    0.12       0
#XS Ineff=2,0
       0                 5029.30    0.00 1082.65
Permanent Ineff=
       F       F
Bank Sta=4995.1,5004.9
XS Rating Curve= 0
Exp/Cntr=0.3,0.1

Type RM Length L Ch R = 1,109374,260,260,260
BEGIN DESCRIPTION:
North Hunting Creek 190.0
END DESCRIPTION:
XS GIS Cut Line= 4
      1434012.83       876122.21      1433908.95       875986.85
      1433757.82       875864.06      1433749.94       875741.06
#Sta/Elev= 30
  4769.9 1097.19  4790.7 1095.50  4824.4 1093.44  4844.7 1091.52  4870.9 1089.90
  4891.6 1087.11  4931.7 1079.75  4960.9 1076.64  4984.5 1074.92  4991.4 1072.71
  4995.1 1072.03  4996.1 1070.03  5003.9 1070.03  5004.9 1072.03  5010.6 1073.46
  5012.4 1073.10  5014.9 1073.87  5018.2 1081.11  5032.3 1080.33  5055.1 1081.45
  5075.6 1080.48  5093.4 1080.47  5134.2 1081.21  5160.1 1083.06  5168.0 1084.54
  5186.6 1089.97  5200.5 1094.94  5232.2 1103.64  5248.0 1108.74  5258.5 1111.31
#Mann=3,-1,0
  4769.9    0.12       0  4995.1    0.04       0  5004.9    0.12       0
#XS Ineff=2,0
       0                 5018.20    0.00 1081.11
Permanent Ineff=
       F       F
Bank Sta=4995.1,5004.9
XS Rating Curve= 0
Exp/Cntr=0.3,0.1