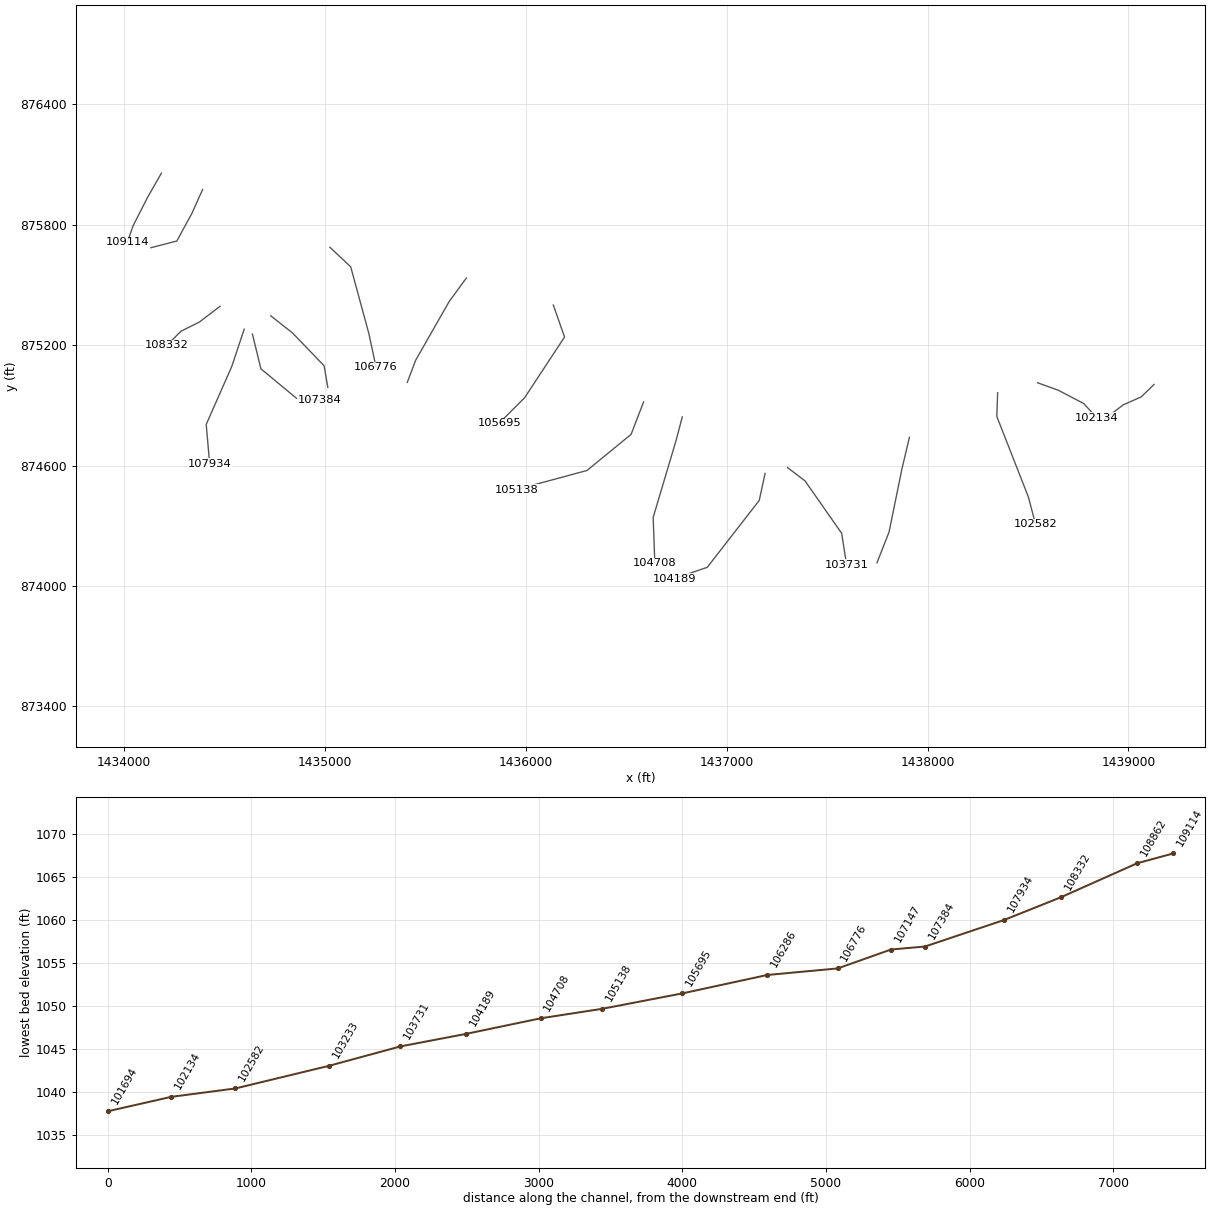
HEC-RAS study North Little Hunting Creek.prj: North Little Hunting Creek Limited Detail Study

--- North Little Hunting Creek.g01 (geometry) --- (continued)

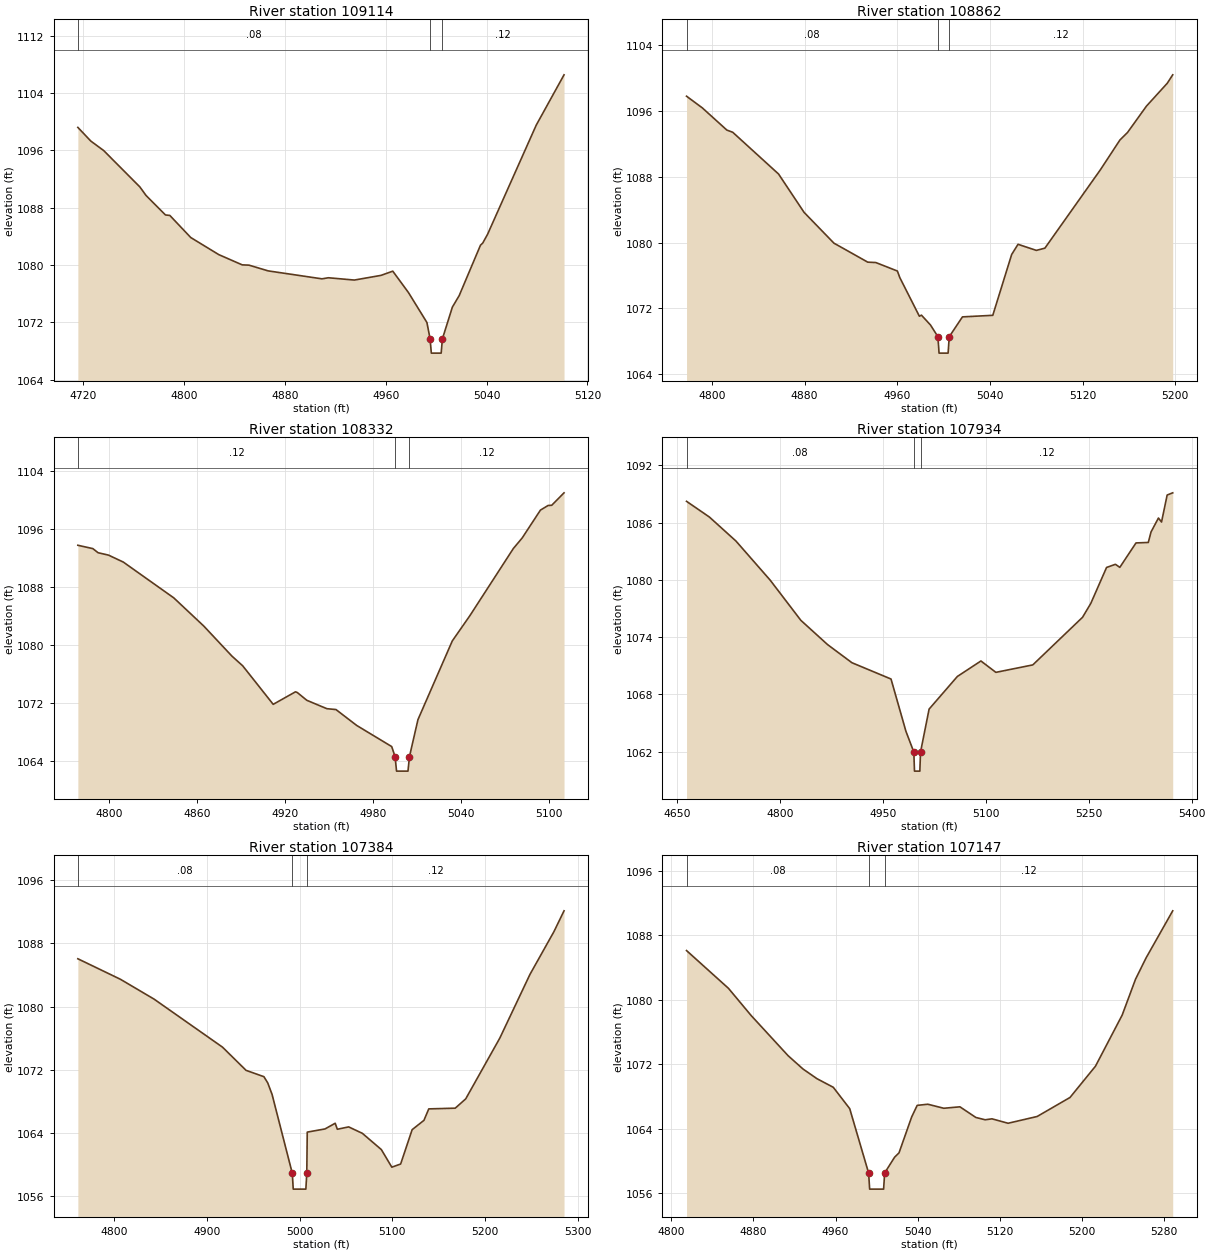
Type RM Length L Ch R = 1,109114,252,252,252
BEGIN DESCRIPTION:
North Little Hunting Creek 189.5
END DESCRIPTION:
XS GIS Cut Line= 4
      1434186.84       876056.47      1434117.80       875935.65
      1434046.08       875794.87      1434016.86       875711.18
#Sta/Elev= 30
  4715.6 1099.19  4725.9 1097.28  4736.1 1095.96  4764.8 1090.89  4769.7 1089.70
  4785.1 1086.98  4788.6 1086.91  4805.2 1083.83  4827.4 1081.45  4846.0 1080.02
  4851.4 1079.98  4866.6 1079.18  4909.3 1078.07  4914.4 1078.22  4935.0 1077.90
  4956.1 1078.55  4965.5 1079.14  4977.9 1076.17  4992.6 1071.98  4995.1 1069.71
  4996.1 1067.71  5003.9 1067.71  5004.9 1069.71  5012.8 1074.13  5018.2 1075.73
  5035.1 1082.76  5036.9 1083.06  5040.8 1084.31  5079.3 1099.49  5101.4 1106.52
#Mann=3,-1,0
  4715.6    0.08       0  4995.1    0.04       0  5004.9    0.12       0
Bank Sta=4995.1,5004.9
XS Rating Curve= 0
Exp/Cntr=0.3,0.1

Type RM Length L Ch R = 1,108862,530,530,530
BEGIN DESCRIPTION:
North Hunting Creek 189.0
END DESCRIPTION:
XS GIS Cut Line= 4
      1434391.84       875975.07      1434338.00       875854.97
      1434263.46       875718.31      1434135.06       875685.17
#Sta/Elev= 30
  4778.0 1097.83  4791.7 1096.40  4812.8 1093.71  4817.9 1093.44  4857.5 1088.36
  4879.5 1083.70  4905.3 1079.95  4934.5 1077.64  4941.5 1077.59  4960.1 1076.56
  4962.2 1075.76  4979.1 1071.06  4980.9 1071.19  4988.7 1069.99  4995.1 1068.57
  4996.1 1066.57  5003.9 1066.57  5004.9 1068.57  5016.3 1070.98  5042.5 1071.17
  5058.8 1078.57  5064.3 1079.81  5080.1 1079.07  5087.5 1079.34  5135.5 1088.89
  5152.3 1092.50  5158.9 1093.42  5175.2 1096.62  5193.1 1099.39  5197.9 1100.43
#Mann=3,-1,0
  4778.0    0.08       0  4995.1    0.04       0  5004.9    0.12       0
Bank Sta=4995.1,5004.9
XS Rating Curve= 0
Exp/Cntr=0.3,0.1

Type RM Length L Ch R = 1,108332,398,398,398
BEGIN DESCRIPTION:
North Hunting Creek 188.0
END DESCRIPTION:
XS GIS Cut Line= 4
      1434478.80       875393.21      1434375.27       875314.53
      1434284.17       875268.98      1434213.73       875198.55
#Sta/Elev= 30
  4778.8 1093.80  4789.0 1093.34  4792.6 1092.77  4799.7 1092.44  4809.8 1091.48
  4844.2 1086.54  4864.7 1082.64  4883.8 1078.51  4891.2 1077.16  4912.0 1071.84
  4927.2 1073.57  4928.5 1073.46  4934.9 1072.40  4948.6 1071.24  4954.8 1071.12
  4968.9 1068.93  4992.8 1066.01  4995.1 1064.62  4996.1 1062.62  5003.9 1062.62
  5004.9 1064.62  5010.7 1069.73  5034.1 1080.59  5046.1 1084.08  5075.8 1093.37
  5081.7 1094.79  5094.2 1098.65  5099.4 1099.29  5101.9 1099.32  5110.3 1101.04
#Mann=3,-1,0
  4778.8    0.12       0  4995.1    0.04       0  5004.9    0.12       0
#XS Ineff=2,0
    0.00 4927.20 1073.57               0
Permanent Ineff=
       F       F
Bank Sta=4995.1,5004.9
XS Rating Curve= 0
Exp/Cntr=0.3,0.1

Type RM Length L Ch R = 1,107934,550,550,550
BEGIN DESCRIPTION:
North Hunting Creek 187.0
END DESCRIPTION:
XS GIS Cut Line= 4
      1434598.91       875279.35      1434536.79       875092.97
      1434409.79       874804.53      1434427.04       874608.41
#Sta/Elev= 30
  4663.9 1088.23  4697.1 1086.59  4735.9 1084.07  4785.8 1079.97  4830.5 1075.76
  4869.4 1073.22  4904.9 1071.32  4961.9 1069.61  4983.6 1064.14  4995.1 1061.96
  4996.1 1059.96  5003.9 1059.96  5004.9 1061.96  5017.4 1066.46  5058.6 1069.88
  5092.9 1071.50  5114.7 1070.31  5168.5 1071.09  5241.0 1076.08  5253.0 1077.53
  5276.0 1081.30  5288.9 1081.63  5295.3 1081.31  5318.9 1083.87  5336.8 1083.92
  5340.8 1085.02  5351.6 1086.48  5356.1 1086.06  5364.3 1088.89  5372.4 1089.12
#Mann=3,-1,0
  4663.9    0.08       0  4995.1    0.04       0  5004.9    0.12       0
#XS Ineff=2,0
       0                 5092.90    0.00 1071.50
Permanent Ineff=
       F       F
Bank Sta=4995.1,5004.9
XS Rating Curve= 0
Exp/Cntr=0.3,0.1

Type RM Length L Ch R = 1,107384,237,237,237
BEGIN DESCRIPTION:
North Hunting Creek 186.5
END DESCRIPTION:
XS GIS Cut Line= 4
      1434639.93       875254.77      1434682.00       875081.80
      1434859.66       874934.54      1434974.21       874925.18
#Sta/Elev= 30
  4761.2 1086.05  4807.1 1083.45  4843.3 1080.94  4917.0 1074.86  4942.4 1071.92
  4961.6 1071.12  4965.7 1070.34  4970.4 1068.88  4992.2 1058.88  4993.2 1056.88
  5006.8 1056.88  5007.8 1058.88  5008.3 1064.10  5027.4 1064.50  5038.4 1065.22
  5040.7 1064.46  5052.9 1064.76  5067.6 1063.95  5088.1 1061.89  5099.4 1059.66
  5108.9 1060.06  5121.3 1064.41  5134.0 1065.59  5139.2 1067.04  5167.7 1067.13
  5179.0 1068.31  5215.7 1076.00  5248.2 1084.07  5274.0 1089.48  5284.9 1092.12
#Mann=3,-1,0
  4761.2    0.08       0  4992.2    0.04       0  5007.8    0.12       0
Bank Sta=4992.2,5007.8
XS Rating Curve= 0
Exp/Cntr=0.3,0.1

Type RM Length L Ch R = 1,107147,371,371,371
BEGIN DESCRIPTION:
North Hunting Creek 186.0
END DESCRIPTION:
XS GIS Cut Line= 4
      1434731.44       875345.58      1434839.10       875260.69
      1434996.47       875097.11      1435015.11       874989.40
#Sta/Elev= 30
  4814.9 1086.12  4855.7 1081.44  4877.7 1078.08  4913.8 1073.08  4928.3 1071.43
  4941.9 1070.23  4957.8 1069.16  4973.8 1066.51  4992.2 1058.53  4993.2 1056.53
  5006.8 1056.53  5007.8 1058.53  5017.5 1060.49  5021.8 1061.03  5034.1 1065.48
  5039.5 1066.92  5049.9 1067.06  5065.4 1066.56  5081.1 1066.74  5096.6 1065.42
  5105.7 1065.13  5112.3 1065.25  5128.0 1064.70  5156.3 1065.54  5188.3 1067.90
  5213.1 1071.78  5239.1 1078.12  5252.1 1082.57  5262.4 1085.22  5288.3 1091.05
#Mann=3,-1,0
  4814.9    0.08       0  4992.2    0.04       0  5007.8    0.12       0
Bank Sta=4992.2,5007.8
XS Rating Curve= 0
Exp/Cntr=0.3,0.1

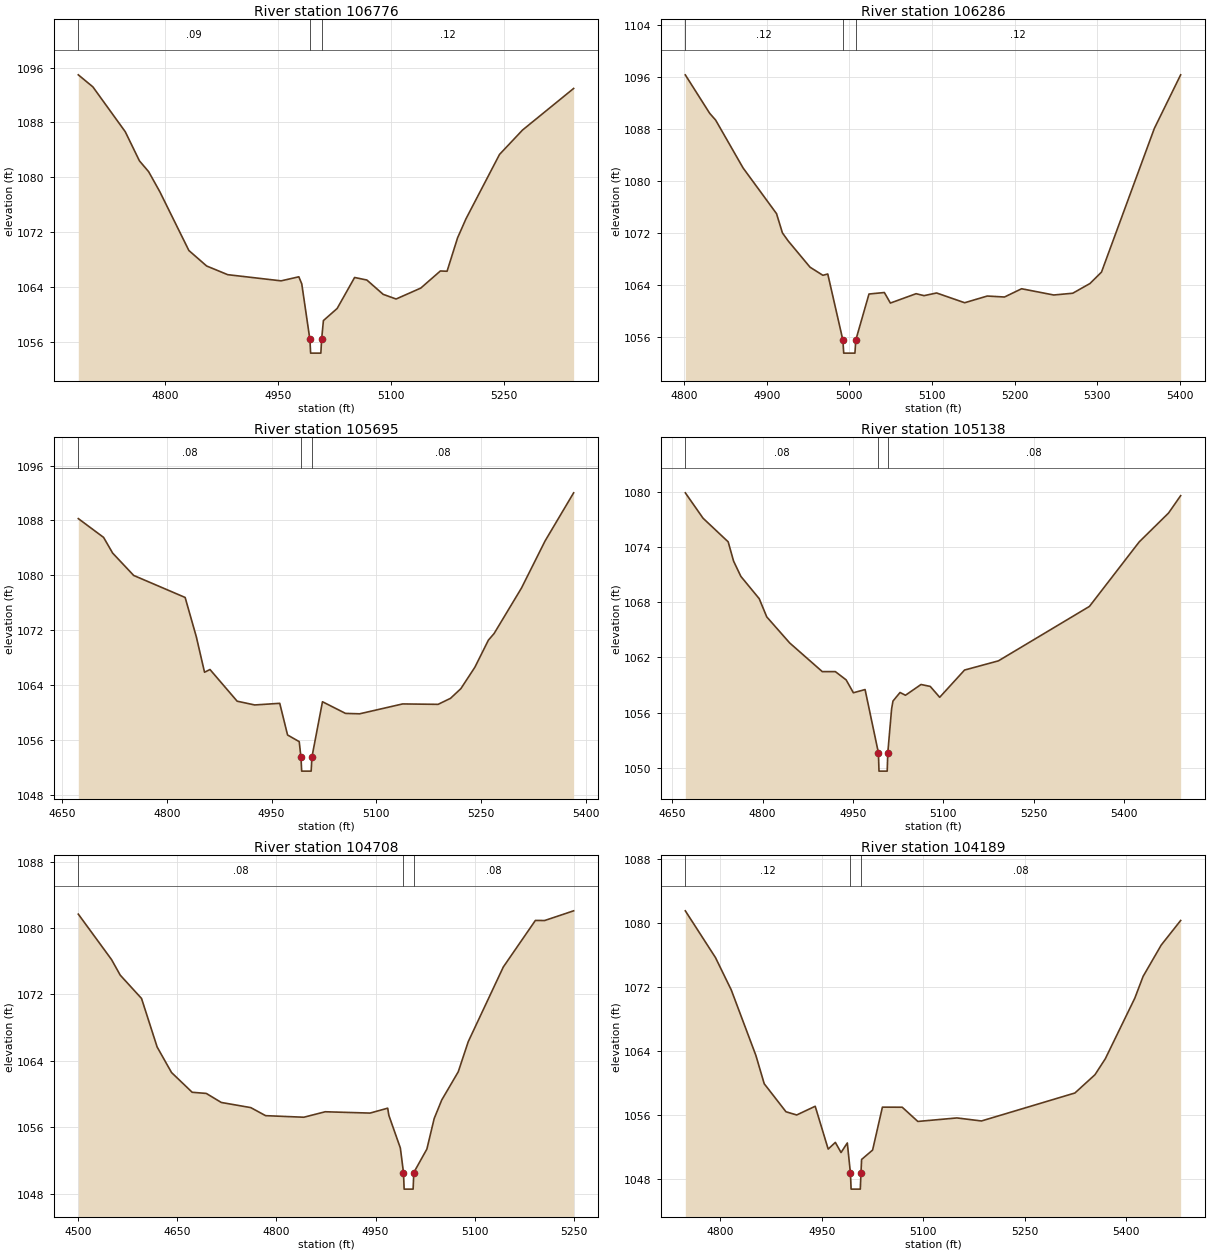
Type RM Length L Ch R = 1,106776,490,490,490
BEGIN DESCRIPTION:
North Hunting Creek 185.0
END DESCRIPTION:
XS GIS Cut Line= 4
      1435025.46       875687.24      1435128.99       875589.93
      1435220.10       875254.48      1435255.29       875088.86
#Sta/Elev= 30
  4684.1 1094.95  4703.5 1093.19  4746.6 1086.64  4765.4 1082.40  4777.7 1080.81
  4792.6 1077.88  4831.2 1069.31  4854.8 1067.05  4882.9 1065.78  4953.9 1064.88
  4977.5 1065.47  4981.4 1064.44  4992.2 1056.33  4993.2 1054.33  5006.8 1054.33
  5007.8 1056.33  5010.2 1059.08  5028.5 1060.85  5051.7 1065.37  5068.0 1065.00
  5089.7 1062.91  5106.9 1062.23  5139.7 1063.82  5165.8 1066.32  5174.7 1066.28
  5188.7 1071.16  5199.9 1073.94  5244.5 1083.33  5275.1 1086.89  5343.1 1092.96
#Mann=3,-1,0
  4684.1    0.09       0  4992.2    0.04       0  5007.8    0.12       0
Bank Sta=4992.2,5007.8
XS Rating Curve= 0
Exp/Cntr=0.3,0.1

Type RM Length L Ch R = 1,106286,591,591,591
BEGIN DESCRIPTION:
North Hunting Creek 184.0
END DESCRIPTION:
XS GIS Cut Line= 4
      1435704.61       875533.99      1435619.73       875418.06
      1435452.01       875124.03      1435410.59       875014.27
#Sta/Elev= 30
  4801.5 1096.36  4831.0 1090.45  4838.2 1089.41  4871.4 1082.05  4911.9 1075.02
  4919.0 1072.07  4925.9 1070.84  4952.5 1066.78  4968.0 1065.54  4973.9 1065.74
  4992.2 1055.57  4993.2 1053.57  5006.8 1053.57  5007.8 1055.57  5023.8 1062.66
  5042.4 1062.89  5049.7 1061.27  5080.8 1062.71  5090.4 1062.41  5105.6 1062.82
  5139.6 1061.32  5167.0 1062.35  5187.8 1062.20  5208.5 1063.47  5247.4 1062.51
  5270.4 1062.78  5291.3 1064.28  5305.2 1066.03  5369.1 1088.11  5401.0 1096.37
#Mann=3,-1,0
  4801.5    0.12       0  4992.2    0.04       0  5007.8    0.12       0
Bank Sta=4992.2,5007.8
XS Rating Curve= 0
Exp/Cntr=0.3,0.1

Type RM Length L Ch R = 1,105695,557,557,557
BEGIN DESCRIPTION:
North Hunting Creek 183.0
END DESCRIPTION:
XS GIS Cut Line= 4
      1436137.38       875399.46      1436193.30       875239.99
      1435994.52       874937.67      1435868.24       874811.39
#Sta/Elev= 30
  4673.3 1088.26  4709.5 1085.52  4722.5 1083.23  4752.6 1079.97  4826.3 1076.76
  4842.3 1071.03  4854.1 1065.85  4861.9 1066.25  4900.8 1061.63  4926.0 1061.08
  4961.8 1061.32  4973.0 1056.70  4989.7 1055.73  4992.2 1053.43  4993.2 1051.43
  5006.8 1051.43  5007.8 1053.43  5023.0 1061.55  5056.0 1059.85  5076.2 1059.79
  5137.8 1061.23  5188.6 1061.17  5206.4 1062.05  5221.2 1063.46  5241.3 1066.59
  5260.6 1070.53  5268.8 1071.50  5308.1 1078.15  5341.8 1085.00  5382.7 1092.02
#Mann=3,-1,0
  4673.3    0.08       0  4992.2    0.04       0  5007.8    0.08       0
Bank Sta=4992.2,5007.8
XS Rating Curve= 0
Exp/Cntr=0.3,0.1

Type RM Length L Ch R = 1,105138,430,430,430
BEGIN DESCRIPTION:
North Hunting Creek 182.0
END DESCRIPTION:
XS GIS Cut Line= 4
      1436586.73       874916.99      1436524.61       874755.46
      1436305.12       874575.31      1435953.09       874480.06
#Sta/Elev= 30
  4671.9 1079.90  4701.3 1077.14  4743.0 1074.57  4752.0 1072.47  4764.1 1070.81
  4794.5 1068.39  4807.0 1066.41  4845.0 1063.58  4899.1 1060.46  4920.8 1060.46
  4938.7 1059.56  4950.7 1058.16  4970.1 1058.51  4992.2 1051.64  4993.2 1049.64
  5006.8 1049.64  5007.8 1051.64  5014.1 1056.40  5016.4 1057.26  5028.1 1058.19
  5037.1 1057.89  5062.9 1059.06  5078.2 1058.85  5093.9 1057.67  5135.1 1060.63
  5191.3 1061.63  5342.3 1067.55  5424.8 1074.56  5473.5 1077.70  5493.6 1079.59
#Mann=3,-1,0
  4671.9    0.08       0  4992.2    0.04       0  5007.8    0.08       0
Bank Sta=4992.2,5007.8
XS Rating Curve= 0
Exp/Cntr=0.3,0.1

Type RM Length L Ch R = 1,104708,519,519,519
BEGIN DESCRIPTION:
North Hunting Creek 181.0
END DESCRIPTION:
XS GIS Cut Line= 4
      1436779.30       874842.45      1436748.24       874724.40
      1436634.35       874341.33      1436642.63       874113.59
#Sta/Elev= 30
  4500.1 1081.69  4550.4 1076.21  4563.5 1074.34  4595.8 1071.52  4619.4 1065.67
  4641.2 1062.59  4672.4 1060.21  4693.8 1060.07  4716.5 1058.98  4761.1 1058.36
  4783.5 1057.39  4841.4 1057.20  4873.8 1057.86  4941.6 1057.70  4968.3 1058.29
  4970.1 1057.42  4987.5 1053.48  4992.2 1050.53  4993.2 1048.53  5006.8 1048.53
  5007.8 1050.53  5027.6 1053.36  5038.7 1057.05  5050.1 1059.28  5075.1 1062.68
  5090.2 1066.31  5143.3 1075.32  5191.8 1080.93  5205.8 1080.92  5249.7 1082.09
#Mann=3,-1,0
  4500.1    0.08       0  4992.2    0.04       0  5007.8    0.08       0
Bank Sta=4992.2,5007.8
XS Rating Curve= 0
Exp/Cntr=0.3,0.1

Type RM Length L Ch R = 1,104189,458,458,458
BEGIN DESCRIPTION:
North Hunting Creek 180.0
END DESCRIPTION:
XS GIS Cut Line= 4
      1437191.36       874560.82      1437162.37       874426.22
      1436903.53       874092.85      1436739.96       874036.95
#Sta/Elev= 30
  4748.0 1081.55  4792.6 1075.70  4815.9 1071.66  4852.3 1063.47  4864.7 1059.91
  4896.9 1056.40  4912.7 1056.00  4940.1 1057.09  4959.3 1051.73  4969.9 1052.57
  4978.3 1051.30  4987.6 1052.50  4992.2 1048.72  4993.2 1046.72  5006.8 1046.72
  5007.8 1048.72  5008.7 1050.43  5025.0 1051.61  5039.5 1056.98  5068.8 1056.97
  5091.9 1055.19  5149.7 1055.63  5186.0 1055.25  5324.2 1058.75  5353.9 1061.04
  5369.2 1063.04  5412.8 1070.62  5425.1 1073.35  5451.9 1077.27  5480.6 1080.34
#Mann=3,-1,0
  4748.0    0.12       0  4992.2    0.04       0  5007.8    0.08       0
Bank Sta=4992.2,5007.8
XS Rating Curve= 0
Exp/Cntr=0.3,0.1

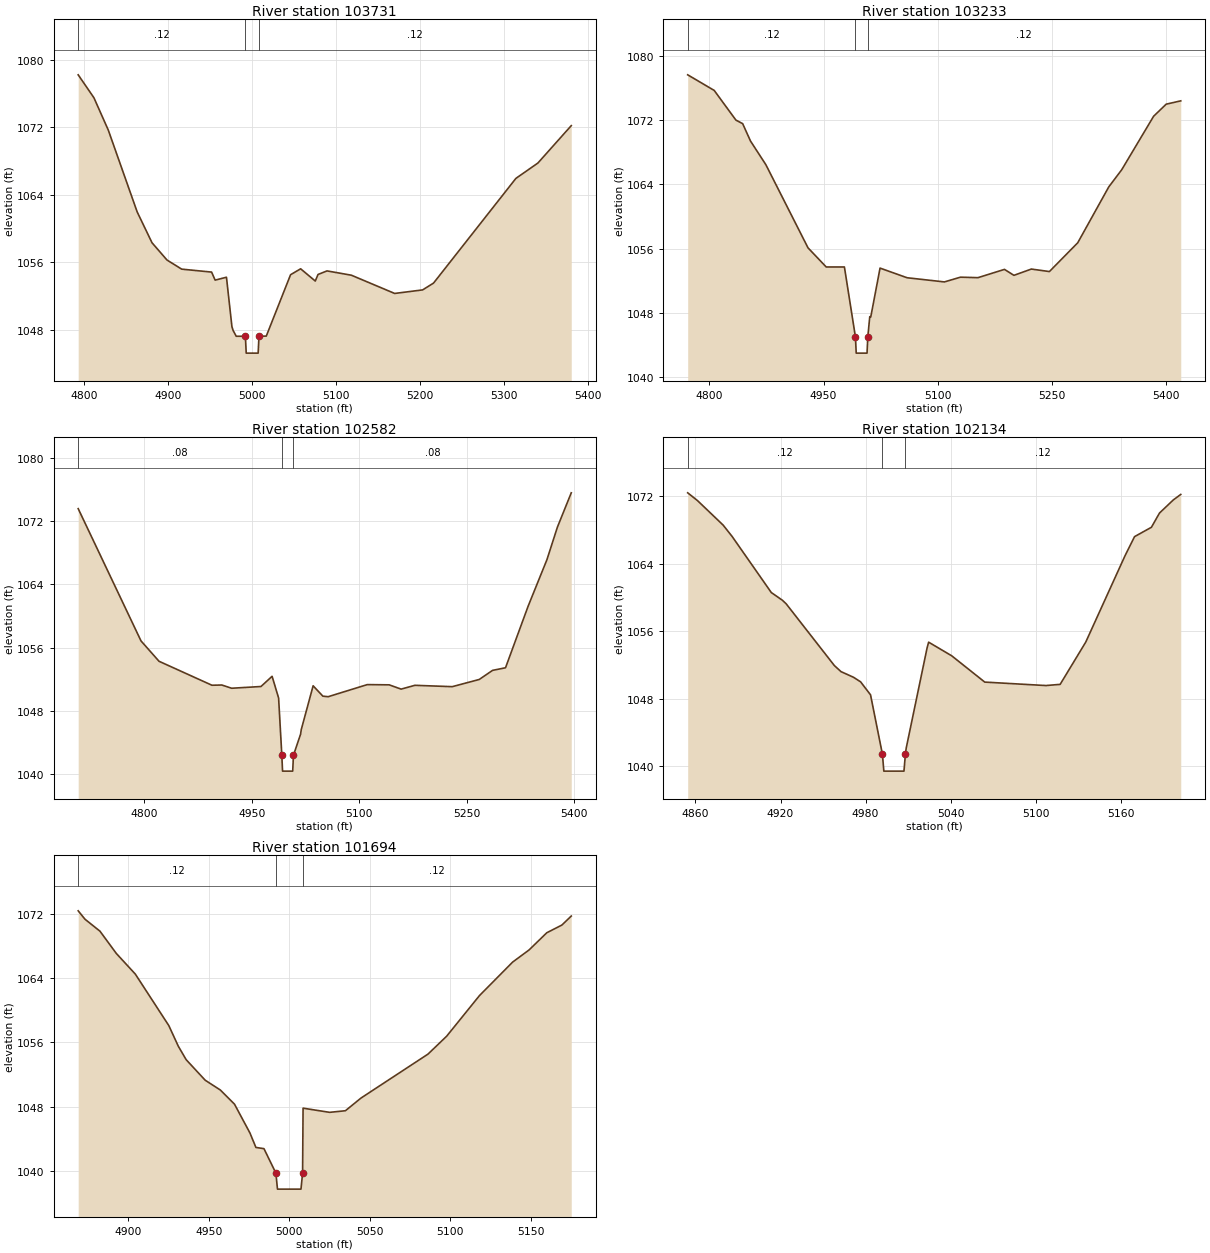
Type RM Length L Ch R = 1,103731,498,498,498
BEGIN DESCRIPTION:
North Hunting Creek 179.0
END DESCRIPTION:
XS GIS Cut Line= 4
      1437303.18       874589.80      1437390.14       874523.54
      1437572.35       874262.64      1437597.21       874105.25
#Sta/Elev= 30
  4792.9 1078.23  4811.6 1075.52  4828.7 1071.69  4863.1 1061.99  4880.8 1058.33
  4898.6 1056.29  4916.1 1055.21  4951.7 1054.86  4955.9 1053.91  4969.4 1054.25
  4975.9 1048.39  4977.3 1047.95  4981.0 1047.26  4991.9 1047.26  4992.9 1045.26
  5007.1 1045.26  5008.1 1047.26  5016.8 1047.28  5045.7 1054.55  5057.7 1055.25
  5075.1 1053.80  5078.4 1054.58  5089.1 1055.00  5118.1 1054.49  5169.6 1052.33
  5202.9 1052.75  5215.9 1053.56  5313.9 1065.96  5340.1 1067.78  5379.8 1072.21
#Mann=3,-1,0
  4792.9    0.12       0  4991.9    0.04       0  5008.1    0.12       0
Bank Sta=4991.9,5008.1
XS Rating Curve= 0
Exp/Cntr=0.3,0.1

Type RM Length L Ch R = 1,103233,651,651,651
BEGIN DESCRIPTION:
North Hunting Creek 178.0
END DESCRIPTION:
XS GIS Cut Line= 4
      1437909.87       874740.94      1437872.60       874583.59
      1437808.41       874268.85      1437748.36       874115.62
#Sta/Elev= 30
  4771.6 1077.63  4806.4 1075.69  4834.9 1072.00  4843.8 1071.55  4854.1 1069.39
  4874.3 1066.44  4929.6 1056.10  4953.5 1053.72  4977.4 1053.72  4991.9 1045.00
  4992.9 1043.00  5007.1 1043.00  5008.1 1045.00  5010.7 1047.54  5012.0 1047.50
  5024.2 1053.58  5059.7 1052.38  5108.7 1051.86  5129.8 1052.45  5152.8 1052.39
  5187.6 1053.42  5200.0 1052.68  5222.9 1053.46  5246.6 1053.15  5283.8 1056.73
  5324.6 1063.69  5341.5 1065.81  5383.5 1072.48  5400.0 1073.98  5419.1 1074.39
#Mann=3,-1,0
  4771.6    0.12       0  4991.9    0.04       0  5008.1    0.12       0
Bank Sta=4991.9,5008.1
XS Rating Curve= 0
Exp/Cntr=0.3,0.1

Type RM Length L Ch R = 1,102582,448,448,448
BEGIN DESCRIPTION:
North Hunting Creek 177.0
END DESCRIPTION:
XS GIS Cut Line= 4
      1438348.85       874962.50      1438344.71       874844.49
      1438502.07       874442.79      1438537.27       874308.23
#Sta/Elev= 30
  4707.5 1073.56  4795.2 1056.84  4820.4 1054.26  4894.3 1051.23  4908.1 1051.26
  4921.8 1050.85  4962.8 1051.07  4978.3 1052.36  4987.4 1049.61  4991.9 1042.37
  4992.9 1040.37  5007.1 1040.37  5008.1 1042.37  5018.1 1045.04  5019.0 1045.61
  5035.6 1051.16  5049.2 1049.85  5056.6 1049.78  5111.2 1051.31  5141.8 1051.28
  5158.5 1050.74  5177.7 1051.22  5229.9 1051.05  5267.6 1051.96  5286.2 1053.11
  5304.3 1053.44  5335.9 1061.23  5362.1 1067.10  5376.8 1071.23  5396.1 1075.56
#Mann=3,-1,0
  4707.5    0.08       0  4991.9    0.04       0  5008.1    0.08       0
Bank Sta=4991.9,5008.1
XS Rating Curve= 0
Exp/Cntr=0.3,0.1

Type RM Length L Ch R = 1,102134,440,440,440
BEGIN DESCRIPTION:
North Hunting Creek 176.0
END DESCRIPTION:
XS GIS Cut Line= 4
      1438547.62       875012.22      1438651.16       874974.95
      1438777.47       874908.68      1438841.63       874838.32
#Sta/Elev= 30
  4854.5 1072.43  4861.4 1071.51  4879.5 1068.60  4885.8 1067.26  4913.5 1060.59
  4921.3 1059.68  4924.0 1059.25  4958.0 1051.92  4962.7 1051.20  4971.4 1050.54
  4976.5 1049.99  4983.5 1048.45  4991.9 1041.39  4992.9 1039.39  5007.1 1039.39
  5008.1 1041.39  5008.7 1042.14  5023.4 1054.01  5024.5 1054.70  5040.8 1053.08
  5064.1 1049.96  5107.2 1049.55  5117.3 1049.69  5135.4 1054.72  5163.1 1064.97
  5169.8 1067.23  5181.7 1068.34  5187.4 1070.03  5197.1 1071.58  5202.4 1072.24
#Mann=3,-1,0
  4854.5    0.12       0  4991.9    0.04       0  5008.1    0.12       0
Bank Sta=4991.9,5008.1
XS Rating Curve= 0
Exp/Cntr=0.3,0.1

Type RM Length L Ch R = 1,101694,507,507,507
BEGIN DESCRIPTION:
North Hunting Creek 175.0
END DESCRIPTION:
XS GIS Cut Line= 4
      1439127.43       875003.95      1439063.22       874941.81
      1438974.18       874902.47      1438879.00       874830.05
#Sta/Elev= 30
  4868.9 1072.37  4873.1 1071.33  4882.4 1069.84  4892.6 1067.06  4904.4 1064.49
  4925.2 1058.08  4931.1 1055.51  4936.0 1053.83  4947.8 1051.28  4957.2 1050.06
  4966.0 1048.30  4975.6 1044.71  4979.3 1042.91  4984.3 1042.76  4991.7 1039.72
  4992.7 1037.72  5007.3 1037.72  5008.3 1039.72  5008.6 1047.80  5025.1 1047.28
  5034.9 1047.48  5044.6 1049.06  5086.2 1054.53  5097.8 1056.76  5118.2 1061.82
  5138.8 1065.99  5149.0 1067.50  5160.0 1069.64  5169.4 1070.60  5175.2 1071.72
#Mann=3,-1,0
  4868.9    0.12       0  4991.7    0.04       0  5008.3    0.12       0
Bank Sta=4991.7,5008.3
XS Rating Curve= 0
Exp/Cntr=0.3,0.1