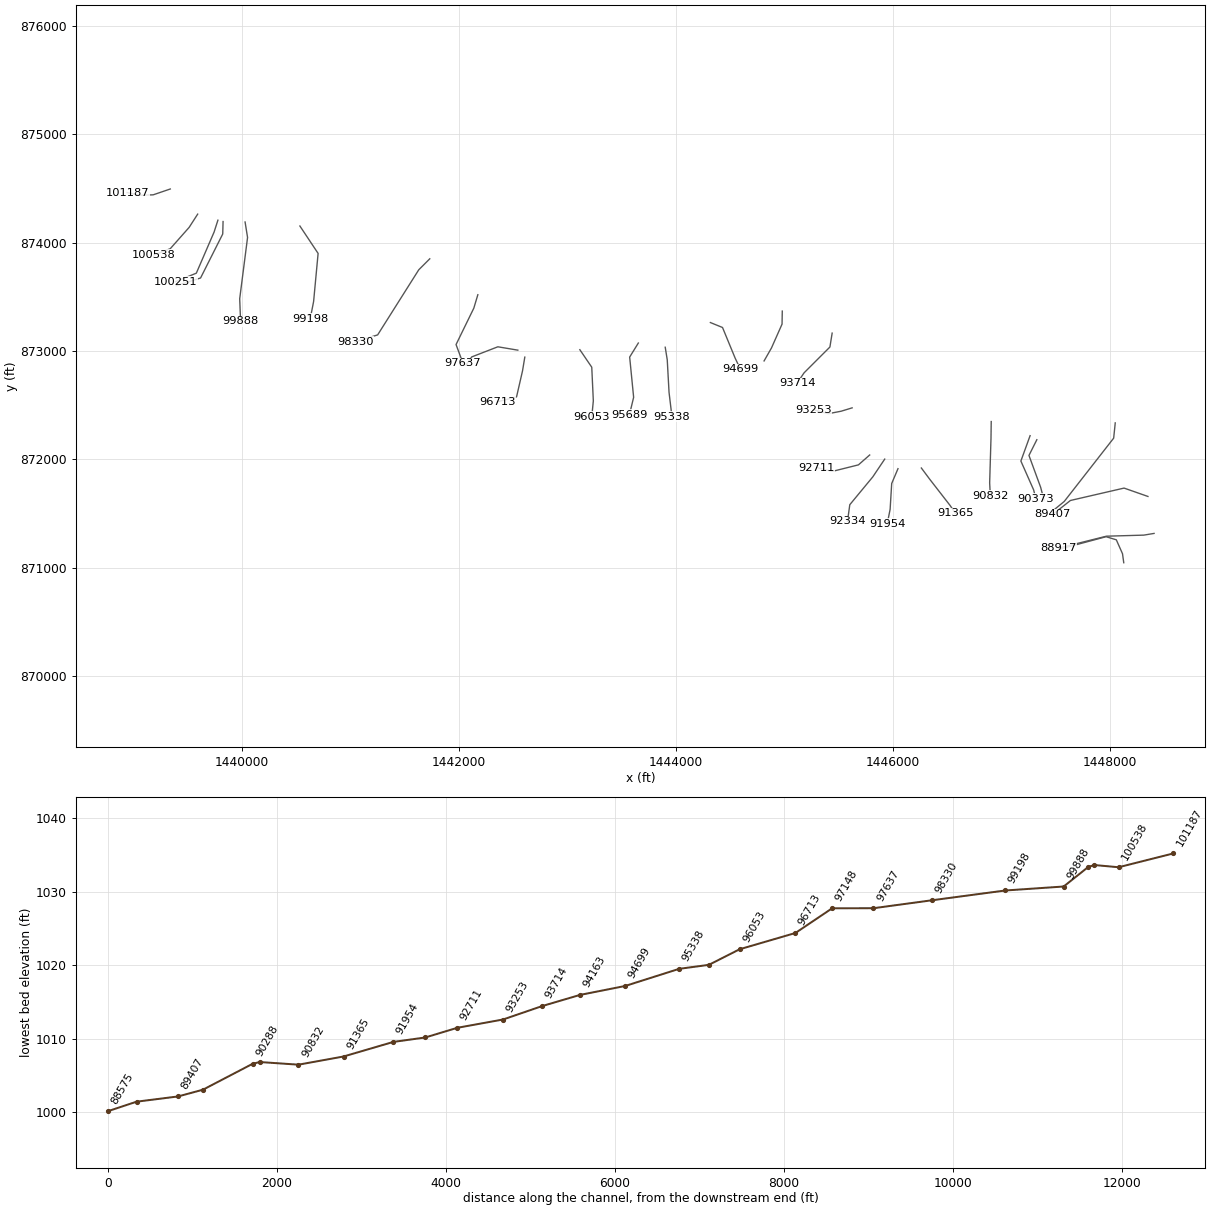
HEC-RAS study North Little Hunting Creek.prj: North Little Hunting Creek Limited Detail Study

--- North Little Hunting Creek.g01 (geometry) --- (continued)

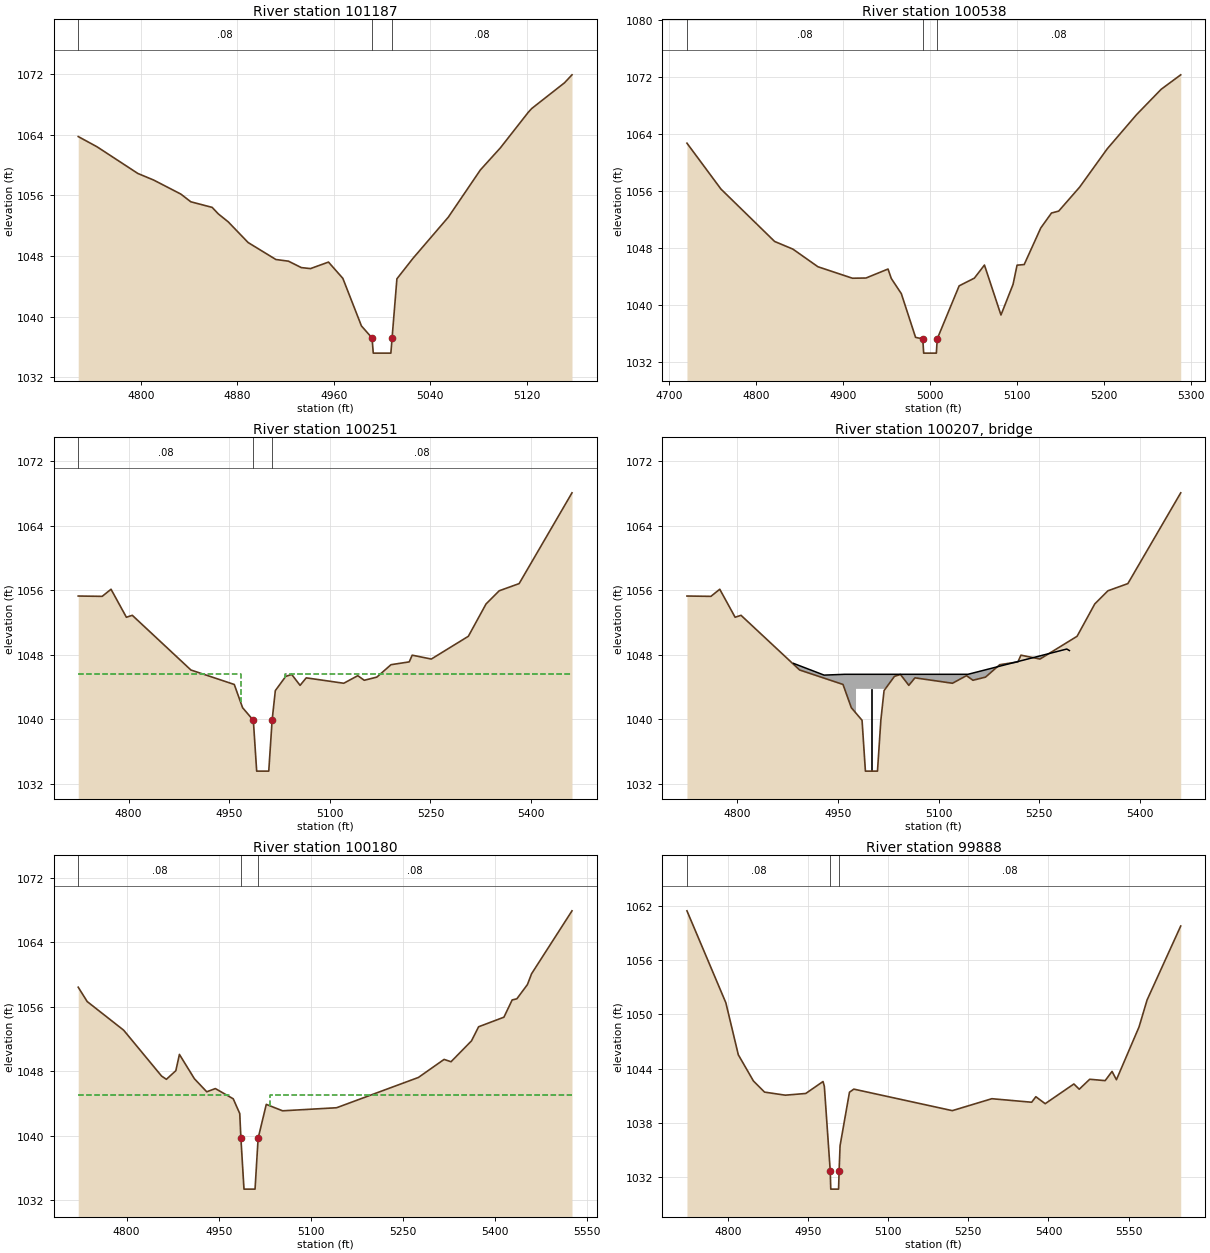
Type RM Length L Ch R = 1,101187,649,649,649
BEGIN DESCRIPTION:
North Hunting Creek 174.0
END DESCRIPTION:
XS GIS Cut Line= 4
      1439338.66       874494.57      1439181.25       874440.72
      1439059.08       874436.58      1438941.08       874461.42
#Sta/Elev= 30
  4748.2 1063.77  4763.8 1062.42  4797.6 1058.90  4810.7 1058.03  4833.2 1056.18
  4841.5 1055.16  4859.2 1054.42  4864.3 1053.56  4872.5 1052.51  4889.0 1049.78
  4912.0 1047.54  4922.4 1047.32  4933.1 1046.47  4940.7 1046.34  4955.6 1047.20
  4967.5 1045.05  4982.9 1038.77  4991.7 1037.18  4992.7 1035.18  5007.3 1035.18
  5008.3 1037.18  5012.3 1044.99  5025.6 1047.69  5054.9 1053.13  5081.5 1059.37
  5098.0 1062.27  5121.1 1066.96  5124.0 1067.47  5151.2 1070.87  5157.4 1071.92
#Mann=3,-1,0
  4748.2    0.08       0  4991.7    0.04       0  5008.3    0.08       0
#XS Ineff=2,0
    0.00 4955.60 1047.20               0
Permanent Ineff=
       F       F
Bank Sta=4991.7,5008.3
XS Rating Curve= 0
Exp/Cntr=0.3,0.1

Type RM Length L Ch R = 1,100538,287,287,287
BEGIN DESCRIPTION:
North Hunting Creek 173.0
END DESCRIPTION:
XS GIS Cut Line= 4
      1439591.21       874262.61      1439512.55       874140.47
      1439338.62       873943.76      1439189.55       873885.79
#Sta/Elev= 30
  4720.5 1062.76  4759.6 1056.32  4821.3 1048.97  4842.4 1047.89  4871.1 1045.42
  4910.8 1043.81  4926.4 1043.84  4951.7 1045.10  4955.5 1043.77  4967.0 1041.65
  4983.4 1035.51  4991.7 1035.30  4992.7 1033.30  5007.3 1033.30  5008.3 1035.30
  5033.5 1042.74  5051.0 1043.82  5062.6 1045.66  5081.6 1038.65  5095.5 1042.95
  5100.1 1045.64  5108.3 1045.73  5127.4 1050.87  5139.7 1052.96  5148.0 1053.23
  5172.1 1056.60  5203.8 1061.97  5237.4 1066.75  5265.8 1070.32  5288.3 1072.35
#Mann=3,-1,0
  4720.5    0.08       0  4991.7    0.04       0  5008.3    0.08       0
Bank Sta=4991.7,5008.3
XS Rating Curve= 0
Exp/Cntr=0.5,0.3

Type RM Length L Ch R = 1,100251,71,71,71
BEGIN DESCRIPTION:
Redding Rd - US
END DESCRIPTION:
XS GIS Cut Line= 4
      1439777.59       874206.74      1439742.39       874096.99
      1439578.81       873718.06      1439386.25       873639.38
#Sta/Elev= 30
  4725.0 1055.30  4760.7 1055.26  4773.9 1056.14  4796.8 1052.67  4805.6 1052.91
  4893.0 1046.13  4957.6 1044.34  4970.0 1041.46  4986.0 1039.90  4991.0 1033.60
  5009.0 1033.60  5014.0 1039.90  5018.8 1043.58  5034.3 1045.34  5043.2 1045.58
  5055.7 1044.23  5064.9 1045.16  5120.8 1044.49  5141.7 1045.43  5151.3 1044.86
  5170.1 1045.25  5191.2 1046.79  5218.4 1047.14  5222.8 1047.97  5251.3 1047.49
  5306.5 1050.31  5332.9 1054.32  5352.5 1055.95  5382.2 1056.84  5461.0 1068.09
#Mann=3,-1,0
  4725.0    0.08       0  4986.0    0.04       0  5014.0    0.08       0
#XS Ineff=2,0
    0.00 4967.00 1045.60 5033.00    0.00 1045.60
Permanent Ineff=
       F       F
Bank Sta=4986,5014
XS Rating Curve= 0
Exp/Cntr=0.5,0.3

Type RM Length L Ch R =3,100207,,,
BEGIN DESCRIPTION:
Redding Rd - TOR
Structure ID: LDS_NLHC_15
Approximate Survey Structure
END DESCRIPTION:
Bridge Culvert--1,0,-1,-1,0
Deck Dist Width WeirC Skew NumUp NumDn MinLoCord MaxHiCord MaxSubmerge Is_Ogee
34,20,3,,10,10,,,,0,1,1,,,
  4883.9  4929.4  4960.2  4977.0  4977.0  5023.0  5023.0  5143.9  5291.1  5295.1
 1046.95 1045.50 1045.60 1045.60 1045.60 1045.60 1045.60 1045.60 1048.73 1048.54
 1013.60 1013.60 1013.60 1013.60 1043.80 1043.80 1013.60 1013.60 1013.60 1013.60
  4883.9  4929.4  4960.2  4977.0  4977.0  5023.0  5023.0  5143.9  5291.1  5295.1
 1046.95 1045.50 1045.60 1045.60 1045.60 1045.60 1045.60 1045.60 1048.73 1048.54
 1013.60 1013.60 1013.60 1013.60 1043.80 1043.80 1013.60 1013.60 1013.60 1013.60
Pier Skew, UpSta & Num, DnSta & Num=,5000,2,5000,2,0,0,0,0,0
       1       1
 1033.60 1043.80
       1       1
 1033.35 1043.80
BR Coef=1,1,0,1.25,0,,,0.8,0,2,0,
WSPro=,,,, 1 ,,,, 0 ,,,, 0 ,,,,-1 ,-1 ,-1 , 0 , 0 , 0 , 0 , 0
BC Design=,,0,,0,,,,,,

Type RM Length L Ch R = 1,100180,292,292,292
BEGIN DESCRIPTION:
Redding Rd - DS
END DESCRIPTION:
XS GIS Cut Line= 4
      1439825.22       874194.28      1439822.07       874079.32
      1439617.85       873673.60      1439394.54       873602.11
#Sta/Elev= 30
  4721.2 1058.41  4735.8 1056.63  4795.1 1053.08  4856.9 1047.38  4864.7 1046.98
  4880.1 1048.05  4885.9 1050.07  4910.4 1047.04  4930.4 1045.43  4944.4 1045.83
  4973.5 1044.56  4984.1 1042.73  4986.0 1039.65  4991.0 1033.35  5009.0 1033.35
  5014.0 1039.65  5027.3 1043.87  5053.8 1043.07  5141.7 1043.45  5274.9 1047.21
  5316.7 1049.45  5328.0 1049.16  5361.3 1051.75  5372.9 1053.50  5414.1 1054.69
  5427.5 1056.83  5435.1 1056.97  5452.3 1058.73  5459.1 1060.08  5524.9 1067.89
#Mann=3,-1,0
  4721.2    0.08       0  4986.0    0.04       0  5014.0    0.08       0
#XS Ineff=2,0
    0.00 4967.00 1045.00 5033.00    0.00 1045.00
Permanent Ineff=
       F       F
Bank Sta=4986,5014
XS Rating Curve= 0
Exp/Cntr=0.5,0.3

Type RM Length L Ch R = 1,99888,690,690,690
BEGIN DESCRIPTION:
North Hunting Creek 172.0
END DESCRIPTION:
XS GIS Cut Line= 4
      1440028.14       874190.16      1440050.92       874047.30
      1439978.45       873482.01      1439986.73       873272.85
#Sta/Elev= 30
  4723.6 1061.46  4796.4 1051.29  4819.7 1045.54  4848.0 1042.64  4868.8 1041.41
  4907.7 1041.07  4945.9 1041.26  4978.2 1042.58  4980.7 1042.04  4991.7 1032.68
  4992.7 1030.68  5007.3 1030.68  5008.3 1032.68  5010.1 1035.49  5027.7 1041.40
  5035.8 1041.74  5220.1 1039.36  5294.1 1040.68  5368.6 1040.29  5376.4 1040.90
  5393.9 1040.13  5447.6 1042.31  5457.6 1041.73  5477.2 1042.83  5506.1 1042.68
  5519.0 1043.70  5527.2 1042.78  5569.5 1048.62  5584.6 1051.61  5647.5 1059.78
#Mann=3,-1,0
  4723.6    0.08       0  4991.7    0.04       0  5008.3    0.08       0
Bank Sta=4991.7,5008.3
XS Rating Curve= 0
Exp/Cntr=0.3,0.1

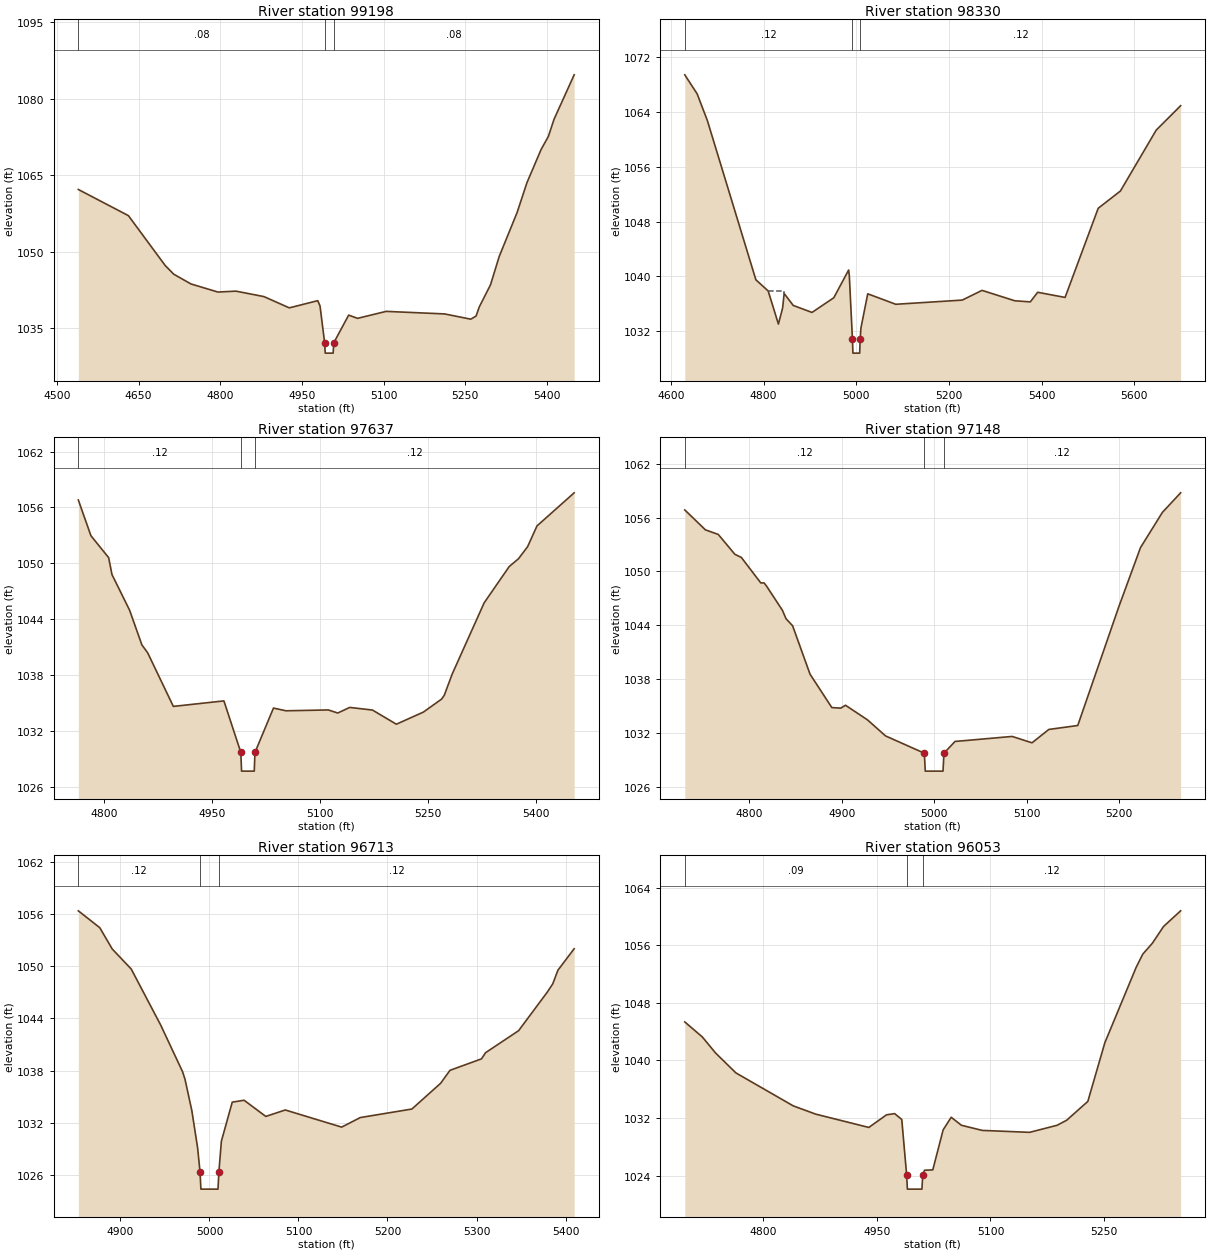
Type RM Length L Ch R = 1,99198,868,868,868
BEGIN DESCRIPTION:
North Hunting Creek 171.0
END DESCRIPTION:
XS GIS Cut Line= 4
      1440533.35       874152.94      1440701.10       873900.28
      1440659.69       873457.16      1440628.62       873297.69
#Sta/Elev= 30
  4539.2 1062.24  4631.2 1057.11  4698.6 1047.35  4714.5 1045.62  4746.1 1043.71
  4795.7 1042.12  4828.7 1042.30  4880.1 1041.23  4926.7 1039.02  4979.0 1040.43
  4983.2 1039.38  4991.7 1032.14  4992.7 1030.14  5007.3 1030.14  5008.3 1032.14
  5035.8 1037.60  5052.1 1036.96  5104.7 1038.33  5212.0 1037.83  5260.1 1036.80
  5269.9 1037.42  5275.6 1039.18  5296.3 1043.53  5312.4 1049.12  5345.2 1057.72
  5363.2 1063.55  5389.3 1070.09  5402.7 1072.66  5413.0 1076.00  5450.0 1084.73
#Mann=3,-1,0
  4539.2    0.08       0  4991.7    0.04       0  5008.3    0.08       0
Bank Sta=4991.7,5008.3
XS Rating Curve= 0
Exp/Cntr=0.3,0.1

Type RM Length L Ch R = 1,98330,693,693,693
BEGIN DESCRIPTION:
North Hunting Creek 170.0
END DESCRIPTION:
XS GIS Cut Line= 4
      1441730.18       873850.55      1441628.75       873749.12
      1441249.82       873148.63      1441042.74       873084.44
#Sta/Elev= 30
  4629.8 1069.43  4656.5 1066.65  4678.5 1062.76  4783.2 1039.52  4809.8 1037.88
  4831.9 1033.05  4840.9 1035.38  4844.3 1037.51  4863.9 1035.77  4904.4 1034.75
  4951.4 1036.89  4983.5 1040.94  4984.9 1040.16  4991.7 1030.81  4992.7 1028.81
  5007.3 1028.81  5008.3 1030.81  5010.0 1032.47  5024.7 1037.47  5085.2 1035.94
  5228.7 1036.55  5271.4 1037.97  5342.2 1036.45  5375.6 1036.29  5391.5 1037.69
  5450.7 1036.94  5522.2 1049.95  5570.1 1052.47  5647.4 1061.36  5700.1 1064.92
#Mann=3,-1,0
  4629.8    0.12       0  4991.7    0.04       0  5008.3    0.12       0
#XS Ineff=1,-1
 4809.80 4844.30 1037.88
Permanent Ineff=
       T
Bank Sta=4991.7,5008.3
XS Rating Curve= 0
Exp/Cntr=0.3,0.1

Type RM Length L Ch R = 1,97637,489,489,489
BEGIN DESCRIPTION:
North Hunting Creek 169.0
END DESCRIPTION:
XS GIS Cut Line= 4
      1442173.33       873519.27      1442136.06       873395.04
      1441972.48       873059.60      1442036.67       872885.67
#Sta/Elev= 30
  4764.6 1056.80  4782.1 1052.97  4806.7 1050.62  4811.3 1048.81  4835.8 1044.98
  4852.8 1041.27  4860.9 1040.41  4896.5 1034.67  4966.7 1035.26  4990.2 1029.73
  4991.2 1027.73  5008.8 1027.73  5009.8 1029.73  5035.5 1034.49  5052.9 1034.20
  5111.7 1034.29  5124.7 1033.96  5141.3 1034.56  5172.9 1034.28  5206.1 1032.76
  5243.6 1034.06  5269.0 1035.46  5272.7 1035.88  5283.6 1038.14  5328.0 1045.78
  5362.8 1049.67  5375.6 1050.50  5388.3 1051.80  5401.3 1054.02  5452.9 1057.57
#Mann=3,-1,0
  4764.6    0.12       0  4990.2    0.04       0  5009.8    0.12       0
Bank Sta=4990.2,5009.8
XS Rating Curve= 0
Exp/Cntr=0.3,0.1

Type RM Length L Ch R = 1,97148,435,435,435
BEGIN DESCRIPTION:
North Hunting Creek 168.0
END DESCRIPTION:
XS GIS Cut Line= 4
      1442541.95       873007.82      1442357.62       873038.89
      1442117.42       872945.71      1442063.60       872871.19
#Sta/Elev= 30
  4730.2 1056.86  4752.5 1054.64  4766.4 1054.13  4784.4 1051.91  4791.4 1051.56
  4812.4 1048.72  4816.0 1048.72  4818.6 1048.37  4835.8 1045.67  4839.7 1044.73
  4846.9 1043.93  4865.7 1038.54  4889.3 1034.81  4899.0 1034.75  4904.1 1035.07
  4928.0 1033.43  4947.4 1031.65  4989.4 1029.72  4990.4 1027.72  5009.6 1027.72
  5010.6 1029.72  5022.6 1031.03  5084.4 1031.59  5105.9 1030.88  5124.1 1032.37
  5155.4 1032.81  5200.1 1046.14  5223.3 1052.66  5247.0 1056.59  5266.7 1058.77
#Mann=3,-1,0
  4730.2    0.12       0  4989.4    0.04       0  5010.6    0.12       0
Bank Sta=4989.4,5010.6
XS Rating Curve= 0
Exp/Cntr=0.3,0.1

Type RM Length L Ch R = 1,96713,660,660,660
BEGIN DESCRIPTION:
North Hunting Creek 167.0
END DESCRIPTION:
XS GIS Cut Line= 4
      1442606.09       872943.60      1442585.11       872816.93
      1442530.00       872576.85      1442353.44       872531.57
#Sta/Elev= 30
  4852.7 1056.36  4876.8 1054.42  4890.8 1051.97  4912.1 1049.67  4945.3 1043.21
  4969.8 1037.86  4972.5 1037.01  4980.2 1033.39  4986.7 1029.11  4989.4 1026.36
  4990.4 1024.36  5009.6 1024.36  5010.6 1026.36  5013.4 1029.87  5025.6 1034.36
  5038.9 1034.58  5063.3 1032.72  5085.2 1033.46  5148.5 1031.49  5169.5 1032.59
  5227.4 1033.57  5259.7 1036.53  5270.2 1038.02  5305.6 1039.34  5310.2 1040.05
  5347.3 1042.58  5379.5 1047.01  5385.7 1047.97  5391.5 1049.54  5409.7 1052.00
#Mann=3,-1,0
  4852.7    0.12       0  4989.4    0.04       0  5010.6    0.12       0
Bank Sta=4989.4,5010.6
XS Rating Curve= 0
Exp/Cntr=0.3,0.1

Type RM Length L Ch R = 1,96053,364,364,364
BEGIN DESCRIPTION:
North Hunting Creek 166.0
END DESCRIPTION:
XS GIS Cut Line= 4
      1443113.39       873012.00      1443223.15       872850.46
      1443237.64       872539.86      1443223.15       872392.81
#Sta/Elev= 30
  4696.8 1045.35  4719.9 1043.27  4737.4 1041.04  4764.2 1038.28  4839.9 1033.70
  4869.4 1032.56  4939.5 1030.71  4962.9 1032.46  4973.6 1032.63  4983.0 1031.81
  4989.4 1024.15  4990.4 1022.15  5009.6 1022.15  5010.6 1024.15  5013.0 1024.77
  5023.9 1024.82  5037.6 1030.38  5048.2 1032.12  5061.7 1031.01  5089.1 1030.30
  5151.6 1030.03  5187.9 1031.01  5200.5 1031.71  5228.4 1034.32  5250.8 1042.45
  5292.2 1052.94  5300.9 1054.76  5313.5 1056.27  5328.3 1058.60  5350.8 1060.77
#Mann=3,-1,0
  4696.8    0.09       0  4989.4    0.04       0  5010.6    0.12       0
Bank Sta=4989.4,5010.6
XS Rating Curve= 0
Exp/Cntr=0.3,0.1

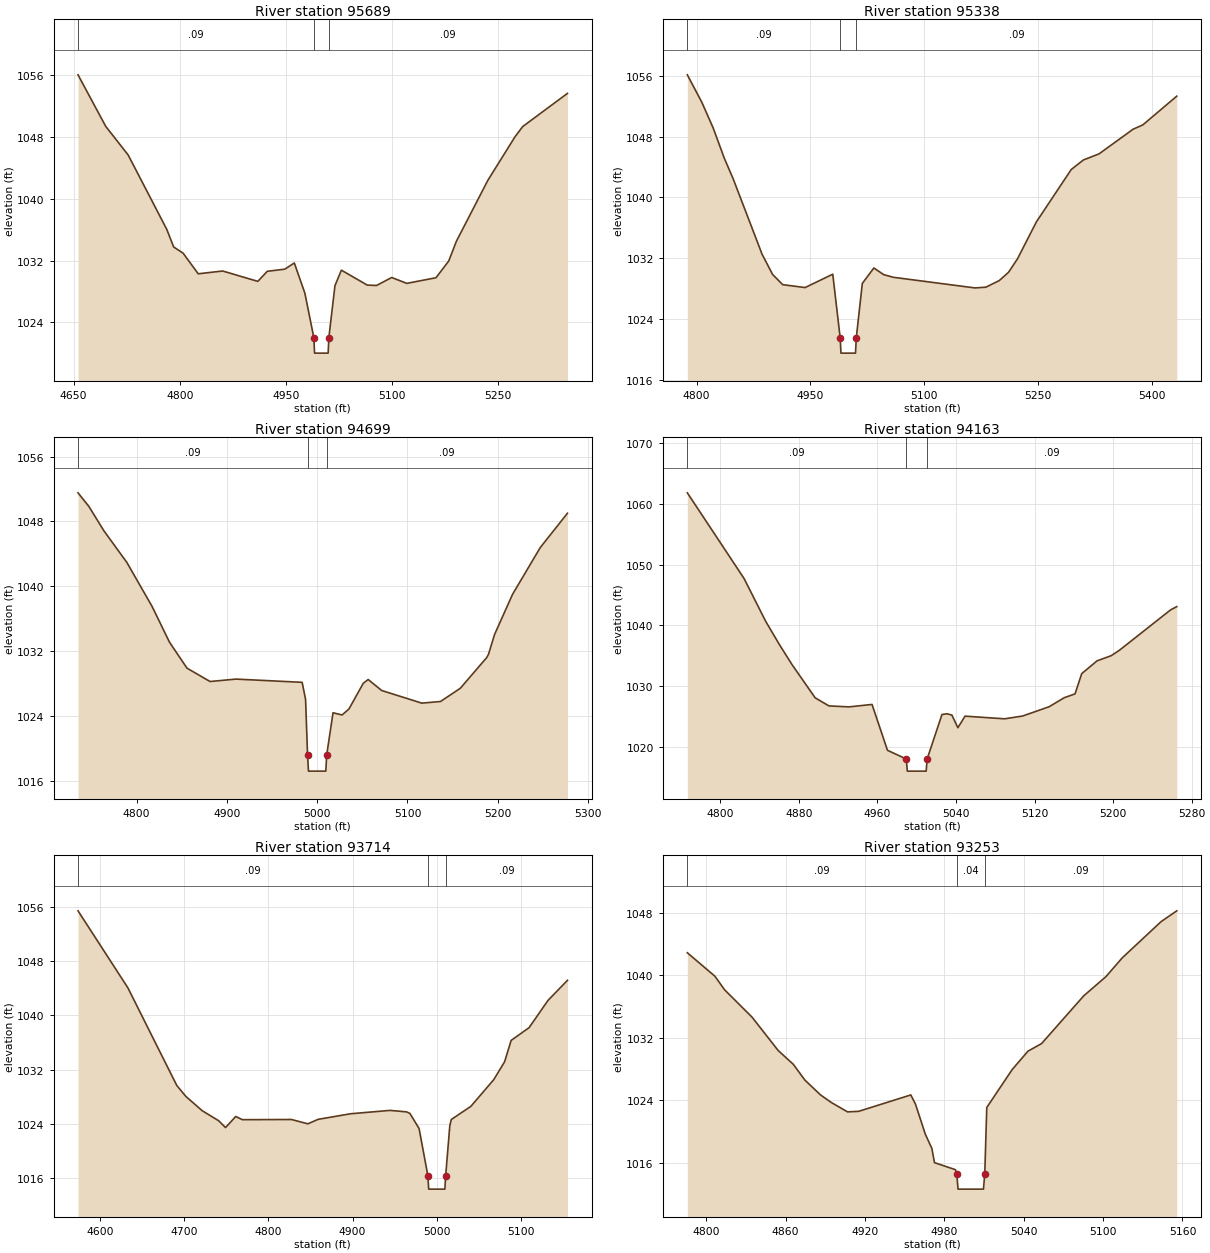
Type RM Length L Ch R = 1,95689,351,351,351
BEGIN DESCRIPTION:
North Hunting Creek 165.5
END DESCRIPTION:
XS GIS Cut Line= 4
      1443652.26       873073.44      1443572.45       872944.02
      1443609.13       872572.98      1443570.29       872411.17
#Sta/Elev= 30
  4656.3 1056.02  4695.5 1049.35  4727.1 1045.66  4781.7 1036.03  4791.4 1033.76
  4804.7 1032.96  4826.1 1030.29  4860.6 1030.65  4910.3 1029.31  4923.6 1030.61
  4948.4 1030.89  4961.8 1031.69  4976.7 1027.79  4989.4 1022.03  4990.4 1020.03
  5009.6 1020.03  5010.6 1022.03  5019.2 1028.75  5028.3 1030.76  5064.8 1028.83
  5078.0 1028.78  5099.4 1029.81  5120.7 1029.05  5161.9 1029.78  5179.9 1031.94
  5190.8 1034.51  5235.0 1042.35  5273.6 1048.02  5284.4 1049.33  5347.6 1053.62
#Mann=3,-1,0
  4656.3    0.09       0  4989.4    0.04       0  5010.6    0.09       0
Bank Sta=4989.4,5010.6
XS Rating Curve= 0
Exp/Cntr=0.3,0.1

Type RM Length L Ch R = 1,95338,639,639,639
BEGIN DESCRIPTION:
North Hunting Creek 165.0
END DESCRIPTION:
XS GIS Cut Line= 4
      1443900.24       873034.79      1443918.89       872918.79
      1443935.45       872618.55      1443962.37       872392.83
#Sta/Elev= 30
  4787.8 1056.16  4807.0 1052.53  4822.0 1049.13  4836.6 1045.16  4848.2 1042.47
  4886.4 1032.52  4900.3 1029.85  4913.6 1028.51  4943.1 1028.13  4979.6 1029.89
  4989.4 1021.49  4990.4 1019.49  5009.6 1019.49  5010.6 1021.49  5018.6 1028.68
  5033.8 1030.71  5046.8 1029.83  5059.6 1029.48  5167.3 1028.08  5181.5 1028.18
  5199.2 1029.05  5211.5 1030.15  5223.3 1031.93  5248.2 1036.79  5294.1 1043.68
  5310.1 1044.94  5330.7 1045.74  5375.8 1049.00  5388.5 1049.56  5433.3 1053.35
#Mann=3,-1,0
  4787.8    0.09       0  4989.4    0.04       0  5010.6    0.09       0
Bank Sta=4989.4,5010.6
XS Rating Curve= 0
Exp/Cntr=0.3,0.1

Type RM Length L Ch R = 1,94699,536,536,536
BEGIN DESCRIPTION:
North Hunting Creek 164.0
END DESCRIPTION:
XS GIS Cut Line= 4
      1444316.49       873262.51      1444428.27       873216.97
      1444544.22       872935.36      1444593.93       872829.72
#Sta/Elev= 30
  4735.2 1051.54  4747.1 1049.88  4764.0 1046.83  4789.3 1042.94  4817.3 1037.49
  4836.5 1033.09  4855.9 1029.88  4881.4 1028.23  4910.1 1028.53  4983.4 1028.13
  4987.2 1026.03  4989.4 1019.16  4990.4 1017.16  5009.6 1017.16  5010.6 1019.16
  5017.6 1024.37  5027.6 1024.10  5035.2 1024.83  5051.1 1028.01  5056.5 1028.48
  5071.5 1027.12  5115.9 1025.56  5136.6 1025.76  5158.6 1027.40  5187.8 1031.19
  5189.8 1031.60  5196.4 1034.02  5216.4 1039.00  5247.1 1044.78  5277.2 1049.02
#Mann=3,-1,0
  4735.2    0.09       0  4989.4    0.04       0  5010.6    0.09       0
Bank Sta=4989.4,5010.6
XS Rating Curve= 0
Exp/Cntr=0.3,0.1

Type RM Length L Ch R = 1,94163,449,449,449
BEGIN DESCRIPTION:
North Hunting Creek 163.0
END DESCRIPTION:
XS GIS Cut Line= 4
      1444979.06       873368.15      1444976.99       873248.03
      1444879.67       873028.54      1444811.34       872908.45
#Sta/Elev= 30
  4766.4 1061.85  4824.2 1047.71  4846.2 1040.65  4860.3 1036.78  4873.1 1033.49
  4896.6 1028.03  4910.6 1026.70  4931.0 1026.54  4954.5 1026.94  4970.2 1019.38
  4989.4 1017.94  4990.4 1015.94  5009.6 1015.94  5010.6 1017.94  5025.7 1025.28
  5030.8 1025.40  5035.8 1025.19  5041.9 1023.10  5049.2 1025.01  5089.5 1024.57
  5107.8 1025.03  5134.8 1026.56  5150.2 1028.05  5161.2 1028.68  5168.0 1032.02
  5183.6 1034.13  5198.0 1034.98  5206.4 1035.88  5258.5 1042.54  5264.8 1043.08
#Mann=3,-1,0
  4766.4    0.09       0  4989.4    0.04       0  5010.6    0.09       0
Bank Sta=4989.4,5010.6
XS Rating Curve= 0
Exp/Cntr=0.3,0.1

Type RM Length L Ch R = 1,93714,461,461,461
BEGIN DESCRIPTION:
North Hunting Creek 162.0
END DESCRIPTION:
XS GIS Cut Line= 4
      1445438.74       873165.17      1445418.04       873036.82
      1445179.91       872798.70      1445115.73       872703.46
#Sta/Elev= 30
  4573.7 1055.38  4633.0 1044.04  4691.1 1029.67  4701.9 1028.06  4721.2 1025.97
  4740.8 1024.49  4749.0 1023.48  4761.1 1025.11  4769.1 1024.64  4827.3 1024.67
  4846.8 1024.03  4859.0 1024.69  4897.5 1025.51  4944.5 1026.01  4964.1 1025.79
  4968.1 1025.56  4979.0 1023.34  4989.4 1016.42  4990.4 1014.42  5009.6 1014.42
  5010.6 1016.42  5015.5 1023.75  5017.3 1024.67  5040.5 1026.60  5067.7 1030.53
  5080.6 1033.16  5088.4 1036.31  5109.7 1038.18  5132.2 1042.20  5155.3 1045.15
#Mann=3,-1,0
  4573.7    0.09       0  4989.4    0.04       0  5010.6    0.09       0
Bank Sta=4989.4,5010.6
XS Rating Curve= 0
Exp/Cntr=0.3,0.1

Type RM Length L Ch R = 1,93253,542,542,542
BEGIN DESCRIPTION:
North Hunting Creek 161.0
END DESCRIPTION:
XS GIS Cut Line= 4
      1445622.99       872475.66      1445521.57       872444.61
      1445403.54       872421.84      1445264.83       872459.10
#Sta/Elev= 30
  4785.8 1042.86  4806.7 1039.85  4813.9 1038.13  4834.7 1034.62  4854.5 1030.34
  4865.9 1028.58  4874.6 1026.57  4886.4 1024.67  4894.7 1023.68  4906.9 1022.49
  4915.3 1022.56  4954.7 1024.66  4958.2 1023.49  4965.7 1019.62  4970.6 1017.81
  4972.6 1015.99  4988.4 1015.09  4989.4 1014.60  4990.4 1012.60  5009.6 1012.60
  5010.6 1014.60  5012.1 1023.05  5031.4 1027.93  5043.3 1030.27  5053.5 1031.23
  5085.4 1037.35  5102.2 1039.81  5114.5 1042.21  5143.8 1046.84  5155.7 1048.23
#Mann=3,-1,0
  4785.8    0.09       0  4989.4    0.04       0  5010.6    0.09       0
Bank Sta=4989.4,5010.6
XS Rating Curve= 0
Exp/Cntr=0.3,0.1

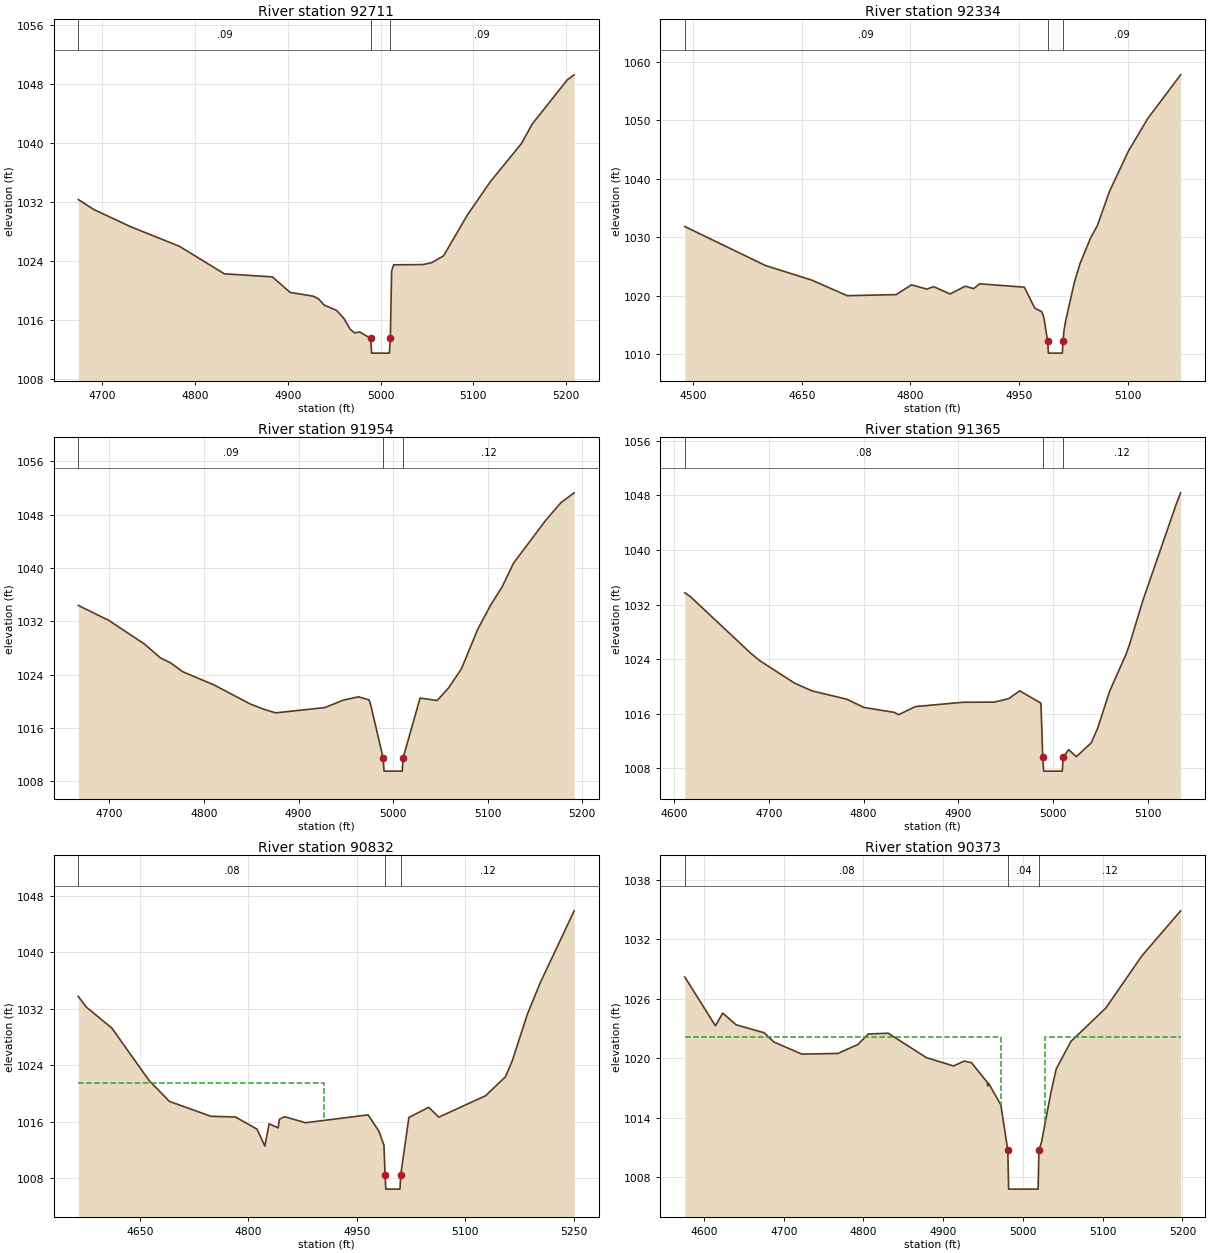
Type RM Length L Ch R = 1,92711,377,377,377
BEGIN DESCRIPTION:
North Hunting Creek 160.0
END DESCRIPTION:
XS GIS Cut Line= 4
      1445784.53       872040.83      1445681.01       871949.73
      1445440.81       871889.68      1445295.91       871924.87
#Sta/Elev= 30
  4674.2 1032.34  4690.8 1030.99  4730.7 1028.64  4783.1 1025.99  4831.6 1022.25
  4883.4 1021.83  4902.6 1019.72  4927.4 1019.21  4933.3 1018.83  4939.2 1018.00
  4952.7 1017.27  4960.6 1016.18  4967.4 1014.70  4972.1 1014.22  4977.6 1014.35
  4989.4 1013.47  4990.4 1011.47  5009.6 1011.47  5010.6 1013.47  5012.0 1022.62
  5014.2 1023.47  5045.4 1023.50  5055.1 1023.75  5068.0 1024.69  5093.7 1030.24
  5118.3 1034.74  5152.0 1039.95  5163.7 1042.62  5201.6 1048.63  5208.8 1049.28
#Mann=3,-1,0
  4674.2    0.09       0  4989.4    0.04       0  5010.6    0.09       0
Bank Sta=4989.4,5010.6
XS Rating Curve= 0
Exp/Cntr=0.3,0.1

Type RM Length L Ch R = 1,92334,380,380,380
BEGIN DESCRIPTION:
North Hunting Creek 159.5
END DESCRIPTION:
XS GIS Cut Line= 4
      1445923.17       872002.87      1445812.73       871838.39
      1445601.29       871582.31      1445580.14       871429.58
#Sta/Elev= 30
  4488.5 1031.82  4599.8 1025.15  4664.0 1022.64  4712.6 1019.99  4780.4 1020.17
  4801.3 1021.84  4822.6 1021.12  4832.0 1021.53  4854.6 1020.28  4875.7 1021.61
  4887.2 1021.19  4895.5 1022.02  4957.2 1021.44  4971.6 1017.85  4981.3 1017.25
  4984.2 1016.23  4989.4 1012.16  4990.4 1010.16  5009.6 1010.16  5010.6 1012.16
  5012.0 1014.11  5014.4 1015.78  5026.3 1022.30  5033.9 1025.43  5048.4 1029.80
  5058.1 1032.02  5074.6 1037.79  5100.8 1044.72  5127.7 1050.32  5172.9 1057.77
#Mann=3,-1,0
  4488.5    0.09       0  4989.4    0.04       0  5010.6    0.09       0
Bank Sta=4989.4,5010.6
XS Rating Curve= 0
Exp/Cntr=0.3,0.1

Type RM Length L Ch R = 1,91954,589,589,589
BEGIN DESCRIPTION:
North Hunting Creek 159.0
END DESCRIPTION:
XS GIS Cut Line= 4
      1446045.42       871914.48      1445987.46       871777.87
      1445972.97       871539.74      1445946.06       871405.17
#Sta/Elev= 30
  4667.2 1034.41  4699.2 1032.18  4737.1 1028.62  4754.1 1026.53  4765.1 1025.76
  4777.5 1024.47  4811.0 1022.46  4849.1 1019.61  4864.0 1018.80  4875.7 1018.29
  4927.7 1019.08  4947.3 1020.20  4963.4 1020.70  4974.5 1020.24  4976.1 1019.61
  4989.4 1011.55  4990.4 1009.55  5009.6 1009.55  5010.6 1011.55  5028.5 1020.51
  5046.5 1020.14  5058.6 1022.03  5072.2 1024.89  5089.6 1030.88  5103.1 1034.45
  5115.3 1037.21  5127.4 1040.77  5161.4 1047.19  5177.5 1049.84  5191.4 1051.30
#Mann=3,-1,0
  4667.2    0.09       0  4989.4    0.04       0  5010.6    0.12       0
Bank Sta=4989.4,5010.6
XS Rating Curve= 0
Exp/Cntr=0.3,0.1

Type RM Length L Ch R = 1,91365,533,533,533
BEGIN DESCRIPTION:
North Hunting Creek 158.0
END DESCRIPTION:
XS GIS Cut Line= 4
      1446260.78       871920.75      1446339.47       871815.14
      1446525.83       871574.94      1446575.53       871502.46
#Sta/Elev= 30
  4611.2 1033.73  4616.6 1033.23  4680.6 1024.89  4690.6 1023.75  4727.6 1020.44
  4745.8 1019.33  4782.2 1018.12  4800.4 1016.91  4832.4 1016.19  4837.0 1015.85
  4854.8 1017.04  4904.9 1017.67  4938.2 1017.69  4953.4 1018.21  4964.8 1019.35
  4987.3 1017.54  4989.2 1009.57  4990.2 1007.57  5009.8 1007.57  5010.8 1009.57
  5016.6 1010.73  5024.6 1009.69  5040.4 1011.71  5047.3 1013.90  5059.8 1019.28
  5077.3 1024.75  5081.2 1026.30  5094.9 1032.59  5130.2 1046.74  5134.8 1048.39
#Mann=3,-1,0
  4611.2    0.08       0  4989.2    0.04       0  5010.8    0.12       0
Bank Sta=4989.2,5010.8
XS Rating Curve= 0
Exp/Cntr=0.3,0.1

Type RM Length L Ch R = 1,90832,459,459,459
BEGIN DESCRIPTION:
North Hunting Creek 157.0
END DESCRIPTION:
XS GIS Cut Line= 4
      1446904.76       872349.39      1446902.69       872198.21
      1446890.27       871784.08      1446896.48       871663.95
#Sta/Elev= 30
  4564.9 1033.73  4575.9 1032.23  4611.3 1029.25  4662.8 1021.83  4691.0 1018.87
  4748.3 1016.77  4782.2 1016.67  4812.0 1014.96  4822.9 1012.56  4828.8 1015.71
  4841.2 1015.13  4843.1 1016.36  4850.2 1016.71  4879.2 1015.86  4965.7 1016.97
  4980.7 1014.65  4987.6 1012.68  4989.2 1008.46  4990.2 1006.46  5009.8 1006.46
  5010.8 1008.46  5022.1 1016.60  5049.5 1018.04  5063.6 1016.65  5128.2 1019.68
  5155.6 1022.35  5165.1 1024.62  5186.0 1031.22  5203.7 1035.65  5250.7 1045.85
#Mann=3,-1,0
  4564.9    0.08       0  4989.2    0.04       0  5010.8    0.12       0
#XS Ineff=2,0
    0.00 4904.30 1021.50               0
Permanent Ineff=
       F       F
Bank Sta=4989.2,5010.8
XS Rating Curve= 0
Exp/Cntr=0.5,0.3

Type RM Length L Ch R = 1,90373,85,85,85
BEGIN DESCRIPTION:
Union Church Rd - US
END DESCRIPTION:
XS GIS Cut Line= 4
      1447262.99       872218.95      1447178.09       871984.93
      1447296.11       871717.82      1447314.74       871639.17
#Sta/Elev= 30
  4575.9 1028.21  4614.3 1023.29  4623.5 1024.57  4640.2 1023.39  4675.3 1022.59
  4687.7 1021.65  4722.8 1020.43  4768.0 1020.50  4793.1 1021.41  4805.9 1022.46
  4831.1 1022.54  4878.6 1020.09  4912.8 1019.24  4926.3 1019.73  4935.4 1019.57
  4955.3 1017.58  4955.7 1017.23  4956.8 1017.50  4972.2 1015.32  4981.0 1010.72
  4982.0 1006.82  5019.0 1006.82  5020.0 1010.72  5023.4 1011.61  5034.7 1016.42
  5041.6 1018.92  5060.1 1021.71  5103.9 1025.08  5149.1 1030.34  5197.7 1034.88
#Mann=3,-1,0
  4575.9    0.08       0  4981.0    0.04       0  5020.0    0.12       0
#XS Ineff=2,0
    0.00 4972.00 1022.20 5028.00    0.00 1022.20
Permanent Ineff=
       F       F
Bank Sta=4981,5020
XS Rating Curve= 0
Exp/Cntr=0.5,0.3

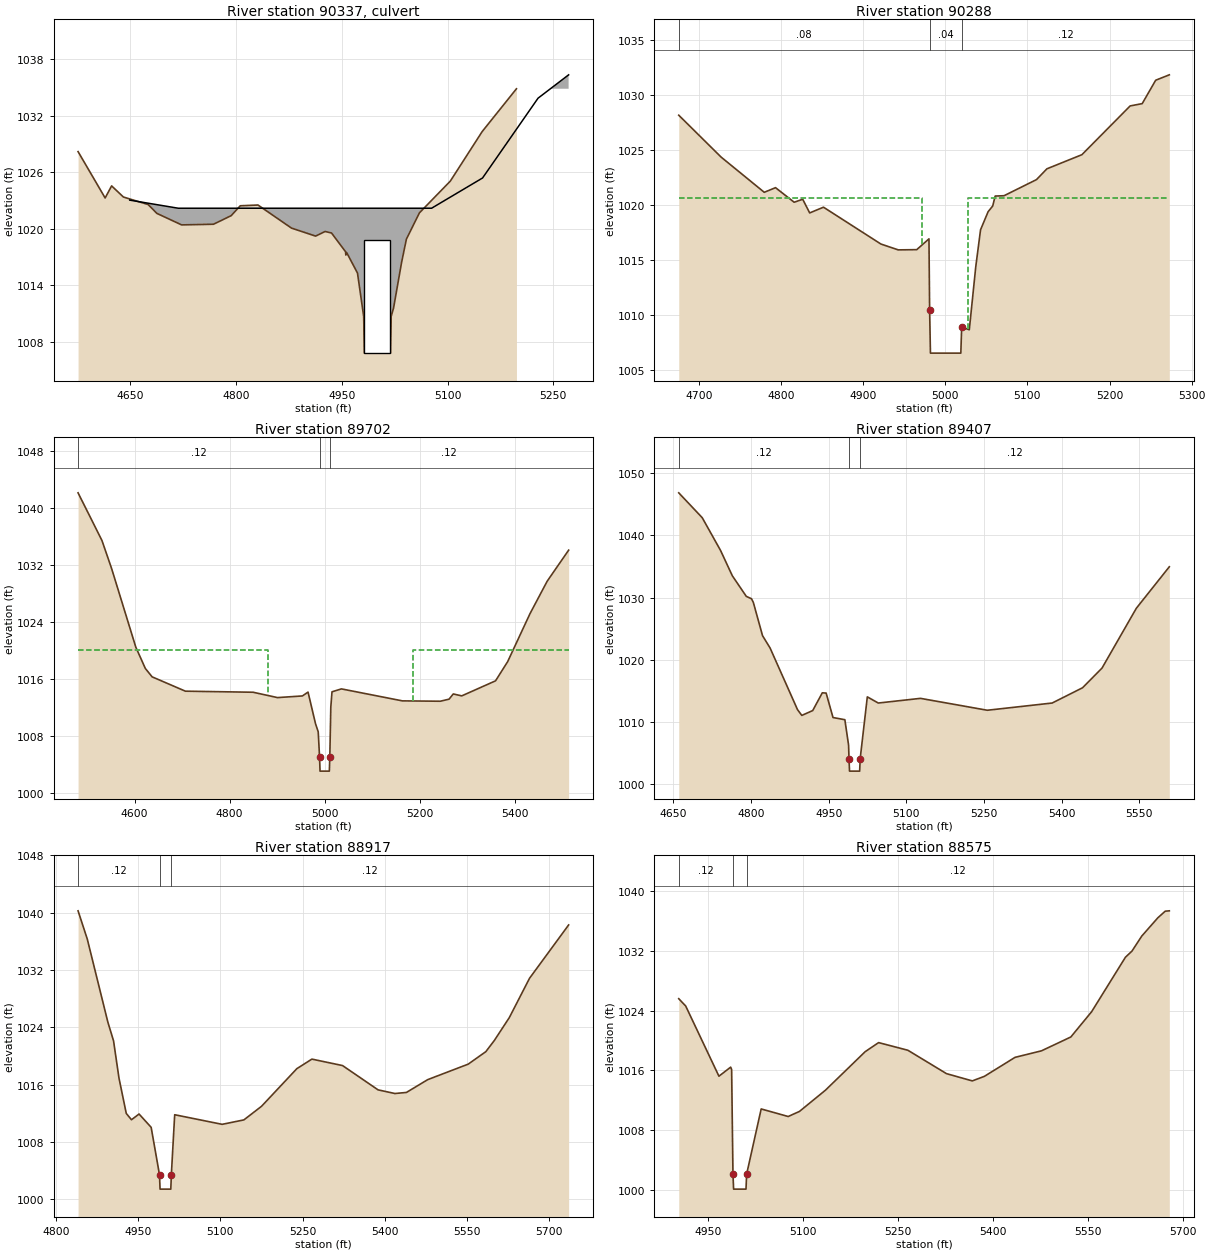
Type RM Length L Ch R =2,90337,,,
BEGIN DESCRIPTION:
Union Church Rd - TOR
Structure ID: LDS_NLHC_14
Approximate Survey Structure
END DESCRIPTION:
Bridge Culvert--1,0,-1,-1,0
Deck Dist Width WeirC Skew NumUp NumDn MinLoCord MaxHiCord MaxSubmerge Is_Ogee
11,50,3,,6,6,,,,0,1,1,,,
  4649.2  4718.1  5077.3  5149.6  5228.3  5271.7
 1023.06 1022.20 1022.20 1025.41 1033.88 1036.36
  986.82  986.82  986.82  986.82  986.82  986.82
  4649.2  4718.1  5077.3  5149.6  5228.3  5271.7
 1023.06 1022.20 1022.20 1025.41 1033.88 1036.36
  986.57  986.57  986.57  986.57  986.57  986.57
Culvert=2,12,36,50,0.013,0.2,1,58,1,1006.82,5000,1006.57,5000,Culvert #1,0,11
Culvert Bottom n=0.013
Culvert Bottom Depth=0
Culvert Depth Blocked=0
BC Design=,,0,,0,,,,,,

Type RM Length L Ch R = 1,90288,586,586,586
BEGIN DESCRIPTION:
Union Church Rd - DS
END DESCRIPTION:
XS GIS Cut Line= 4
      1447325.09       872181.63      1447252.63       872036.70
      1447360.30       871742.67      1447391.36       871624.65
#Sta/Elev= 30
  4675.6 1028.14  4727.2 1024.34  4779.7 1021.15  4793.4 1021.57  4816.1 1020.25
  4826.5 1020.52  4835.0 1019.28  4851.8 1019.80  4921.7 1016.46  4942.8 1015.93
  4965.3 1015.95  4980.2 1016.93  4981.0 1010.47  4982.0 1006.57  5019.0 1006.57
  5020.0 1008.93  5029.3 1008.69  5037.2 1014.42  5043.0 1017.75  5052.2 1019.39
  5057.8 1019.91  5060.8 1020.81  5071.6 1020.84  5111.1 1022.30  5123.8 1023.28
  5166.4 1024.56  5225.1 1028.98  5239.8 1029.19  5256.2 1031.31  5272.8 1031.80
#Mann=3,-1,0
  4675.6    0.08       0  4981.0    0.04       0  5020.0    0.12       0
#XS Ineff=2,0
    0.00 4972.00 1020.60 5028.00    0.00 1020.60
Permanent Ineff=
       F       F
Bank Sta=4981,5020
XS Rating Curve= 0
Exp/Cntr=0.5,0.3

Type RM Length L Ch R = 1,89702,295,295,295
BEGIN DESCRIPTION:
North Hunting Creek 156.0
END DESCRIPTION:
XS GIS Cut Line= 4
      1448047.75       872336.89      1448033.26       872196.14
      1447577.72       871612.21      1447461.73       871516.94
#Sta/Elev= 30
  4481.1 1042.08  4531.4 1035.39  4551.7 1031.46  4602.6 1020.44  4622.6 1017.46
  4636.9 1016.28  4706.9 1014.27  4849.4 1014.12  4900.7 1013.37  4953.1 1013.60
  4965.0 1014.14  4980.7 1009.71  4986.4 1008.57  4989.2 1005.06  4990.2 1003.06
  5009.8 1003.06  5010.8 1005.06  5012.9 1012.05  5015.4 1014.18  5035.2 1014.59
  5163.5 1012.91  5243.3 1012.86  5261.7 1013.15  5270.6 1013.88  5288.4 1013.61
  5359.5 1015.72  5385.0 1018.41  5432.1 1025.15  5468.0 1029.67  5513.3 1034.04
#Mann=3,-1,0
  4481.1    0.12       0  4989.2    0.04       0  5010.8    0.12       0
#XS Ineff=2,0
    0.00 4880.00 1020.00 5185.00    0.00 1020.00
Permanent Ineff=
       F       F
Bank Sta=4989.2,5010.8
XS Rating Curve= 0
Exp/Cntr=0.3,0.1

Type RM Length L Ch R = 1,89407,490,490,490
BEGIN DESCRIPTION:
North Hunting Creek 155.5
END DESCRIPTION:
XS GIS Cut Line= 4
      1448349.06       871658.38      1448129.04       871735.53
      1447634.76       871621.25      1447471.88       871492.65
#Sta/Elev= 30
  4660.2 1046.85  4705.6 1042.85  4741.0 1037.59  4763.7 1033.53  4790.7 1030.22
  4800.8 1029.83  4804.4 1029.23  4822.1 1023.90  4836.7 1021.92  4889.7 1012.02
  4898.0 1011.09  4919.1 1011.87  4937.6 1014.72  4945.0 1014.68  4958.3 1010.75
  4981.2 1010.40  4988.4 1006.31  4989.2 1004.14  4990.2 1002.14  5009.8 1002.14
  5010.8 1004.14  5024.6 1014.07  5045.8 1013.08  5127.3 1013.83  5256.5 1011.92
  5381.8 1013.08  5440.5 1015.53  5478.1 1018.69  5544.5 1028.31  5608.2 1034.97
#Mann=3,-1,0
  4660.2    0.12       0  4989.2    0.04       0  5010.8    0.12       0
Bank Sta=4989.2,5010.8
XS Rating Curve= 0
Exp/Cntr=0.3,0.1

Type RM Length L Ch R = 1,88917,342,342,342
BEGIN DESCRIPTION:
North Hunting Creek 155.0
END DESCRIPTION:
XS GIS Cut Line= 4
      1448405.57       871317.37      1448311.15       871301.64
      1447966.77       871291.80      1447525.98       871181.60
#Sta/Elev= 30
  4840.7 1040.26  4857.5 1036.32  4895.0 1024.74  4905.4 1022.12  4915.3 1016.93
  4928.6 1011.99  4938.1 1011.11  4951.9 1011.91  4974.0 1010.05  4989.2 1003.43
  4990.2 1001.43  5009.8 1001.43  5010.8 1003.43  5016.9 1011.81  5103.5 1010.47
  5143.1 1011.09  5175.3 1012.99  5239.7 1018.24  5267.1 1019.57  5323.0 1018.67
  5387.8 1015.28  5418.5 1014.77  5439.5 1014.92  5478.4 1016.71  5552.2 1018.87
  5584.3 1020.61  5599.8 1022.17  5627.1 1025.36  5664.0 1030.85  5735.3 1038.29
#Mann=3,-1,0
  4840.7    0.12       0  4989.2    0.04       0  5010.8    0.12       0
Bank Sta=4989.2,5010.8
XS Rating Curve= 0
Exp/Cntr=0.3,0.1

Type RM Length L Ch R = 1,88575,464,464,464
BEGIN DESCRIPTION:
North Hunting Creek 154.5
END DESCRIPTION:
XS GIS Cut Line= 5
      1448126.17       871047.03      1448114.75       871129.83
      1448057.61       871258.40      1447963.33       871286.97
      1447526.15       871169.82
#Sta/Elev= 30
  4903.5 1025.59  4914.5 1024.61  4967.0 1015.23  4985.6 1016.44  4987.0 1016.14
  4987.1 1016.02  4989.2 1002.13  4990.2 1000.13  5009.8 1000.13  5010.8 1002.13
  5033.8 1010.85  5076.5 1009.84  5094.3 1010.52  5135.4 1013.36  5198.2 1018.51
  5219.4 1019.72  5265.6 1018.70  5326.7 1015.57  5367.5 1014.60  5386.6 1015.21
  5435.1 1017.75  5476.8 1018.62  5523.2 1020.47  5556.1 1023.85  5609.5 1031.13
  5619.8 1031.95  5635.4 1033.97  5660.8 1036.41  5672.4 1037.29  5678.9 1037.34
#Mann=3,-1,0
  4903.5    0.12       0  4989.2    0.04       0  5010.8    0.12       0
Bank Sta=4989.2,5010.8
XS Rating Curve= 0
Exp/Cntr=0.3,0.1