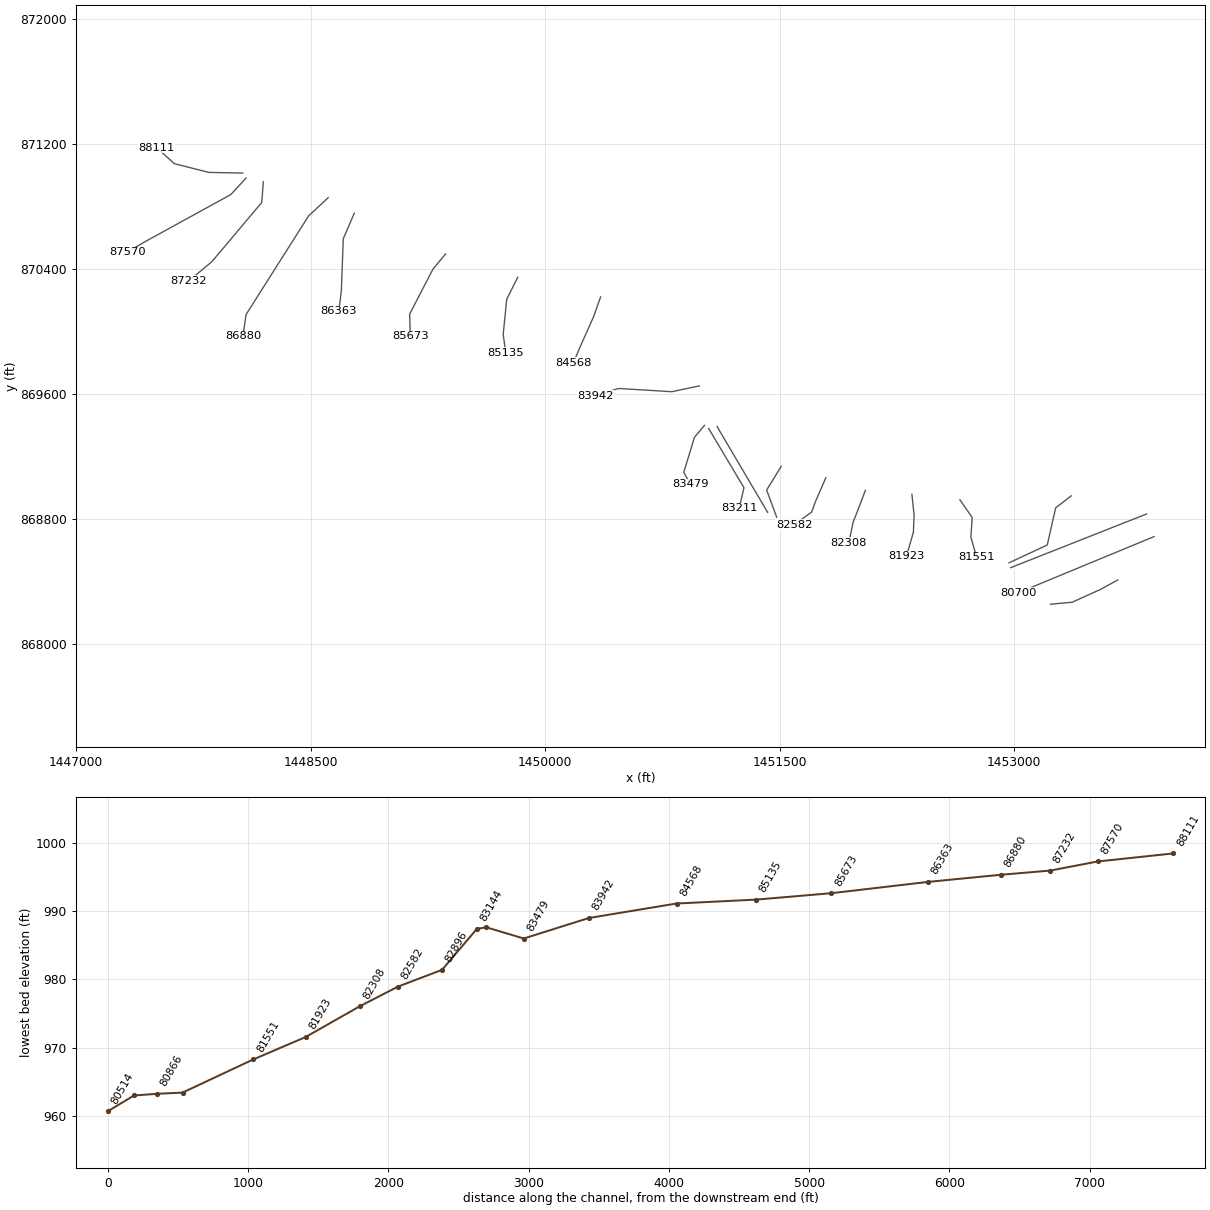
HEC-RAS study North Little Hunting Creek.prj: North Little Hunting Creek Limited Detail Study

--- North Little Hunting Creek.g01 (geometry) --- (continued)

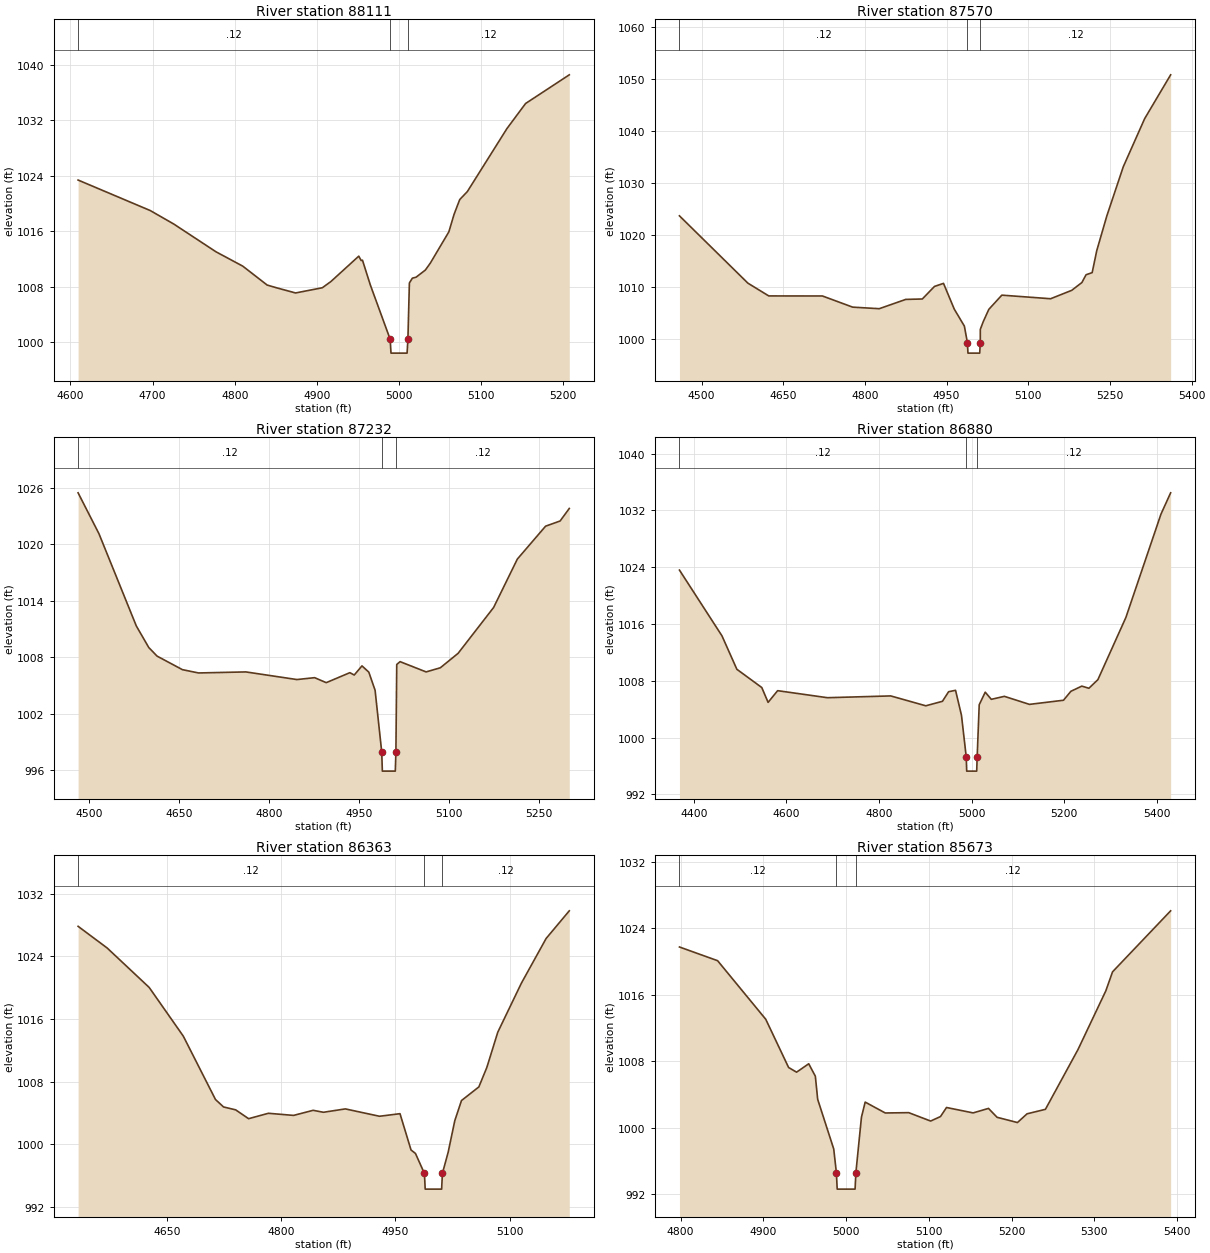
Type RM Length L Ch R = 1,88111,541,541,541
BEGIN DESCRIPTION:
North Hunting Creek 154.0
END DESCRIPTION:
XS GIS Cut Line= 4
      1448064.32       871015.87      1447848.97       871020.01
      1447627.42       871075.92      1447513.53       871179.45
#Sta/Elev= 30
  4609.4 1023.38  4697.2 1018.98  4725.9 1017.03  4777.2 1013.03  4809.8 1010.96
  4839.5 1008.23  4852.3 1007.79  4874.1 1007.09  4906.6 1007.84  4917.0 1008.73
  4951.0 1012.40  4953.9 1011.77  4955.5 1011.82  4965.0 1008.27  4989.2 1000.41
  4990.2  998.41  5009.8  998.41  5010.8 1000.41  5012.6 1008.53  5016.2 1009.22
  5020.8 1009.37  5032.0 1010.39  5038.1 1011.40  5060.6 1015.90  5067.0 1018.44
  5073.9 1020.57  5083.1 1021.71  5131.3 1030.80  5154.0 1034.42  5207.2 1038.56
#Mann=3,-1,0
  4609.4    0.12       0  4989.2    0.04       0  5010.8    0.12       0
#XS Ineff=2,0
    0.00 4951.00 1012.40               0
Permanent Ineff=
       F       F
Bank Sta=4989.2,5010.8
XS Rating Curve= 0
Exp/Cntr=0.3,0.1

Type RM Length L Ch R = 1,87570,338,338,338
BEGIN DESCRIPTION:
North Hunting Creek 153.5
END DESCRIPTION:
XS GIS Cut Line= 4
      1448086.17       870984.11      1447989.04       870878.41
      1447443.34       870578.42      1447326.21       870509.85
#Sta/Elev= 30
  4459.4 1023.68  4585.1 1010.71  4623.4 1008.25  4722.0 1008.24  4777.5 1006.09
  4826.3 1005.79  4874.9 1007.58  4905.4 1007.66  4927.7 1010.08  4944.3 1010.67
  4964.0 1005.72  4982.6 1002.44  4988.2  999.23  4989.2  997.23  5010.8  997.23
  5011.8  999.23  5011.9 1001.82  5017.3 1003.30  5027.5 1005.66  5051.4 1008.40
  5141.0 1007.71  5179.8 1009.33  5198.4 1010.83  5206.1 1012.33  5217.3 1012.74
  5225.7 1016.97  5244.2 1023.66  5274.4 1033.13  5313.7 1042.41  5361.4 1050.85
#Mann=3,-1,0
  4459.4    0.12       0  4988.2    0.04       0  5011.8    0.12       0
#XS Ineff=2,0
    0.00 4944.30 1010.67               0
Permanent Ineff=
       F       F
Bank Sta=4988.2,5011.8
XS Rating Curve= 0
Exp/Cntr=0.3,0.1

Type RM Length L Ch R = 1,87232,352,352,352
BEGIN DESCRIPTION:
North Hunting Creek 153.0
END DESCRIPTION:
XS GIS Cut Line= 4
      1448196.85       870959.98      1448186.49       870827.44
      1447867.61       870448.51      1447720.63       870326.37
#Sta/Elev= 30
  4481.7 1025.44  4516.5 1021.10  4578.8 1011.31  4599.6 1009.02  4613.4 1008.11
  4655.7 1006.67  4682.6 1006.32  4761.5 1006.43  4846.7 1005.62  4876.2 1005.82
  4895.6 1005.29  4935.0 1006.35  4942.3 1006.10  4955.2 1007.07  4966.6 1006.41
  4977.1 1004.48  4988.2  997.90  4989.2  995.90  5010.8  995.90  5011.8  997.90
  5013.2 1007.22  5018.8 1007.52  5062.2 1006.43  5085.9 1006.87  5115.5 1008.40
  5174.8 1013.27  5214.4 1018.41  5261.5 1021.90  5285.7 1022.45  5301.0 1023.78
#Mann=3,-1,0
  4481.7    0.12       0  4988.2    0.04       0  5011.8    0.12       0
Bank Sta=4988.2,5011.8
XS Rating Curve= 0
Exp/Cntr=0.3,0.1

Type RM Length L Ch R = 1,86880,517,517,517
BEGIN DESCRIPTION:
North Hunting Creek 152.5
END DESCRIPTION:
XS GIS Cut Line= 4
      1448611.87       870858.41      1448486.17       870741.27
      1448086.18       870109.86      1448066.18       869969.85
#Sta/Elev= 30
  4368.9 1023.60  4460.7 1014.34  4492.9 1009.63  4546.7 1007.06  4560.3 1004.97
  4580.9 1006.62  4688.4 1005.63  4825.2 1005.88  4900.8 1004.49  4936.8 1005.12
  4950.1 1006.47  4965.1 1006.67  4977.9 1003.16  4988.2  997.29  4989.2  995.29
  5010.8  995.29  5011.8  997.29  5016.2 1004.63  5029.2 1006.41  5042.3 1005.40
  5070.6 1005.82  5124.7 1004.69  5198.2 1005.27  5214.2 1006.53  5237.7 1007.26
  5253.1 1006.96  5272.5 1008.17  5332.9 1016.92  5408.7 1031.48  5429.6 1034.48
#Mann=3,-1,0
  4368.9    0.12       0  4988.2    0.04       0  5011.8    0.12       0
Bank Sta=4988.2,5011.8
XS Rating Curve= 0
Exp/Cntr=0.3,0.1

Type RM Length L Ch R = 1,86363,690,690,690
BEGIN DESCRIPTION:
North Hunting Creek 152.0
END DESCRIPTION:
XS GIS Cut Line= 4
      1448778.70       870759.13      1448708.29       870595.53
      1448695.87       870262.15      1448679.30       870129.60
#Sta/Elev= 30
  4533.2 1027.83  4571.4 1025.06  4626.6 1020.02  4671.4 1013.80  4713.7 1005.70
  4724.3 1004.75  4740.2 1004.38  4757.2 1003.25  4783.2 1003.94  4816.3 1003.67
  4842.0 1004.32  4855.5 1004.07  4884.3 1004.50  4929.2 1003.56  4956.1 1003.89
  4970.6  999.25  4976.4  998.81  4988.2  996.25  4989.2  994.25  5010.8  994.25
  5011.8  996.25  5019.4  998.97  5028.1 1003.00  5036.9 1005.57  5059.7 1007.31
  5070.2 1009.80  5084.6 1014.31  5115.6 1020.57  5148.1 1026.28  5178.5 1029.81
#Mann=3,-1,0
  4533.2    0.12       0  4988.2    0.04       0  5011.8    0.12       0
Bank Sta=4988.2,5011.8
XS Rating Curve= 0
Exp/Cntr=0.3,0.1

Type RM Length L Ch R = 1,85673,538,538,538
BEGIN DESCRIPTION:
North Hunting Creek 151.0
END DESCRIPTION:
XS GIS Cut Line= 4
      1449362.60       870498.18      1449281.86       870400.89
      1449132.78       870113.07      1449136.92       869970.20
#Sta/Elev= 30
  4798.6 1021.73  4844.7 1020.08  4902.9 1013.03  4930.5 1007.23  4940.1 1006.67
  4954.8 1007.68  4962.8 1006.18  4965.6 1003.41  4985.0  997.43  4988.2  994.60
  4989.2  992.60  5010.8  992.60  5011.8  994.60  5018.5 1001.25  5023.0 1003.07
  5047.3 1001.76  5075.6 1001.80  5102.1 1000.79  5114.0 1001.33  5121.3 1002.42
  5153.4 1001.77  5172.0 1002.31  5182.4 1001.24  5207.0 1000.61  5218.6 1001.66
  5240.8 1002.20  5280.2 1009.40  5313.8 1016.46  5321.9 1018.74  5392.1 1026.08
#Mann=3,-1,0
  4798.6    0.12       0  4988.2    0.04       0  5011.8    0.12       0
Bank Sta=4988.2,5011.8
XS Rating Curve= 0
Exp/Cntr=0.3,0.1

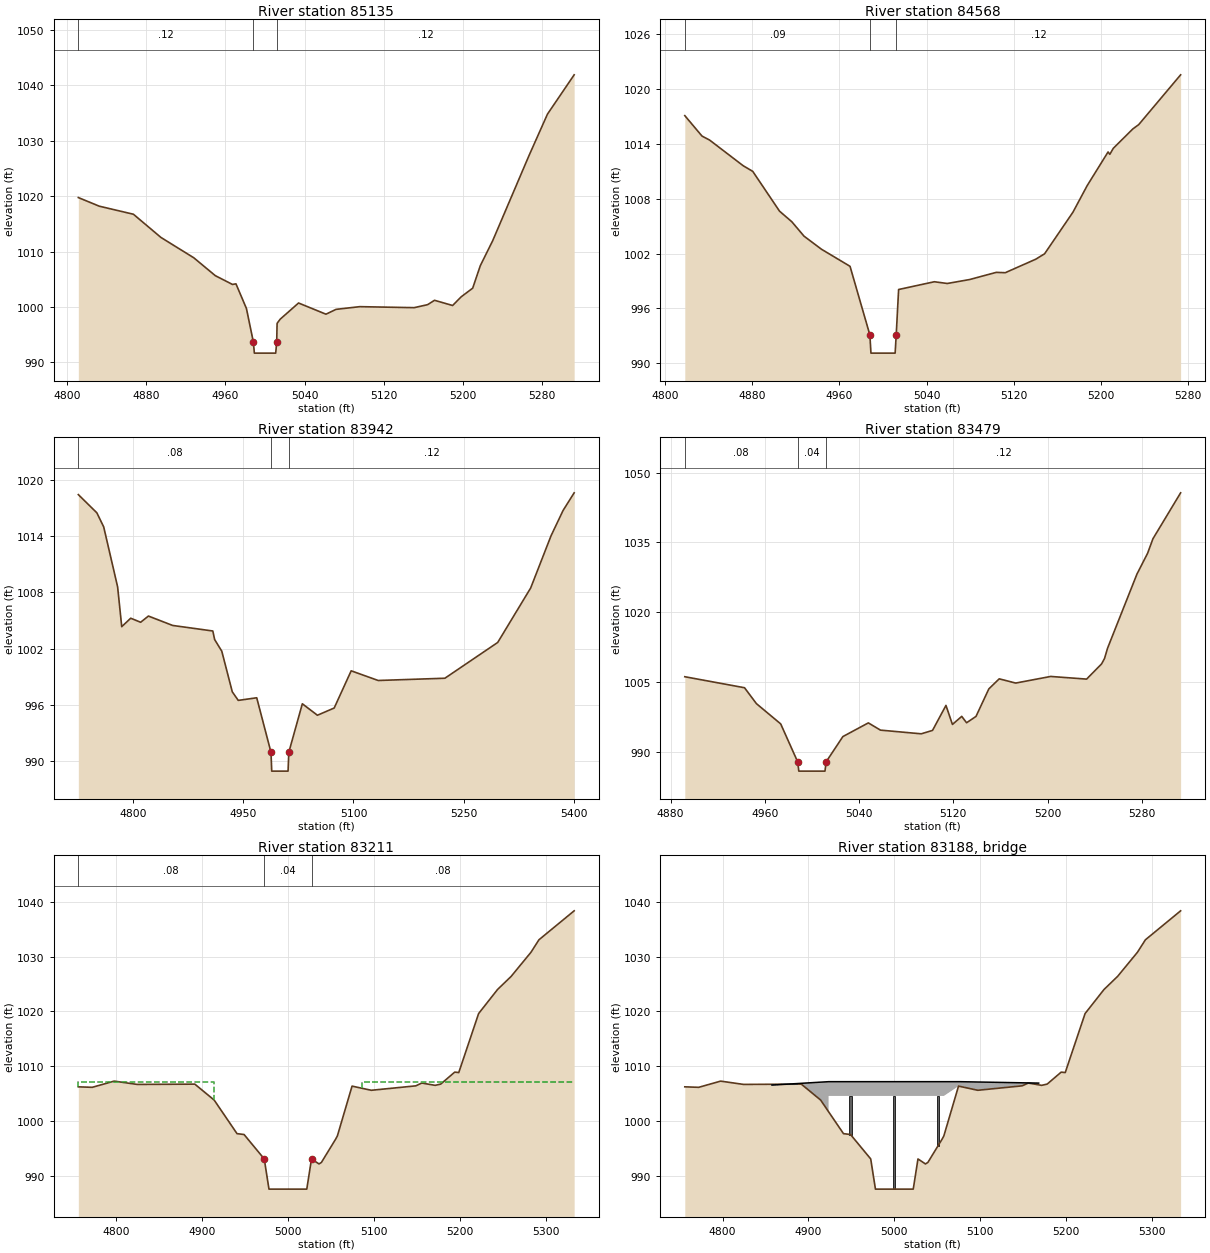
Type RM Length L Ch R = 1,85135,567,567,567
BEGIN DESCRIPTION:
North Hunting Creek 150.0
END DESCRIPTION:
XS GIS Cut Line= 4
      1449824.35       870349.08      1449753.97       870208.32
      1449731.19       869982.62      1449747.76       869866.62
#Sta/Elev= 30
  4811.2 1019.75  4832.4 1018.19  4866.9 1016.74  4894.8 1012.54  4928.0 1008.87
  4949.7 1005.65  4967.1 1004.06  4970.6 1004.17  4981.2  999.72  4988.2  993.66
  4989.2  991.66  5010.8  991.66  5011.8  993.66  5012.2  997.04  5015.4  997.80
  5033.9 1000.71  5061.6  998.69  5071.8  999.56  5095.7 1000.05  5150.8  999.87
  5164.4 1000.41  5171.4 1001.20  5189.7 1000.26  5198.3 1001.82  5210.0 1003.39
  5217.7 1007.45  5230.3 1011.99  5266.8 1027.27  5285.6 1034.81  5312.6 1041.91
#Mann=3,-1,0
  4811.2    0.12       0  4988.2    0.04       0  5011.8    0.12       0
Bank Sta=4988.2,5011.8
XS Rating Curve= 0
Exp/Cntr=0.3,0.1

Type RM Length L Ch R = 1,84568,626,626,626
BEGIN DESCRIPTION:
North Hunting Creek 149.0
END DESCRIPTION:
XS GIS Cut Line= 4
      1450354.46       870222.83      1450308.90       870094.43
      1450230.22       869918.43      1450180.52       869802.46
#Sta/Elev= 30
  4818.0 1017.11  4833.8 1014.87  4840.8 1014.43  4871.5 1011.63  4880.4 1011.00
  4905.0 1006.64  4916.2 1005.49  4927.5 1003.90  4943.5 1002.47  4969.7 1000.60
  4987.9  993.09  4988.9  991.09  5011.1  991.09  5012.1  993.09  5014.3  998.06
  5047.1  998.91  5059.0  998.72  5079.4  999.15  5104.0  999.94  5112.2  999.90
  5140.2 1001.38  5148.3 1001.97  5174.4 1006.54  5187.4 1009.44  5206.6 1013.13
  5208.2 1012.87  5211.4 1013.53  5229.4 1015.66  5234.7 1016.12  5273.2 1021.58
#Mann=3,-1,0
  4818.0    0.09       0  4987.9    0.04       0  5012.1    0.12       0
Bank Sta=4987.9,5012.1
XS Rating Curve= 0
Exp/Cntr=0.3,0.1

Type RM Length L Ch R = 1,83942,463,463,463
BEGIN DESCRIPTION:
North Hunting Creek 148.0
END DESCRIPTION:
XS GIS Cut Line= 4
      1450985.97       869653.37      1450810.00       869616.11
      1450470.41       869636.82      1450323.40       869591.26
#Sta/Elev= 30
  4726.0 1018.41  4751.2 1016.47  4760.5 1014.97  4779.4 1008.59  4785.0 1004.35
  4797.2 1005.25  4810.7 1004.82  4821.3 1005.48  4854.2 1004.48  4908.8 1003.89
  4911.3 1002.98  4921.0 1001.74  4935.3  997.41  4943.4  996.50  4968.5  996.78
  4987.9  990.97  4988.9  988.97  5011.1  988.97  5012.1  990.97  5030.5  996.14
  5051.0  994.92  5073.8  995.69  5096.9  999.65  5133.6  998.62  5224.3  998.86
  5296.1 1002.67  5340.9 1008.47  5368.6 1014.03  5385.0 1016.73  5400.0 1018.60
#Mann=3,-1,0
  4726.0    0.08       0  4987.9    0.04       0  5012.1    0.12       0
Bank Sta=4987.9,5012.1
XS Rating Curve= 0
Exp/Cntr=0.3,0.1

Type RM Length L Ch R = 1,83479,268,268,268
BEGIN DESCRIPTION:
North Hunting Creek 147.0
END DESCRIPTION:
XS GIS Cut Line= 4
      1451019.13       869400.76      1450954.95       869324.15
      1450886.61       869100.52      1450928.04       869023.88
#Sta/Elev= 30
  4892.1 1006.22  4942.8 1003.86  4952.9 1000.45  4973.5  996.11  4987.9  987.98
  4988.9  985.98  5011.1  985.98  5012.1  987.98  5026.3  993.39  5047.9  996.32
  5058.2  994.77  5092.8  993.98  5102.4  994.71  5113.8 1000.07  5119.3  995.99
  5127.2  997.72  5131.3  996.35  5139.3  997.71  5150.2 1003.61  5159.0 1005.77
  5173.0 1004.86  5202.7 1006.28  5233.2 1005.71  5245.9 1008.97  5248.4 1010.13
  5251.0 1012.35  5275.9 1028.21  5285.0 1032.71  5289.5 1035.80  5313.0 1045.65
#Mann=3,-1,0
  4892.1    0.08       0  4987.9    0.04       0  5012.1    0.12       0
#XS Ineff=2,0
       0                 5113.80    0.00 1000.07
Permanent Ineff=
       F       F
Bank Sta=4987.9,5012.1
XS Rating Curve= 0
Exp/Cntr=0.5,0.3

Type RM Length L Ch R = 1,83211,67,67,67
BEGIN DESCRIPTION:
Mayberry Mill Rd - US
END DESCRIPTION:
XS GIS Cut Line= 3
      1451046.08       869380.01      1451271.75       869001.13
      1451240.70       868868.62
#Sta/Elev= 30
  4756.1 1006.26  4772.3 1006.17  4797.8 1007.30  4824.5 1006.70  4891.7 1006.75
  4914.2 1003.85  4940.8  997.73  4949.0  997.57  4972.5  993.12  4978.0  987.62
  5022.0  987.62  5027.5  993.12  5036.2  992.21  5039.0  992.48  5055.6  996.73
  5057.6  997.31  5074.7 1006.39  5097.1 1005.63  5148.9 1006.44  5155.9 1006.95
  5171.4 1006.53  5177.9 1006.76  5194.2 1008.94  5198.9 1008.86  5222.0 1019.61
  5244.0 1023.99  5259.9 1026.39  5282.9 1030.77  5292.2 1033.05  5333.2 1038.33
#Mann=3,-1,0
  4756.1    0.08       0  4972.5    0.04       0  5027.5    0.08       0
#XS Ineff=2,0
    0.00 4913.50 1007.12 5086.50    0.00 1007.17
Permanent Ineff=
       F       F
Bank Sta=4972.5,5027.5
XS Rating Curve= 0
Exp/Cntr=0.5,0.3

Type RM Length L Ch R =3,83188,,,
BEGIN DESCRIPTION:
Mayberry Mill Rd - TOR
Structure ID: LDS_NLHC_13
Approximate Survey Structure
END DESCRIPTION:
Bridge Culvert--1,0,-1,-1,0
Deck Dist Width WeirC Skew NumUp NumDn MinLoCord MaxHiCord MaxSubmerge Is_Ogee
9.5,27,3,,6,6,,,,0,1,1,,,
  4857.6  4923.5  4923.5  5076.5  5076.5  5168.0
 1006.58 1007.20 1007.20 1007.20 1007.20 1006.94
  967.62  967.62 1004.60 1004.60  967.62  967.62
  4857.6  4923.5  4923.5  5076.5  5076.5  5168.0
 1006.58 1007.20 1007.20 1007.20 1007.20 1006.94
  967.62  967.62 1004.60 1004.60  967.62  967.62
Pier Skew, UpSta & Num, DnSta & Num=,4949,2,4949,2,0,0,0,0,0
     2.5     2.5
  997.57 1004.60
     2.5     2.5
  996.11 1004.60
Pier Skew, UpSta & Num, DnSta & Num=,5000,2,5000,2,0,0,0,0,0
     2.5     2.5
  988.70 1004.60
     2.5     2.5
  988.45 1004.60
Pier Skew, UpSta & Num, DnSta & Num=,5051,2,5051,2,0,0,0,0,0
     2.5     2.5
  995.54 1004.60
     2.5     2.5
  992.17 1004.60
Abutment Skew #Up #Dn=,2,2
  4923.5  4944.5
 1004.60  997.41
  4923.5  4944.5
 1004.60  998.09
Abutment Skew #Up #Dn=,2,2
  5055.5  5076.5
  996.73 1004.60
  5055.5  5076.5
  993.51 1004.60
BR Coef=1,1,0,1.25,0,,,0.8,0,2,0,
WSPro=,,,, 1 ,,,, 0 ,,,, 0 ,,,,-1 ,-1 ,-1 , 0 , 0 , 0 , 0 , 0
BC Design=,,0,,0,,,,,,

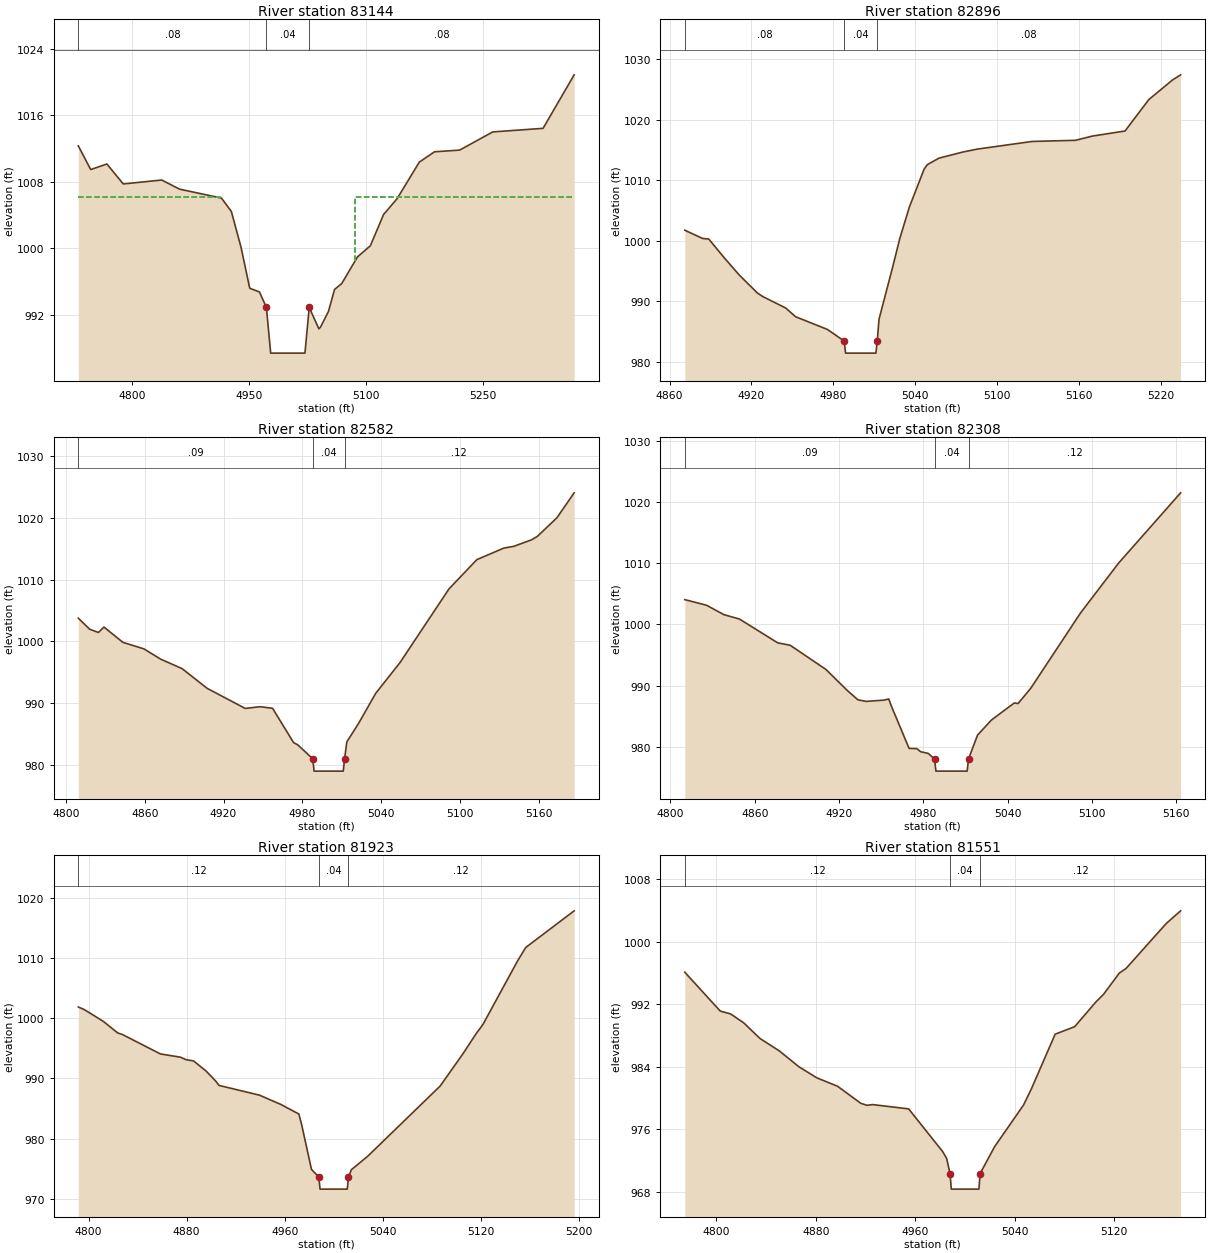
Type RM Length L Ch R = 1,83144,248,248,248
BEGIN DESCRIPTION:
Mayberry Mill Rd - DS
END DESCRIPTION:
XS GIS Cut Line= 2
      1451099.91       869392.45      1451422.91       868843.76
#Sta/Elev= 30
  4731.0 1012.31  4746.9 1009.46  4767.7 1010.13  4788.7 1007.73  4838.1 1008.20
  4861.1 1007.10  4914.8 1006.03  4927.5 1004.42  4939.9 1000.12  4951.1  995.18
  4963.6  994.73  4972.5  992.87  4978.0  987.37  5022.0  987.37  5027.5  992.87
  5039.9  990.29  5042.0  990.50  5052.2  992.39  5060.0  995.03  5069.3  995.75
  5089.4  998.94  5106.0 1000.29  5122.9 1004.04  5140.5 1005.98  5168.9 1010.36
  5188.4 1011.60  5220.6 1011.80  5263.2 1013.99  5327.8 1014.42  5367.7 1020.86
#Mann=3,-1,0
  4731.0    0.08       0  4972.5    0.04       0  5027.5    0.08       0
#XS Ineff=2,0
    0.00 4913.50 1006.10 5086.50    0.00 1006.10
Permanent Ineff=
       F       F
Bank Sta=4972.5,5027.5
XS Rating Curve= 0
Exp/Cntr=0.5,0.3

Type RM Length L Ch R = 1,82896,314,314,314
BEGIN DESCRIPTION:
North Little Hunting Creek 146.0
END DESCRIPTION:
XS GIS Cut Line= 3
      1451509.90       869137.82      1451416.70       868986.63
      1451480.89       868812.70
#Sta/Elev= 30
  4871.2 1001.73  4884.3 1000.36  4888.7 1000.28  4900.2  997.14  4911.1  994.31
  4924.3  991.36  4928.1  990.78  4945.1  988.86  4952.3  987.42  4975.5  985.33
  4987.9  983.40  4988.9  981.40  5011.1  981.40  5012.1  983.40  5013.4  987.01
  5023.6  995.82  5028.6 1000.36  5035.6 1005.55  5046.4 1011.83  5048.8 1012.58
  5057.3 1013.65  5074.8 1014.66  5085.2 1015.14  5125.5 1016.41  5157.3 1016.60
  5169.6 1017.30  5193.5 1018.14  5210.9 1023.33  5228.2 1026.57  5234.2 1027.43
#Mann=3,-1,0
  4871.2    0.08       0  4987.9    0.04       0  5012.1    0.08       0
Bank Sta=4987.9,5012.1
XS Rating Curve= 0
Exp/Cntr=0.3,0.1

Type RM Length L Ch R = 1,82582,274,274,274
BEGIN DESCRIPTION:
North Little Hunting Creek 145.5
END DESCRIPTION:
XS GIS Cut Line= 4
      1451795.59       869065.83      1451728.96       868912.68
      1451704.42       868844.89      1451592.20       868764.24
#Sta/Elev= 30
  4809.5 1003.76  4818.1 1001.97  4824.8 1001.44  4829.0 1002.32  4843.4  999.84
  4859.4  998.78  4872.1  997.12  4888.5  995.57  4907.6  992.37  4936.5  989.12
  4947.9  989.40  4957.3  989.14  4973.3  983.58  4976.5  983.21  4987.9  980.95
  4988.9  978.95  5011.1  978.95  5012.1  980.95  5013.8  983.69  5022.7  986.67
  5035.8  991.57  5054.4  996.59  5091.6 1008.52  5112.8 1013.26  5133.3 1015.13
  5140.7 1015.40  5154.3 1016.46  5158.7 1017.01  5173.6 1020.02  5186.8 1024.09
#Mann=3,-1,0
  4809.5    0.09       0  4987.9    0.04       0  5012.1    0.12       0
Bank Sta=4987.9,5012.1
XS Rating Curve= 0
Exp/Cntr=0.3,0.1

Type RM Length L Ch R = 1,82308,385,385,385
BEGIN DESCRIPTION:
North Hunting Creek 145.0
END DESCRIPTION:
XS GIS Cut Line= 4
      1452048.25       868984.58      1452006.83       868874.82
      1451969.56       868779.57      1451942.64       868649.11
#Sta/Elev= 30
  4810.2 1004.05  4825.7 1003.13  4838.0 1001.60  4849.1 1000.88  4876.3  997.00
  4885.2  996.60  4910.6  992.66  4926.2  989.14  4933.4  987.70  4939.2  987.44
  4952.0  987.65  4955.3  987.84  4957.6  986.44  4969.8  979.77  4975.3  979.73
  4978.0  979.23  4983.4  978.95  4987.9  978.06  4988.9  976.06  5011.1  976.06
  5012.1  978.06  5018.5  981.94  5028.1  984.33  5029.8  984.64  5044.6  987.18
  5047.4  987.10  5056.5  989.63  5091.7 1001.85  5118.9 1010.02  5163.0 1021.48
#Mann=3,-1,0
  4810.2    0.09       0  4987.9    0.04       0  5012.1    0.12       0
Bank Sta=4987.9,5012.1
XS Rating Curve= 0
Exp/Cntr=0.3,0.1

Type RM Length L Ch R = 1,81923,372,372,372
BEGIN DESCRIPTION:
North Hunting Creek 144.5
END DESCRIPTION:
XS GIS Cut Line= 4
      1452346.08       868959.44      1452360.11       868823.85
      1452355.44       868716.32      1452311.02       868562.03
#Sta/Elev= 30
  4791.7 1001.89  4796.5 1001.47  4811.9  999.53  4823.8  997.58  4827.6  997.32
  4858.7  994.08  4875.0  993.54  4879.5  993.13  4885.8  992.91  4896.0  991.22
  4903.7  989.58  4906.5  988.84  4939.5  987.22  4957.1  985.66  4971.6  984.08
  4973.8  982.40  4981.9  974.86  4987.9  973.58  4988.9  971.58  5011.1  971.58
  5012.1  973.58  5014.4  974.80  5027.7  977.04  5086.9  988.74  5105.5  994.12
  5116.4  997.50  5121.8  998.99  5150.0 1009.55  5156.7 1011.80  5196.2 1017.90
#Mann=3,-1,0
  4791.7    0.12       0  4987.9    0.04       0  5012.1    0.12       0
Bank Sta=4987.9,5012.1
XS Rating Curve= 0
Exp/Cntr=0.3,0.1

Type RM Length L Ch R = 1,81551,505,505,505
BEGIN DESCRIPTION:
North Hunting Creek 144.0
END DESCRIPTION:
XS GIS Cut Line= 4
      1452652.87       868924.53      1452731.56       868810.63
      1452723.28       868684.32      1452760.55       868555.94
#Sta/Elev= 30
  4774.6  996.08  4803.1  991.11  4811.4  990.75  4822.0  989.60  4835.0  987.61
  4850.7  986.00  4866.3  983.99  4880.8  982.56  4897.3  981.50  4916.1  979.31
  4921.1  979.05  4925.7  979.14  4954.6  978.59  4981.8  973.16  4985.1  972.28
  4987.9  970.32  4988.9  968.32  5011.1  968.32  5012.1  970.32  5023.7  973.75
  5047.0  979.09  5053.3  981.15  5072.4  988.15  5088.1  989.11  5105.3  992.30
  5111.2  993.23  5124.0  995.97  5129.4  996.56  5161.8 1002.33  5173.3 1003.94
#Mann=3,-1,0
  4774.6    0.12       0  4987.9    0.04       0  5012.1    0.12       0
Bank Sta=4987.9,5012.1
XS Rating Curve= 0
Exp/Cntr=0.3,0.1

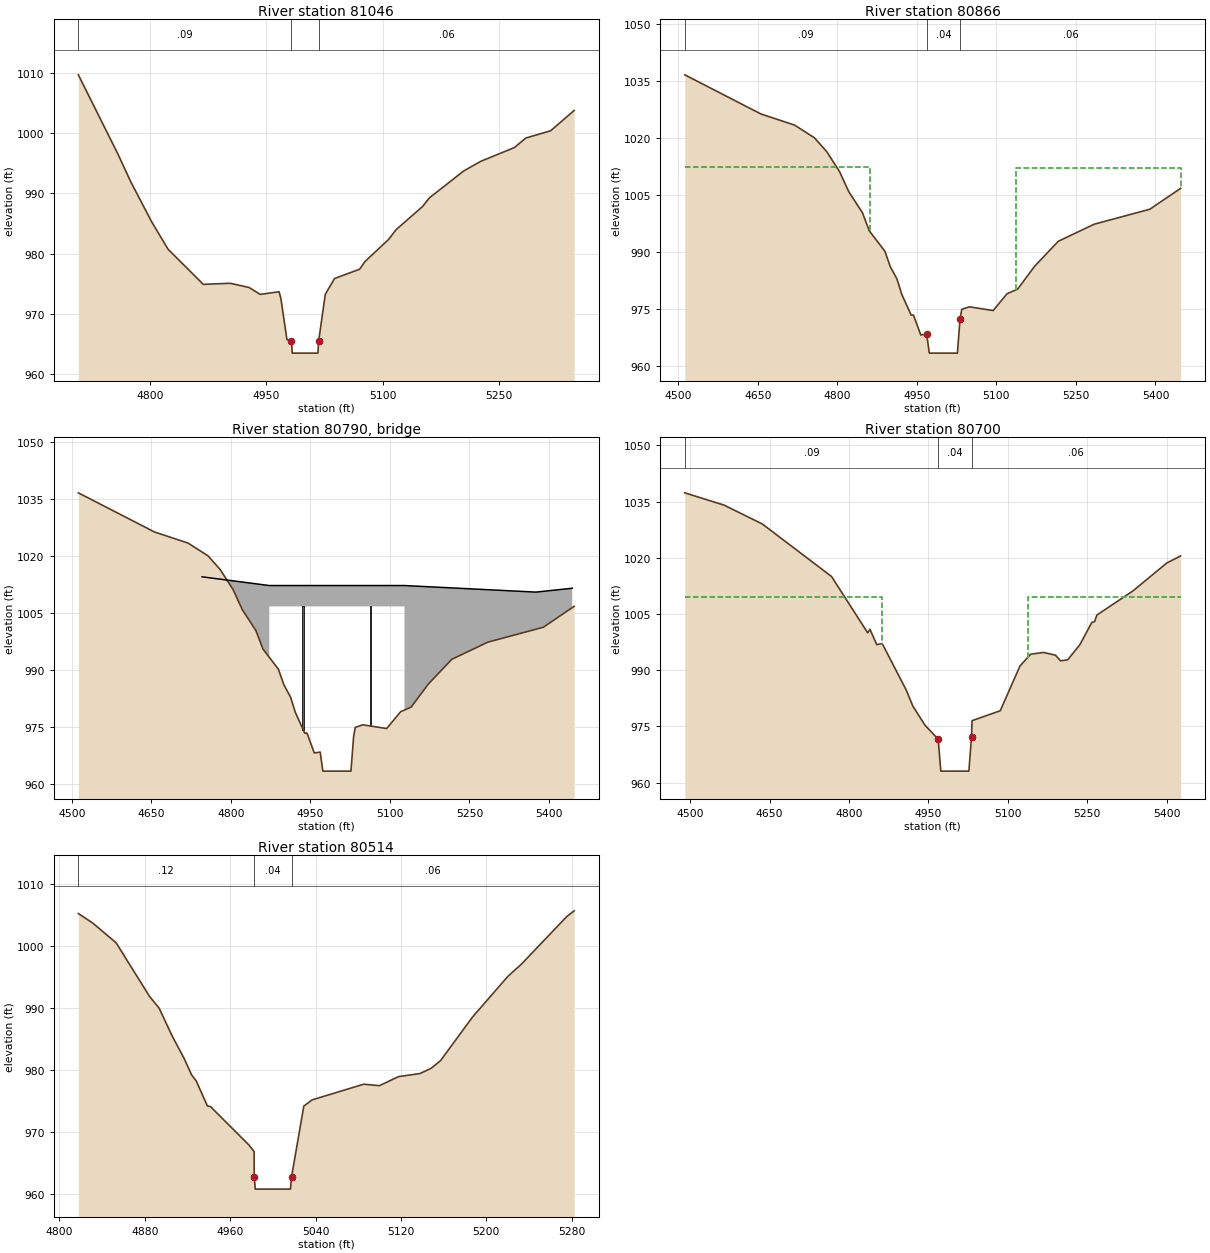
Type RM Length L Ch R = 1,81046,180,180,180
BEGIN DESCRIPTION:
North Hunting Creek 143.0
END DESCRIPTION:
XS GIS Cut Line= 4
      1453365.19       868949.37      1453265.79       868872.75
      1453211.95       868634.62      1452967.63       868520.74
#Sta/Elev= 30
  4707.7 1009.72  4759.1  996.46  4775.2  991.97  4802.4  985.26  4823.4  980.73
  4868.8  974.90  4903.6  975.08  4927.8  974.38  4942.1  973.23  4966.5  973.67
  4968.9  972.50  4976.6  965.73  4982.5  965.47  4983.5  963.47  5016.5  963.47
  5017.5  965.47  5026.1  973.25  5038.0  975.87  5070.4  977.42  5077.3  978.70
  5107.9  982.39  5117.2  983.97  5151.4  987.83  5160.4  989.29  5204.5  993.74
  5226.5  995.35  5269.8  997.63  5284.7  999.22  5316.5 1000.42  5346.9 1003.79
#Mann=3,-1,0
  4707.7    0.09       0  4982.5    0.04       0  5017.5    0.06       0
Bank Sta=4982.5,5017.5
XS Rating Curve= 0
Exp/Cntr=0.5,0.3

Type RM Length L Ch R = 1,80866,166,166,166
BEGIN DESCRIPTION:
Winsor Rd - US
END DESCRIPTION:
XS GIS Cut Line= 2
      1453847.68       868833.42      1452977.95       868489.67
#Sta/Elev= 30
  4512.3 1036.63  4655.7 1026.33  4719.4 1023.38  4756.9 1020.03  4779.9 1016.42
  4804.3 1011.10  4821.4 1005.89  4847.4 1000.28  4860.5  995.48  4889.7  990.15
  4899.8  986.11  4912.5  982.83  4921.5  978.82  4939.3  973.30  4943.6  973.33
  4957.4  968.08  4968.5  968.32  4973.5  963.30  5026.5  963.30  5031.5  972.40
  5034.7  974.84  5049.0  975.50  5093.9  974.52  5120.2  978.96  5140.1  980.17
  5172.2  986.20  5216.8  992.77  5284.5  997.27  5389.5 1001.22  5447.5 1006.72
#Mann=3,-1,0
  4512.3    0.09       0  4968.5    0.04       0  5031.5    0.06       0
#XS Ineff=2,0
    0.00 4862.50 1012.42 5137.50    0.00 1012.13
Permanent Ineff=
       F       F
Bank Sta=4968.5,5031.5
XS Rating Curve= 0
Exp/Cntr=0.5,0.3

Type RM Length L Ch R =3,80790,,,
BEGIN DESCRIPTION:
Winsor Rd - TOR
Structure ID: LDS_NLHC_09
Approximate Survey Structure
END DESCRIPTION:
Bridge Culvert--1,0,-1,-1,0
Deck Dist Width WeirC Skew NumUp NumDn MinLoCord MaxHiCord MaxSubmerge Is_Ogee
60,32,3,,7,7,,,,0,1,1,,,
  4745.7  4872.5  4872.5  5127.5  5127.5  5375.6  5443.9
 1014.50 1012.20 1012.20 1012.20 1012.20 1010.47 1011.49
  943.30  943.30 1006.70 1006.70  943.30  943.30  943.30
  4745.7  4872.5  4872.5  5127.5  5127.5  5375.6  5443.9
 1014.50 1012.20 1012.20 1012.20 1012.20 1010.47 1011.49
  943.30  943.30 1006.70 1006.70  943.30  943.30  943.30
Pier Skew, UpSta & Num, DnSta & Num=,4936.3,2,4936.3,2,0,0,0,0,0
     2.5     2.5
  974.15 1006.70
     2.5     2.5
  976.94 1006.70
Pier Skew, UpSta & Num, DnSta & Num=,5063.8,2,5063.8,2,0,0,0,0,0
     2.5     2.5
  975.19 1006.70
     2.5     2.5
  977.92 1006.70
Abutment Skew #Up #Dn=,2,2
  4872.5  4922.5
 1006.70  978.55
  4872.5  4922.5
 1006.70  979.98
Abutment Skew #Up #Dn=,2,2
  5077.5  5127.5
  975.40 1006.70
  5077.5  5127.5
  978.94 1006.70
BR Coef=1,1,0,1.25,0,,,0.8,0,2,0,
WSPro=,,,, 1 ,,,, 0 ,,,, 0 ,,,,-1 ,-1 ,-1 , 0 , 0 , 0 , 0 , 0
BC Design=,,0,,0,,,,,,

Type RM Length L Ch R = 1,80700,186,186,186
BEGIN DESCRIPTION:
Winsor Rd - DS
END DESCRIPTION:
XS GIS Cut Line= 2
      1453895.29       868688.47      1453029.69       868330.22
#Sta/Elev= 30
  4489.8 1037.36  4564.3 1034.06  4636.6 1029.01  4767.1 1015.01  4835.4  999.97
  4839.6 1000.93  4852.5  996.82  4862.7  997.13  4908.1  984.72  4920.8  980.38
  4943.6  975.31  4968.5  971.60  4973.5  963.05  5026.5  963.05  5031.5  972.15
  5032.5  976.52  5085.8  979.17  5123.1  991.12  5143.2  994.27  5167.7  994.74
  5190.2  994.00  5199.7  992.50  5213.3  992.78  5236.1  996.79  5259.0 1002.78
  5264.1 1002.97  5268.3 1004.71  5336.6 1011.18  5400.4 1018.62  5426.6 1020.50
#Mann=3,-1,0
  4489.8    0.09       0  4968.5    0.04       0  5031.5    0.06       0
#XS Ineff=2,0
    0.00 4862.50 1009.50 5137.50    0.00 1009.50
Permanent Ineff=
       F       F
Bank Sta=4968.5,5031.5
XS Rating Curve= 0
Exp/Cntr=0.5,0.3

Type RM Length L Ch R = 1,80514,575,575,575
BEGIN DESCRIPTION:
North Hunting Creek 142.0
END DESCRIPTION:
XS GIS Cut Line= 4
      1453663.36       868411.00      1453553.61       868350.95
      1453371.39       868268.12      1453232.61       868255.69
#Sta/Elev= 30
  4817.7 1005.30  4831.3 1003.74  4853.1 1000.57  4884.3  991.93  4893.4  990.01
  4905.5  985.55  4916.9  981.85  4923.8  979.23  4928.2  978.23  4938.6  974.20
  4941.6  974.08  4977.5  967.89  4982.4  966.82  4982.5  962.75  4983.5  960.75
  5016.5  960.75  5017.5  962.75  5029.0  974.17  5036.7  975.17  5085.1  977.71
  5099.9  977.47  5117.6  978.93  5138.0  979.44  5148.5  980.30  5157.1  981.52
  5187.0  988.55  5220.2  995.14  5232.9  997.12  5275.3 1004.79  5282.3 1005.73
#Mann=3,-1,0
  4817.7    0.12       0  4982.5    0.04       0  5017.5    0.06       0
Bank Sta=4982.5,5017.5
XS Rating Curve= 0
Exp/Cntr=0.3,0.1