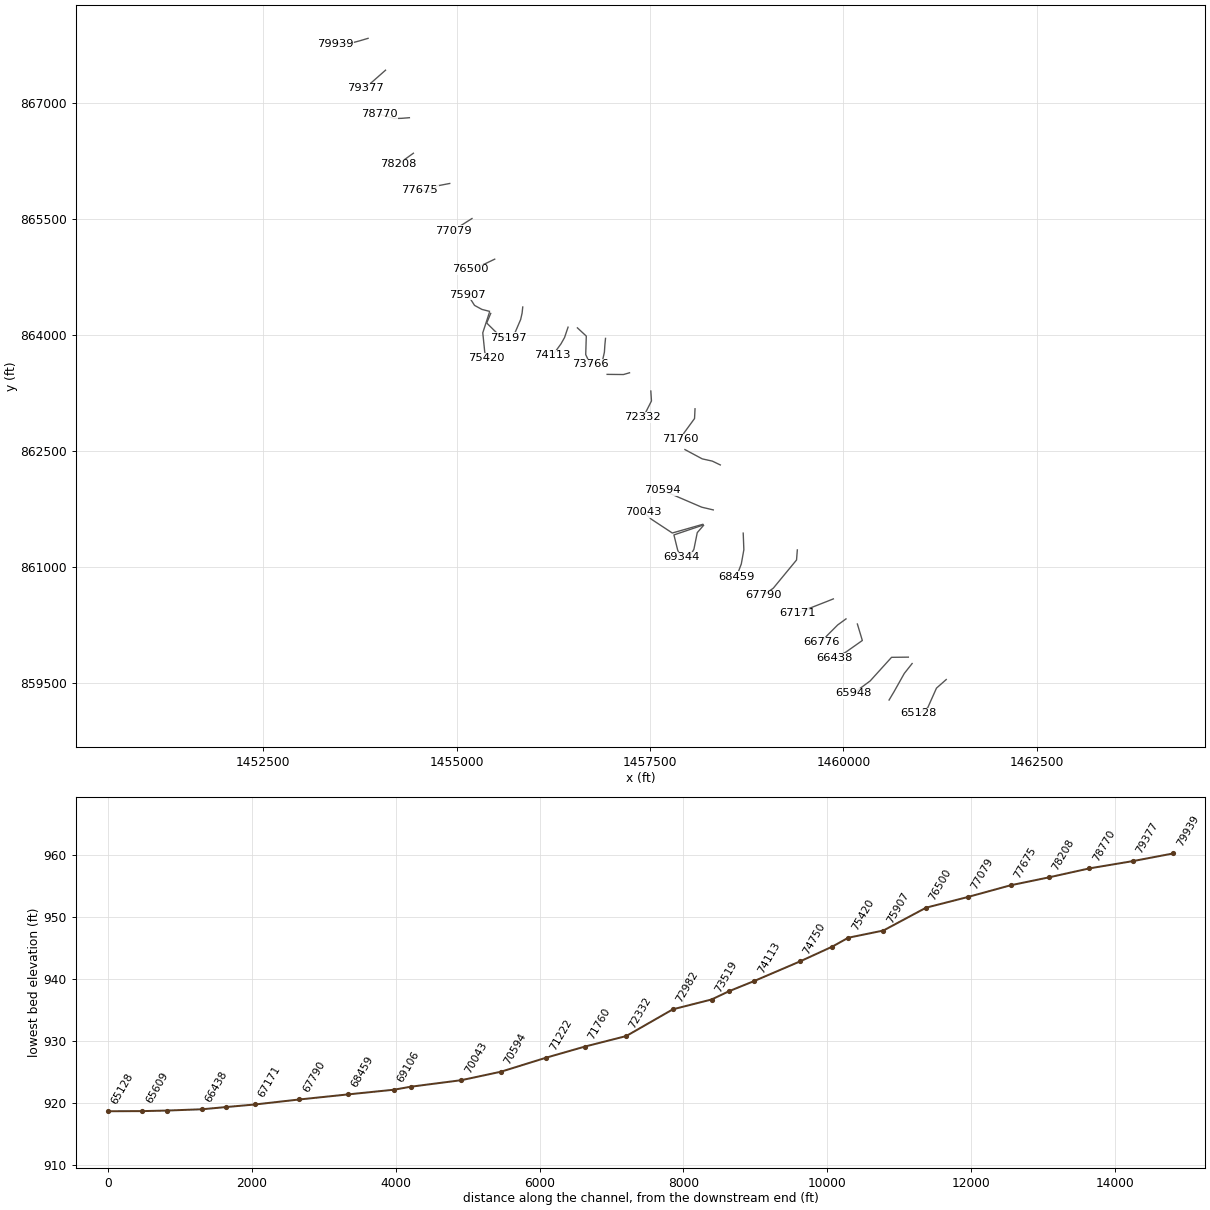
HEC-RAS study North Little Hunting Creek.prj: North Little Hunting Creek Limited Detail Study

--- North Little Hunting Creek.g01 (geometry) --- (continued)

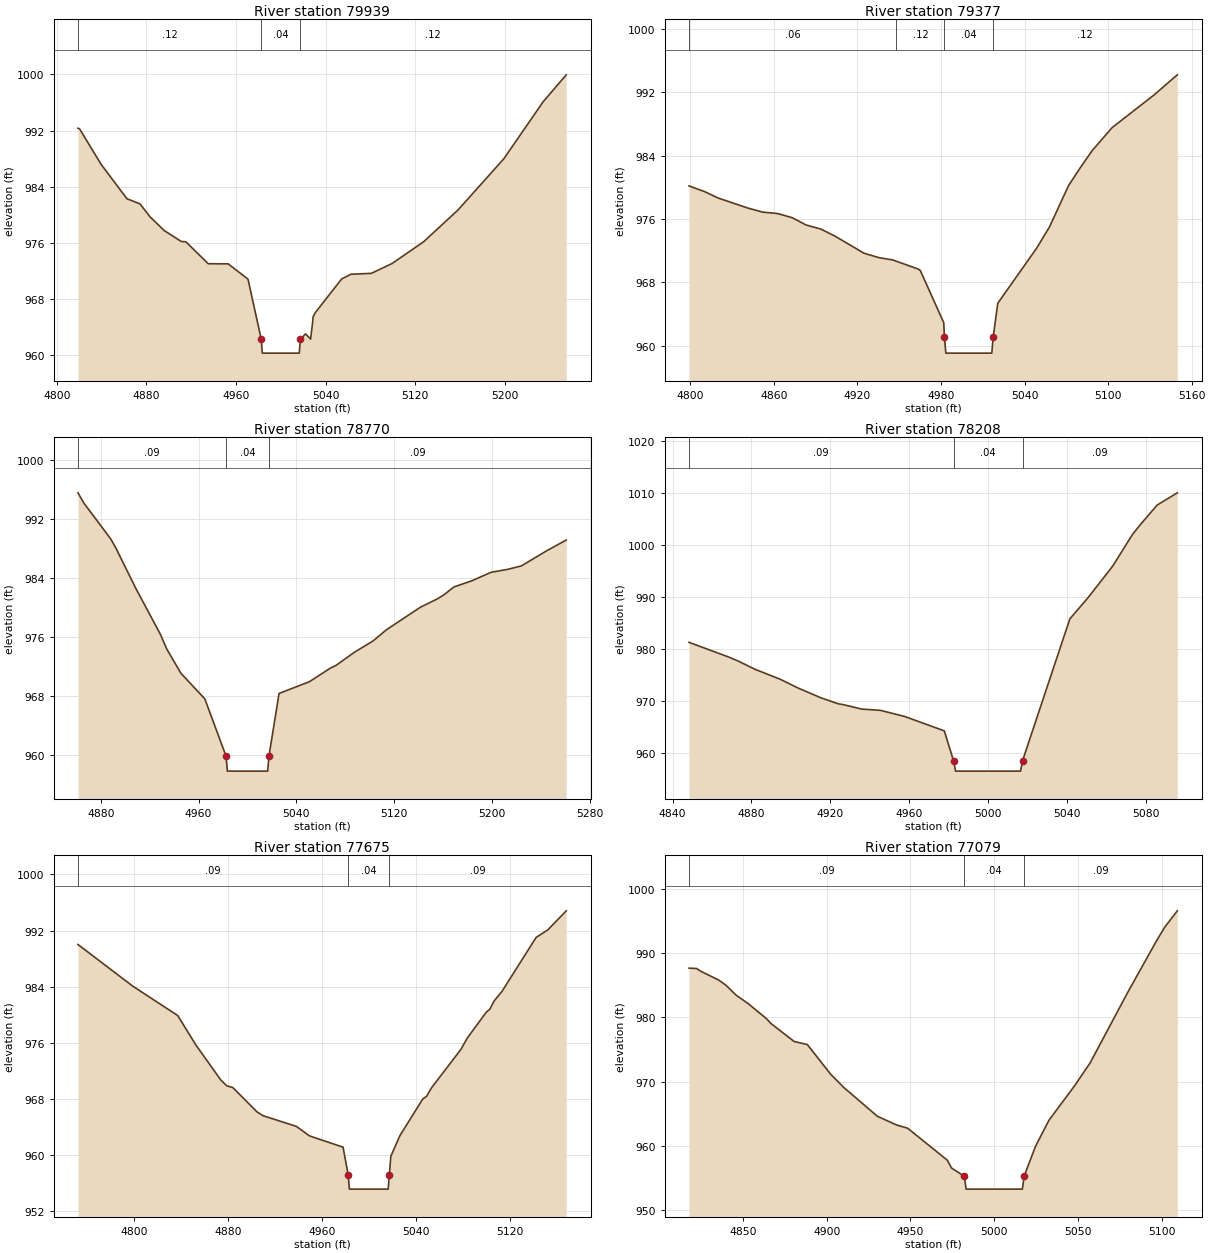
Type RM Length L Ch R = 1,79939,562,562,562
BEGIN DESCRIPTION:
North Hunting Creek 141.0
END DESCRIPTION:
XS GIS Cut Line= 4
      1453853.87       867839.50      1453742.04       867806.37
      1453601.23       867769.09      1453427.34       867771.16
#Sta/Elev= 30
  4818.8  992.32  4820.2  992.25  4839.5  987.18  4862.6  982.28  4874.2  981.56
  4883.3  979.69  4895.9  977.75  4911.1  976.20  4915.2  976.15  4935.2  973.03
  4953.0  973.01  4970.7  970.84  4982.5  962.30  4983.5  960.30  5016.5  960.30
  5017.5  962.30  5022.2  963.04  5026.6  962.30  5028.4  964.63  5028.9  965.48
  5030.7  966.04  5054.3  970.85  5062.6  971.53  5080.9  971.66  5099.4  973.06
  5127.6  976.16  5158.4  980.70  5199.2  987.97  5234.5  996.12  5255.0  999.93
#Mann=3,-1,0
  4818.8    0.12       0  4982.5    0.04       0  5017.5    0.12       0
Bank Sta=4982.5,5017.5
XS Rating Curve= 0
Exp/Cntr=0.3,0.1

Type RM Length L Ch R = 1,79377,607,607,607
BEGIN DESCRIPTION:
North Hunting Creek 140.0
END DESCRIPTION:
XS GIS Cut Line= 2
      1454079.54       867427.43      1453816.59       867195.53
#Sta/Elev= 30
  4799.1  980.19  4810.2  979.48  4820.0  978.66  4841.6  977.38  4852.0  976.88
  4862.7  976.70  4873.3  976.17  4883.2  975.25  4893.6  974.75  4903.8  973.86
  4924.7  971.69  4935.6  971.12  4945.3  970.84  4948.0  970.67  4963.9  969.67
  4965.2  969.49  4982.0  962.91  4982.5  961.06  4983.5  959.06  5016.5  959.06
  5017.5  961.06  5020.8  965.36  5048.7  972.32  5058.0  975.03  5071.6  980.22
  5080.0  982.48  5088.7  984.68  5102.9  987.56  5133.1  991.70  5149.7  994.23
#Mann=4,-1,0
  4799.1    0.06       0  4948.0    0.12       0  4982.5    0.04       0
  5017.5    0.12       0
Bank Sta=4982.5,5017.5
XS Rating Curve= 0
Exp/Cntr=0.3,0.1

Type RM Length L Ch R = 1,78770,562,562,562
BEGIN DESCRIPTION:
North Hunting Creek 139.0
END DESCRIPTION:
XS GIS Cut Line= 4
      1454388.05       866812.45      1454284.55       866804.17
      1454195.51       866802.10      1453996.72       866858.01
#Sta/Elev= 30
  4861.3  995.54  4866.2  994.14  4888.0  989.33  4892.2  988.11  4908.6  982.62
  4928.8  976.37  4933.9  974.42  4945.5  971.13  4965.1  967.65  4982.5  959.88
  4983.5  957.88  5016.5  957.88  5017.5  959.88  5025.8  968.39  5050.6  969.98
  5067.6  971.80  5072.3  972.18  5087.4  973.96  5102.6  975.49  5113.8  977.03
  5141.5  980.07  5155.3  981.19  5160.5  981.72  5168.8  982.80  5183.5  983.64
  5199.3  984.79  5212.7  985.18  5224.0  985.65  5244.6  987.69  5260.7  989.15
#Mann=3,-1,0
  4861.3    0.09       0  4982.5    0.04       0  5017.5    0.09       0
Bank Sta=4982.5,5017.5
XS Rating Curve= 0
Exp/Cntr=0.3,0.1

Type RM Length L Ch R = 1,78208,533,533,533
BEGIN DESCRIPTION:
North Hunting Creek 138.0
END DESCRIPTION:
XS GIS Cut Line= 3
      1454439.84       866352.77      1454344.59       866284.44
      1454238.98       866207.82
#Sta/Elev= 24
  4848.3  981.24  4868.7  978.37  4873.5  977.59  4881.6  976.08  4894.6  974.12
  4903.5  972.46  4915.1  970.57  4924.0  969.40  4926.4  969.25  4936.0  968.38
  4945.5  968.13  4957.6  966.97  4977.8  964.19  4982.5  958.43  4983.5  956.43
  5016.5  956.43  5017.5  958.43  5041.5  985.76  5050.7  989.83  5063.3  995.96
  5073.2 1001.99  5077.2 1003.89  5085.8 1007.69  5096.0 1010.04
#Mann=3,-1,0
  4848.3    0.09       0  4982.5    0.04       0  5017.5    0.09       0
Bank Sta=4982.5,5017.5
XS Rating Curve= 0
Exp/Cntr=0.3,0.1

Type RM Length L Ch R = 1,77675,596,596,596
BEGIN DESCRIPTION:
North Hunting Creek 137.0
END DESCRIPTION:
XS GIS Cut Line= 4
      1454909.88       865961.42      1454758.72       865932.43
      1454642.77       865853.75      1454522.69       865874.45
#Sta/Elev= 30
  4752.3  990.02  4799.1  984.07  4837.3  979.89  4852.8  975.68  4874.1  970.68
  4879.1  969.87  4884.2  969.63  4904.8  966.16  4910.1  965.61  4938.4  964.09
  4949.5  962.74  4978.1  961.13  4982.5  957.15  4983.5  955.15  5016.5  955.15
  5017.5  957.15  5018.8  959.83  5026.6  962.80  5046.0  968.00  5049.2  968.37
  5053.4  969.58  5078.4  975.05  5084.0  976.70  5100.0  980.35  5103.2  980.82
  5106.7  981.96  5113.5  983.34  5142.5  991.02  5152.6  992.12  5168.2  994.82
#Mann=3,-1,0
  4752.3    0.09       0  4982.5    0.04       0  5017.5    0.09       0
Bank Sta=4982.5,5017.5
XS Rating Curve= 0
Exp/Cntr=0.3,0.1

Type RM Length L Ch R = 1,77079,579,579,579
BEGIN DESCRIPTION:
North Hunting Creek 136.0
END DESCRIPTION:
XS GIS Cut Line= 3
      1455197.70       865507.94      1455106.59       865449.97
      1454951.26       865352.63
#Sta/Elev= 30
  4817.9  987.69  4822.4  987.63  4825.1  987.18  4835.5  985.85  4839.8  985.06
  4846.0  983.48  4853.1  982.18  4864.2  979.80  4866.7  979.08  4880.6  976.26
  4888.5  975.78  4902.4  971.16  4910.3  969.08  4930.3  964.60  4941.8  963.24
  4948.3  962.75  4972.0  957.76  4974.5  956.54  4982.2  955.25  4983.2  953.25
  5016.8  953.25  5017.8  955.25  5024.6  959.91  5032.6  963.97  5047.8  969.31
  5057.2  972.92  5079.5  983.85  5096.9  991.99  5101.6  994.03  5109.2  996.62
#Mann=3,-1,0
  4817.9    0.09       0  4982.2    0.04       0  5017.8    0.09       0
Bank Sta=4982.2,5017.8
XS Rating Curve= 0
Exp/Cntr=0.3,0.1

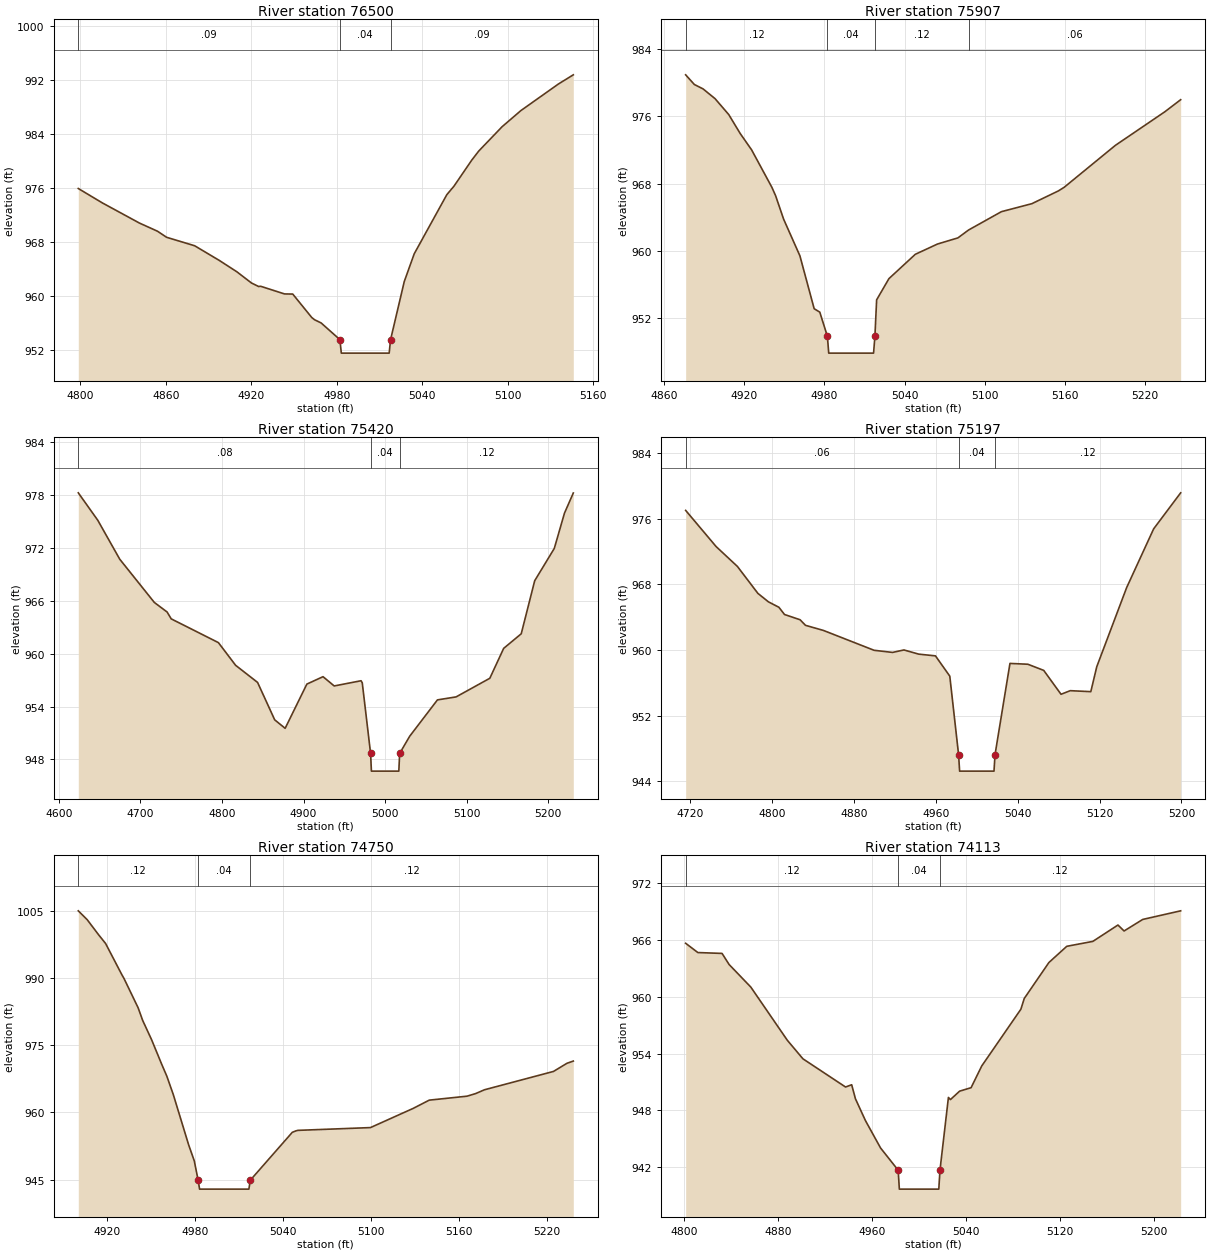
Type RM Length L Ch R = 1,76500,593,593,593
BEGIN DESCRIPTION:
North Hunting Creek 135.0
END DESCRIPTION:
XS GIS Cut Line= 3
      1455491.76       864982.01      1455357.14       864917.81
      1455170.81       864849.49
#Sta/Elev= 30
  4798.5  975.89  4815.3  973.77  4841.4  970.78  4854.1  969.57  4860.5  968.67
  4880.2  967.42  4897.5  965.25  4909.9  963.56  4920.1  961.91  4925.1  961.39
  4926.6  961.42  4943.3  960.29  4949.1  960.27  4962.4  956.81  4964.4  956.47
  4969.0  956.00  4982.2  953.53  4983.2  951.53  5016.8  951.53  5017.8  953.53
  5027.4  962.12  5034.4  966.23  5057.3  974.98  5062.3  976.23  5074.8  980.09
  5079.7  981.43  5096.1  985.03  5109.3  987.42  5135.7  991.36  5146.1  992.71
#Mann=3,-1,0
  4798.5    0.09       0  4982.2    0.04       0  5017.8    0.09       0
Bank Sta=4982.2,5017.8
XS Rating Curve= 0
Exp/Cntr=0.3,0.1

Type RM Length L Ch R = 1,75907,487,487,487
BEGIN DESCRIPTION:
North Hunting Creek 134.0
END DESCRIPTION:
XS GIS Cut Line= 4
      1455423.44       864306.96      1455326.08       864331.82
      1455230.83       864383.59      1455143.85       864520.27
#Sta/Elev= 30
  4876.0  980.95  4882.5  979.80  4889.0  979.28  4898.0  978.12  4908.3  976.22
  4916.9  973.96  4925.4  972.03  4940.6  967.57  4943.4  966.57  4949.4  963.78
  4961.6  959.42  4972.3  953.12  4976.5  952.72  4982.2  949.84  4983.2  947.84
  5016.8  947.84  5017.8  949.84  5019.1  954.18  5028.3  956.70  5048.1  959.60
  5064.7  960.82  5080.0  961.55  5088.0  962.49  5112.6  964.67  5135.4  965.62
  5155.3  967.14  5159.7  967.58  5198.0  972.56  5235.0  976.55  5246.9  977.99
#Mann=4,-1,0
  4876.0    0.12       0  4982.2    0.04       0  5017.8    0.12       0
  5088.0    0.06       0
Bank Sta=4982.2,5017.8
XS Rating Curve= 0
Exp/Cntr=0.3,0.1

Type RM Length L Ch R = 1,75420,223,223,223
BEGIN DESCRIPTION:
North Hunting Creek 133.5
END DESCRIPTION:
XS GIS Cut Line= 4
      1455421.85       864288.77      1455337.14       864028.67
      1455362.40       863783.44      1455380.23       863698.77
#Sta/Elev= 30
  4624.0  978.21  4647.9  975.10  4674.8  970.69  4717.2  965.79  4732.8  964.71
  4737.9  963.93  4795.7  961.24  4816.8  958.67  4843.7  956.73  4864.7  952.49
  4877.5  951.53  4904.1  956.54  4923.9  957.38  4937.6  956.33  4970.5  956.92
  4972.0  956.68  4982.2  948.68  4983.2  946.68  5016.8  946.68  5017.8  948.68
  5030.1  950.63  5064.1  954.75  5087.0  955.09  5128.3  957.20  5145.3  960.59
  5166.8  962.24  5183.3  968.25  5207.3  971.91  5219.8  975.91  5230.6  978.19
#Mann=3,-1,0
  4624.0    0.08       0  4982.2    0.04       0  5017.8    0.12       0
Bank Sta=4982.2,5017.8
XS Rating Curve= 0
Exp/Cntr=0.3,0.1

Type RM Length L Ch R = 1,75197,447,447,447
BEGIN DESCRIPTION:
North Hunting Creek 133.0
END DESCRIPTION:
XS GIS Cut Line= 4
      1455439.96       864280.04      1455388.20       864155.81
      1455568.35       863977.74      1455663.60       863967.38
#Sta/Elev= 30
  4715.5  977.00  4745.3  972.59  4766.1  970.17  4786.1  966.89  4796.4  965.86
  4806.6  965.20  4812.1  964.32  4827.3  963.68  4832.6  963.00  4850.1  962.38
  4899.6  959.96  4917.7  959.70  4928.8  960.00  4943.3  959.49  4959.6  959.28
  4973.6  956.81  4982.2  947.24  4983.2  945.24  5016.8  945.24  5017.8  947.24
  5032.4  958.36  5049.9  958.26  5065.4  957.51  5082.3  954.60  5091.3  955.04
  5111.4  954.92  5117.2  957.95  5146.4  967.59  5172.8  974.75  5199.2  979.14
#Mann=3,-1,0
  4715.5    0.06       0  4982.2    0.04       0  5017.8    0.12       0
#XS Ineff=2,0
       0                 5032.40    0.00  958.36
Permanent Ineff=
       F       F
Bank Sta=4982.2,5017.8
XS Rating Curve= 0
Exp/Cntr=0.3,0.1

Type RM Length L Ch R = 1,74750,637,637,637
BEGIN DESCRIPTION:
North Hunting Creek 132.0
END DESCRIPTION:
XS GIS Cut Line= 4
      1455854.10       864362.89      1455845.81       864284.19
      1455827.18       864201.37      1455758.84       864041.92
#Sta/Elev= 30
  4900.5 1005.00  4906.6 1003.01  4914.5  999.59  4919.1  997.72  4930.1  990.80
  4931.6  989.94  4941.3  983.35  4944.4  980.53  4950.5  976.21  4957.4  970.72
  4960.9  968.05  4965.3  963.95  4975.7  952.79  4979.6  949.15  4982.2  944.86
  4983.2  942.86  5016.8  942.86  5017.8  944.86  5046.4  955.54  5048.8  955.86
  5050.2  955.98  5099.7  956.60  5128.8  960.88  5139.8  962.73  5165.5  963.61
  5171.4  964.19  5177.4  965.04  5224.5  969.14  5233.7  970.96  5238.0  971.45
#Mann=3,-1,0
  4900.5    0.12       0  4982.2    0.04       0  5017.8    0.12       0
Bank Sta=4982.2,5017.8
XS Rating Curve= 0
Exp/Cntr=0.3,0.1

Type RM Length L Ch R = 1,74113,347,347,347
BEGIN DESCRIPTION:
North Hunting Creek 131.0
END DESCRIPTION:
XS GIS Cut Line= 4
      1456440.09       864101.97      1456394.54       863967.39
      1456348.98       863886.63      1456239.24       863735.47
#Sta/Elev= 30
  4801.2  965.67  4811.6  964.69  4832.2  964.60  4838.2  963.43  4856.7  961.04
  4887.8  955.42  4901.1  953.46  4937.4  950.48  4942.6  950.72  4945.8  949.24
  4954.3  946.94  4967.2  944.04  4982.2  941.69  4983.2  939.69  5016.8  939.69
  5017.8  941.69  5025.0  949.38  5026.7  949.15  5034.5  950.04  5044.3  950.41
  5053.4  952.71  5086.7  958.70  5089.6  959.84  5110.6  963.64  5125.8  965.35
  5148.0  965.87  5169.4  967.60  5174.6  966.97  5190.5  968.19  5222.8  969.10
#Mann=3,-1,0
  4801.2    0.12       0  4982.2    0.04       0  5017.8    0.12       0
Bank Sta=4982.2,5017.8
XS Rating Curve= 0
Exp/Cntr=0.3,0.1

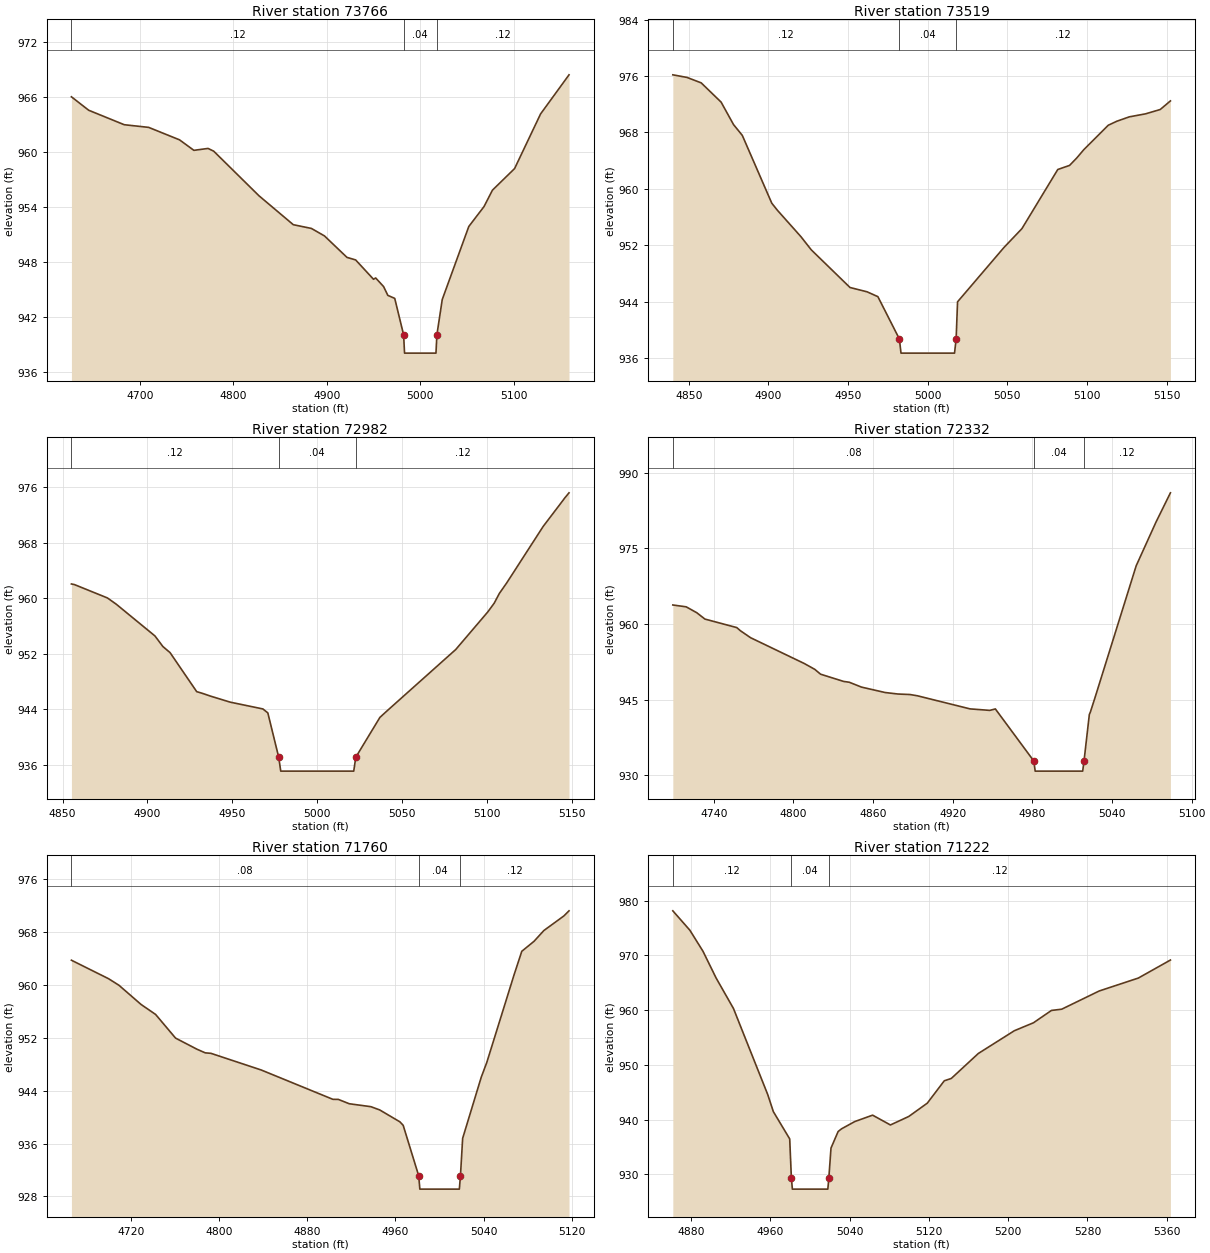
Type RM Length L Ch R = 1,73766,247,247,247
BEGIN DESCRIPTION:
North Little Hunting Creek 130.5
END DESCRIPTION:
XS GIS Cut Line= 4
      1456561.01       864093.04      1456676.05       863986.60
      1456668.53       863746.87      1456726.59       863624.30
#Sta/Elev= 30
  4626.9  966.06  4645.4  964.59  4683.4  963.01  4709.5  962.72  4742.5  961.36
  4757.9  960.21  4773.0  960.42  4779.1  960.12  4827.6  955.24  4864.2  952.09
  4883.6  951.68  4897.6  950.86  4921.6  948.52  4930.9  948.24  4950.0  946.13
  4952.3  946.27  4960.8  945.33  4965.3  944.37  4972.7  944.04  4982.2  940.06
  4983.2  938.06  5016.8  938.06  5017.8  940.06  5023.5  943.91  5051.9  951.89
  5068.2  954.07  5077.2  955.86  5100.9  958.22  5128.7  964.19  5159.1  968.46
#Mann=3,-1,0
  4626.9    0.12       0  4982.2    0.04       0  5017.8    0.12       0
Bank Sta=4982.2,5017.8
XS Rating Curve= 0
Exp/Cntr=0.3,0.1

Type RM Length L Ch R = 1,73519,537,537,537
BEGIN DESCRIPTION:
North Hunting Creek 130.0
END DESCRIPTION:
XS GIS Cut Line= 4
      1456924.62       863957.00      1456916.34       863872.14
      1456910.13       863778.96      1456881.13       863648.49
#Sta/Elev= 30
  4840.0  976.18  4848.9  975.81  4857.8  975.04  4870.3  972.31  4878.1  969.12
  4883.6  967.59  4902.1  957.97  4905.7  956.95  4920.4  953.22  4926.9  951.35
  4951.2  946.01  4961.9  945.40  4968.7  944.71  4982.2  938.70  4983.2  936.70
  5016.8  936.70  5017.8  938.70  5018.7  943.98  5047.8  951.68  5059.1  954.36
  5081.6  962.75  5089.0  963.33  5093.5  964.38  5098.0  965.58  5113.3  969.03
  5118.6  969.59  5126.5  970.22  5136.6  970.64  5145.9  971.26  5152.3  972.48
#Mann=3,-1,0
  4840.0    0.12       0  4982.2    0.04       0  5017.8    0.12       0
Bank Sta=4982.2,5017.8
XS Rating Curve= 0
Exp/Cntr=0.3,0.1

Type RM Length L Ch R = 1,72982,650,650,650
BEGIN DESCRIPTION:
North Hunting Creek 129.0
END DESCRIPTION:
XS GIS Cut Line= 3
      1457235.22       863511.84      1457156.53       863489.07
      1456945.36       863491.14
#Sta/Elev= 28
  4855.2  962.06  4857.0  961.97  4876.4  960.05  4881.6  959.15  4904.4  954.58
  4909.1  953.05  4913.3  952.18  4929.0  946.56  4932.3  946.32  4937.1  945.92
  4948.7  945.05  4968.0  944.07  4970.9  943.50  4977.3  937.12  4978.5  935.12
  5021.5  935.12  5022.7  937.12  5036.9  942.85  5041.1  943.79  5081.6  952.63
  5100.4  958.02  5104.2  959.28  5107.3  960.71  5111.6  962.21  5133.1  970.35
  5145.3  974.27  5145.4  974.32  5148.3  975.18
#Mann=3,-1,0
  4855.2    0.12       0  4977.3    0.04       0  5022.7    0.12       0
Bank Sta=4977.3,5022.7
XS Rating Curve= 0
Exp/Cntr=0.3,0.1

Type RM Length L Ch R = 1,72332,572,572,572
BEGIN DESCRIPTION:
North Hunting Creek 128.0
END DESCRIPTION:
XS GIS Cut Line= 4
      1457510.61       863275.81      1457518.90       863147.41
      1457440.21       862992.11      1457394.65       862936.19
#Sta/Elev= 30
  4709.1  963.78  4719.2  963.41  4727.1  962.25  4733.3  960.98  4757.3  959.29
  4760.0  958.67  4767.7  957.28  4808.2  952.15  4816.1  950.99  4820.4  950.04
  4837.8  948.60  4842.0  948.44  4851.3  947.47  4869.0  946.40  4878.7  946.10
  4887.8  946.00  4893.4  945.75  4933.0  943.15  4947.9  942.85  4952.1  943.14
  4981.1  932.79  4982.1  930.79  5017.9  930.79  5018.9  932.79  5022.9  942.02
  5023.7  942.53  5027.1  945.32  5058.2  971.56  5073.1  980.22  5084.0  986.05
#Mann=3,-1,0
  4709.1    0.08       0  4981.1    0.04       0  5018.9    0.12       0
Bank Sta=4981.1,5018.9
XS Rating Curve= 0
Exp/Cntr=0.3,0.1

Type RM Length L Ch R = 1,71760,538,538,538
BEGIN DESCRIPTION:
North Hunting Creek 127.0
END DESCRIPTION:
XS GIS Cut Line= 4
      1458082.11       863045.92      1458075.90       862919.64
      1457941.31       862735.35      1457895.75       862650.44
#Sta/Elev= 30
  4666.3  963.72  4699.9  960.93  4709.4  959.93  4729.5  957.02  4742.6  955.52
  4760.7  951.94  4780.2  950.25  4787.6  949.71  4792.7  949.64  4838.3  947.12
  4903.3  942.68  4908.2  942.67  4918.2  942.01  4937.7  941.57  4945.7  941.08
  4964.0  939.28  4967.0  938.75  4981.1  931.10  4982.1  929.10  5017.9  929.10
  5018.9  931.10  5020.9  936.78  5037.7  946.00  5042.8  948.27  5067.4  961.46
  5074.5  965.07  5085.6  966.58  5094.5  968.21  5112.6  970.41  5117.3  971.19
#Mann=3,-1,0
  4666.3    0.08       0  4981.1    0.04       0  5018.9    0.12       0
Bank Sta=4981.1,5018.9
XS Rating Curve= 0
Exp/Cntr=0.3,0.1

Type RM Length L Ch R = 1,71222,628,628,628
BEGIN DESCRIPTION:
North Hunting Creek 126.0
END DESCRIPTION:
XS GIS Cut Line= 4
      1458409.32       862319.13      1458305.74       862368.85
      1458175.29       862397.84      1457951.63       862517.95
#Sta/Elev= 30
  4861.4  978.14  4878.6  974.60  4891.8  970.77  4905.1  965.87  4922.6  960.31
  4957.2  944.59  4962.9  941.46  4979.4  936.48  4981.1  929.31  4982.1  927.31
  5017.9  927.31  5018.9  929.31  5021.1  934.81  5028.3  937.83  5031.8  938.33
  5045.1  939.65  5063.1  940.82  5081.1  939.03  5099.7  940.59  5118.3  943.01
  5135.5  947.10  5142.6  947.53  5169.8  952.08  5206.2  956.24  5225.5  957.69
  5243.7  959.95  5254.0  960.17  5291.9  963.50  5331.4  965.86  5363.8  969.15
#Mann=3,-1,0
  4861.4    0.12       0  4981.1    0.04       0  5018.9    0.12       0
Bank Sta=4981.1,5018.9
XS Rating Curve= 0
Exp/Cntr=0.3,0.1

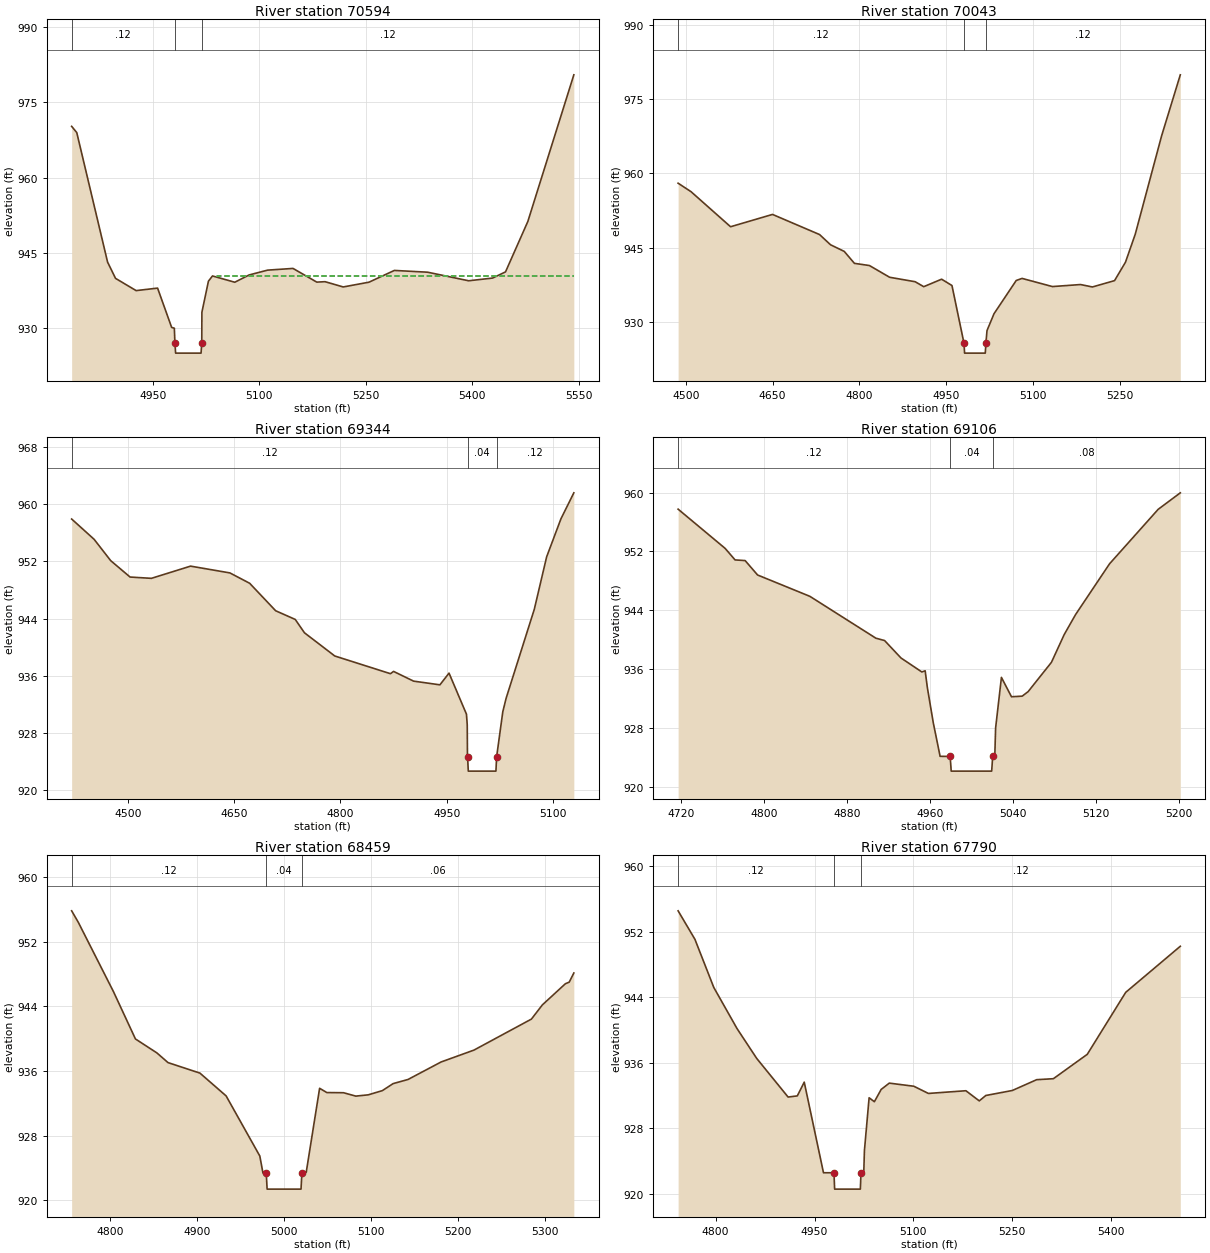
Type RM Length L Ch R = 1,70594,551,551,551
BEGIN DESCRIPTION:
North Hunting Creek 125.0
END DESCRIPTION:
XS GIS Cut Line= 4
      1458318.19       861737.29      1458169.08       861772.50
      1457740.46       861956.79      1457659.67       861989.93
#Sta/Elev= 30
  4835.7  970.21  4842.9  968.97  4886.3  943.17  4897.5  939.93  4926.5  937.49
  4956.7  937.99  4976.5  930.16  4980.3  930.00  4981.1  927.04  4982.1  925.04
  5017.9  925.04  5018.9  927.04  5019.1  933.18  5028.3  939.37  5034.0  940.41
  5065.4  939.16  5085.6  940.61  5111.6  941.57  5147.4  941.91  5180.9  939.18
  5192.5  939.27  5218.1  938.22  5254.4  939.17  5290.1  941.51  5336.8  941.16
  5394.7  939.45  5428.4  939.99  5446.6  941.22  5478.0  951.25  5542.8  980.47
#Mann=3,-1,0
  4835.7    0.12       0  4981.1    0.04       0  5018.9    0.12       0
#XS Ineff=2,0
       0                 5040.10    0.00  940.43
Permanent Ineff=
       F       F
Bank Sta=4981.1,5018.9
XS Rating Curve= 0
Exp/Cntr=0.3,0.1

Type RM Length L Ch R = 1,70043,699,699,699
BEGIN DESCRIPTION:
North Hunting Creek 124.0
END DESCRIPTION:
XS GIS Cut Line= 4
      1458181.85       861550.62      1457788.25       861438.44
      1457516.67       861617.52      1457418.27       861708.05
#Sta/Elev= 30
  4486.8  958.01  4509.2  956.29  4577.5  949.21  4650.0  951.70  4731.4  947.63
  4750.3  945.57  4774.0  944.23  4791.7  941.81  4817.6  941.37  4852.5  939.00
  4896.6  938.10  4911.5  937.10  4942.4  938.61  4960.3  937.33  4981.1  925.67
  4982.1  923.67  5017.9  923.67  5018.9  925.67  5020.9  928.23  5033.0  931.63
  5071.4  938.35  5081.5  938.77  5134.0  937.12  5182.6  937.53  5203.1  937.04
  5241.4  938.32  5260.3  942.04  5277.2  947.70  5322.9  967.63  5355.1  979.91
#Mann=3,-1,0
  4486.8    0.12       0  4981.1    0.04       0  5018.9    0.12       0
Bank Sta=4981.1,5018.9
XS Rating Curve= 0
Exp/Cntr=0.3,0.1

Type RM Length L Ch R = 1,69344,238,238,238
BEGIN DESCRIPTION:
North Hunting Creek 123.5
END DESCRIPTION:
XS GIS Cut Line= 4
      1458189.14       861542.03      1457809.23       861413.56
      1457858.79       861213.49      1457906.52       861123.53
#Sta/Elev= 30
  4420.5  957.94  4452.2  955.10  4475.6  952.11  4503.0  949.81  4533.1  949.63
  4588.4  951.34  4643.9  950.39  4671.8  948.94  4708.5  945.09  4736.2  943.87
  4749.2  942.00  4792.0  938.75  4870.6  936.27  4875.0  936.59  4903.2  935.23
  4940.4  934.71  4953.3  936.35  4977.9  930.60  4979.0  929.09  4979.3  924.63
  4979.5  924.62  4980.5  922.62  5019.5  922.62  5020.5  924.62  5029.2  930.94
  5033.9  932.83  5073.7  945.30  5091.1  952.64  5111.3  957.97  5129.5  961.61
#Mann=3,-1,0
  4420.5    0.12       0  4979.5    0.04       0  5020.5    0.12       0
Bank Sta=4979.5,5020.5
XS Rating Curve= 0
Exp/Cntr=0.3,0.1

Type RM Length L Ch R = 1,69106,647,647,647
BEGIN DESCRIPTION:
North Hunting Creek 123.0
END DESCRIPTION:
XS GIS Cut Line= 4
      1458191.84       861536.42      1458111.10       861443.27
      1458067.62       861227.92      1457997.20       861105.72
#Sta/Elev= 30
  4717.3  957.74  4762.6  952.41  4772.2  950.84  4781.9  950.75  4793.9  948.79
  4844.3  945.89  4907.9  940.20  4916.3  939.88  4932.1  937.51  4952.2  935.61
  4955.4  935.77  4957.5  933.50  4963.2  928.72  4969.8  924.14  4979.5  924.13
  4980.5  922.13  5019.5  922.13  5020.5  924.13  5022.5  924.14  5023.3  927.99
  5028.9  934.87  5038.6  932.24  5048.9  932.32  5054.6  932.93  5077.1  936.92
  5089.4  940.69  5100.4  943.42  5133.1  950.31  5180.0  957.72  5201.3  959.96
#Mann=3,-1,0
  4717.3    0.12       0  4979.5    0.04       0  5020.5    0.08       0
Bank Sta=4979.5,5020.5
XS Rating Curve= 0
Exp/Cntr=0.3,0.1

Type RM Length L Ch R = 1,68459,669,669,669
BEGIN DESCRIPTION:
North Hunting Creek 122.0
END DESCRIPTION:
XS GIS Cut Line= 4
      1458705.38       861437.10      1458713.66       861221.71
      1458680.53       861037.42      1458618.40       860873.82
#Sta/Elev= 30
  4755.6  955.83  4763.3  954.40  4803.9  945.78  4829.0  939.96  4853.7  938.23
  4866.5  937.03  4903.2  935.73  4933.3  932.91  4972.1  925.46  4975.7  923.36
  4979.5  923.36  4980.5  921.36  5019.5  921.36  5020.5  923.36  5025.5  923.45
  5040.9  933.85  5049.2  933.32  5068.4  933.30  5082.6  932.88  5096.9  933.04
  5113.1  933.56  5125.5  934.43  5142.6  934.94  5180.7  937.11  5218.5  938.58
  5284.6  942.42  5297.2  944.18  5323.7  946.80  5328.1  947.00  5333.4  948.13
#Mann=3,-1,0
  4755.6    0.12       0  4979.5    0.04       0  5020.5    0.06       0
Bank Sta=4979.5,5020.5
XS Rating Curve= 0
Exp/Cntr=0.3,0.1

Type RM Length L Ch R = 1,67790,619,619,619
BEGIN DESCRIPTION:
North Hunting Creek 121.0
END DESCRIPTION:
XS GIS Cut Line= 4
      1459405.26       861219.66      1459394.90       861089.19
      1459094.66       860724.75      1458966.28       860631.58
#Sta/Elev= 30
  4743.1  954.55  4768.6  951.07  4797.2  945.19  4832.5  940.16  4862.3  936.52
  4909.9  931.80  4923.9  931.94  4934.4  933.62  4963.6  922.55  4979.5  922.55
  4980.5  920.55  5019.5  920.55  5020.5  922.55  5024.7  922.59  5025.7  925.27
  5032.8  931.71  5040.8  931.23  5051.1  932.73  5063.4  933.50  5100.6  933.12
  5122.7  932.24  5179.6  932.57  5199.9  931.33  5209.8  931.99  5250.0  932.60
  5286.9  933.92  5312.3  934.04  5363.7  937.02  5422.0  944.59  5504.8  950.22
#Mann=3,-1,0
  4743.1    0.12       0  4979.5    0.04       0  5020.5    0.12       0
Bank Sta=4979.5,5020.5
XS Rating Curve= 0
Exp/Cntr=0.3,0.1

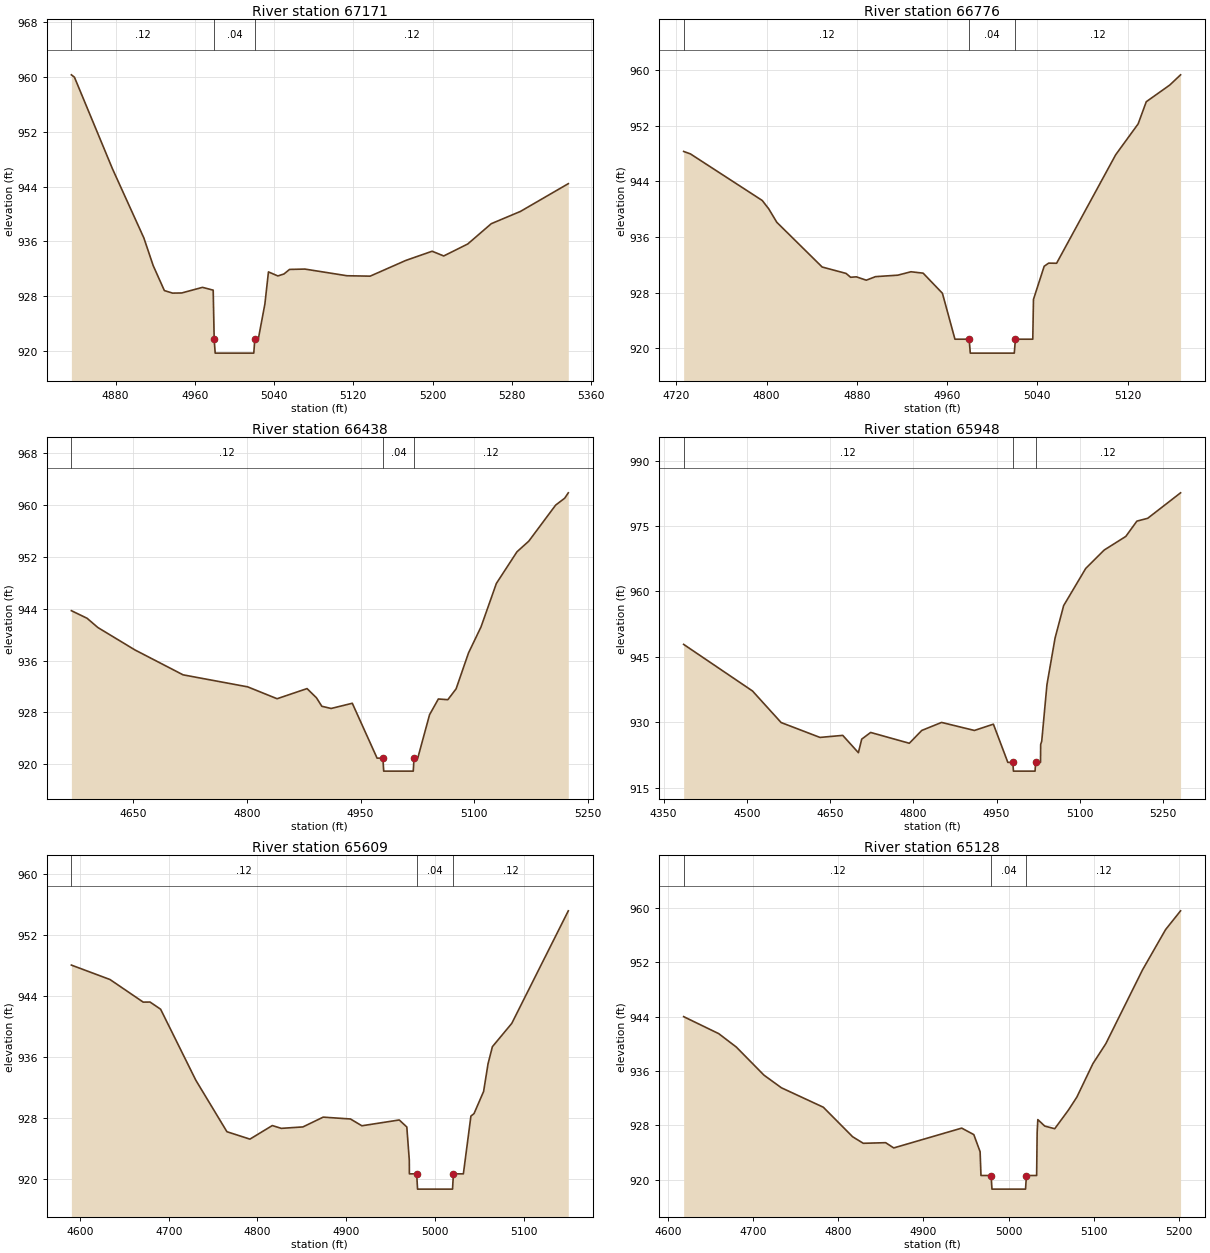
Type RM Length L Ch R = 1,67171,395,395,395
BEGIN DESCRIPTION:
North Hunting Creek 120.0
END DESCRIPTION:
XS GIS Cut Line= 4
      1459871.13       860586.01      1459788.33       860552.89
      1459566.77       860465.92      1459405.23       860399.65
#Sta/Elev= 30
  4835.3  960.27  4838.4  959.92  4876.8  946.58  4908.5  936.51  4917.9  932.49
  4929.2  928.85  4937.5  928.48  4946.7  928.50  4967.7  929.32  4978.5  928.91
  4979.5  921.74  4980.5  919.74  5019.5  919.74  5020.5  921.74  5024.0  921.75
  5030.7  926.89  5034.3  931.57  5043.8  930.98  5050.0  931.27  5055.6  931.93
  5071.1  931.98  5113.6  931.01  5137.0  930.95  5173.0  933.24  5199.6  934.58
  5211.3  933.89  5235.6  935.64  5259.3  938.59  5288.8  940.38  5337.1  944.42
#Mann=3,-1,0
  4835.3    0.12       0  4979.5    0.04       0  5020.5    0.12       0
Bank Sta=4979.5,5020.5
XS Rating Curve= 0
Exp/Cntr=0.3,0.1

Type RM Length L Ch R = 1,66776,338,338,338
BEGIN DESCRIPTION:
North Hunting Creek 119.5
END DESCRIPTION:
XS GIS Cut Line= 4
      1460034.69       860327.11      1459927.15       860248.69
      1459799.48       860121.02      1459714.37       860026.95
#Sta/Elev= 30
  4726.4  948.28  4732.4  947.93  4796.1  941.24  4801.8  940.05  4809.0  938.11
  4849.2  931.69  4870.4  930.77  4874.4  930.22  4879.5  930.28  4888.3  929.80
  4896.5  930.31  4916.2  930.52  4927.9  931.01  4938.7  930.81  4955.8  927.92
  4966.9  921.33  4979.5  921.33  4980.5  919.33  5019.5  919.33  5020.5  921.33
  5035.9  921.33  5036.5  927.04  5046.0  931.80  5050.0  932.25  5057.0  932.23
  5109.4  947.81  5129.3  952.24  5136.5  955.42  5157.3  957.81  5166.9  959.28
#Mann=3,-1,0
  4726.4    0.12       0  4979.5    0.04       0  5020.5    0.12       0
Bank Sta=4979.5,5020.5
XS Rating Curve= 0
Exp/Cntr=0.3,0.1

Type RM Length L Ch R = 1,66438,490,490,490
BEGIN DESCRIPTION:
North Hunting Creek 119.0
END DESCRIPTION:
XS GIS Cut Line= 4
      1460181.76       860260.89      1460245.94       860047.65
      1460034.73       859898.56      1459881.50       859815.73
#Sta/Elev= 30
  4568.6  943.68  4589.3  942.51  4603.6  941.08  4652.5  937.63  4715.9  933.80
  4801.1  931.95  4839.9  930.12  4879.4  931.68  4891.8  930.27  4898.9  928.96
  4911.2  928.62  4939.1  929.42  4971.8  920.97  4979.5  920.97  4980.5  918.97
  5019.5  918.97  5020.5  920.97  5025.5  921.00  5041.0  927.66  5052.6  930.08
  5065.1  929.97  5076.0  931.64  5092.4  937.18  5108.9  941.19  5129.1  947.87
  5156.3  952.75  5171.9  954.39  5207.3  959.94  5219.2  961.00  5224.0  961.83
#Mann=3,-1,0
  4568.6    0.12       0  4979.5    0.04       0  5020.5    0.12       0
Bank Sta=4979.5,5020.5
XS Rating Curve= 0
Exp/Cntr=0.3,0.1

Type RM Length L Ch R = 1,65948,339,339,339
BEGIN DESCRIPTION:
North Hunting Creek 118.5
END DESCRIPTION:
XS GIS Cut Line= 4
      1460841.06       859832.08      1460623.75       859829.83
      1460346.01       859522.97      1460133.24       859366.19
#Sta/Elev= 30
  4386.2  947.83  4510.3  937.14  4561.9  929.90  4631.9  926.49  4672.9  926.96
  4701.1  922.99  4707.1  926.10  4723.2  927.63  4792.9  925.15  4815.3  928.09
  4851.0  929.93  4910.2  928.09  4944.4  929.53  4970.4  920.77  4979.5  920.76
  4980.5  918.76  5019.5  918.76  5020.5  920.76  5029.3  920.76  5029.6  924.88
  5031.5  925.61  5040.9  938.59  5055.5  949.26  5071.0  956.72  5110.8  965.25
  5144.0  969.46  5183.0  972.59  5203.0  976.10  5222.5  976.75  5281.7  982.59
#Mann=3,-1,0
  4386.2    0.12       0  4979.5    0.04       0  5020.5    0.12       0
Bank Sta=4979.5,5020.5
XS Rating Curve= 0
Exp/Cntr=0.3,0.1

Type RM Length L Ch R = 1,65609,481,481,481
BEGIN DESCRIPTION:
North Hunting Creek 118.0
END DESCRIPTION:
XS GIS Cut Line= 4
      1460889.88       859749.45      1460788.45       859621.10
      1460655.93       859385.04      1460591.71       859277.33
#Sta/Elev= 30
  4590.4  948.02  4633.9  946.13  4671.3  943.17  4679.0  943.18  4690.9  942.24
  4730.6  932.93  4765.6  926.19  4791.5  925.22  4816.7  927.00  4826.8  926.63
  4851.2  926.82  4874.0  928.10  4904.7  927.86  4917.6  926.97  4959.7  927.73
  4968.2  926.81  4971.0  922.48  4971.1  920.67  4979.3  920.67  4980.3  918.67
  5019.7  918.67  5020.7  920.67  5031.9  920.67  5040.4  928.24  5043.9  928.56
  5054.7  931.47  5059.7  935.10  5064.6  937.33  5086.4  940.38  5150.1  955.13
#Mann=3,-1,0
  4590.4    0.12       0  4979.3    0.04       0  5020.7    0.12       0
Bank Sta=4979.3,5020.7
XS Rating Curve= 0
Exp/Cntr=0.3,0.1

Type RM Length L Ch R = 1,65128,432,432,432
BEGIN DESCRIPTION:
North Hunting Creek 117.0
END DESCRIPTION:
XS GIS Cut Line= 4
      1461330.98       859542.44      1461204.75       859431.16
      1461090.61       859175.34      1460976.43       859104.47
#Sta/Elev= 30
  4618.7  943.98  4659.9  941.48  4680.5  939.51  4712.9  935.39  4733.4  933.53
  4782.5  930.68  4816.9  926.34  4829.4  925.38  4855.6  925.47  4865.1  924.70
  4944.8  927.61  4959.0  926.66  4966.4  924.14  4967.4  920.65  4979.3  920.65
  4980.3  918.65  5019.7  918.65  5020.7  920.65  5032.7  920.65  5033.3  926.99
  5034.1  928.86  5042.2  927.91  5053.9  927.52  5069.7  930.21  5079.8  932.15
  5098.7  937.08  5113.8  940.00  5156.8  950.83  5183.9  956.76  5201.5  959.52
#Mann=3,-1,0
  4618.7    0.12       0  4979.3    0.04       0  5020.7    0.12       0
Bank Sta=4979.3,5020.7
XS Rating Curve= 0
Exp/Cntr=0.3,0.1