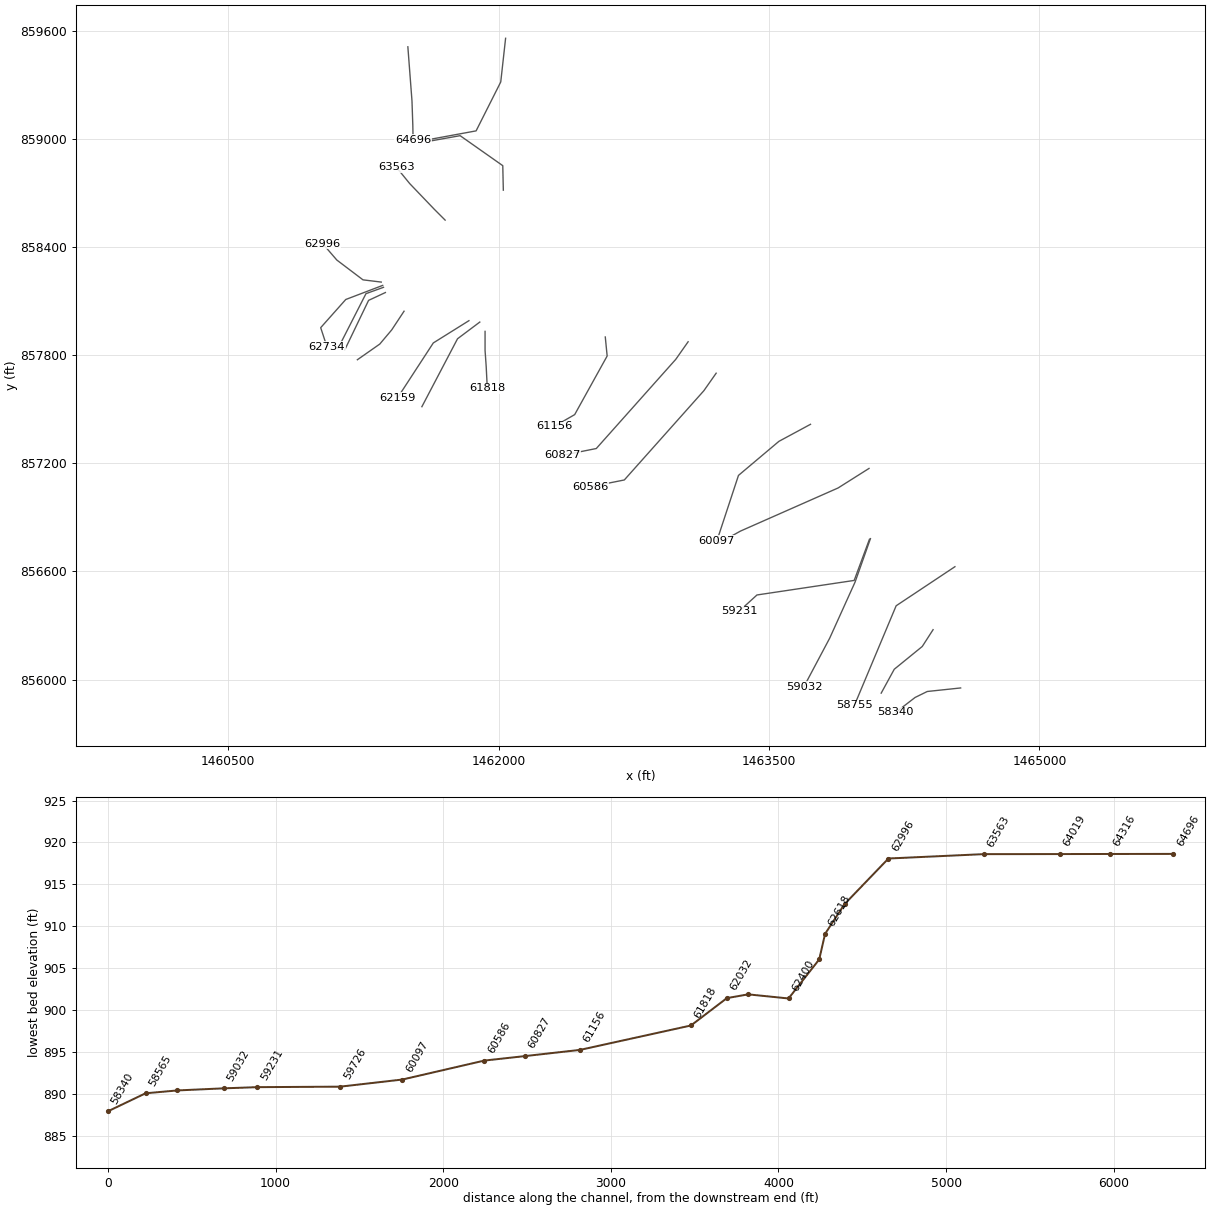
HEC-RAS study North Little Hunting Creek.prj: North Little Hunting Creek Limited Detail Study

--- North Little Hunting Creek.g01 (geometry) --- (continued)

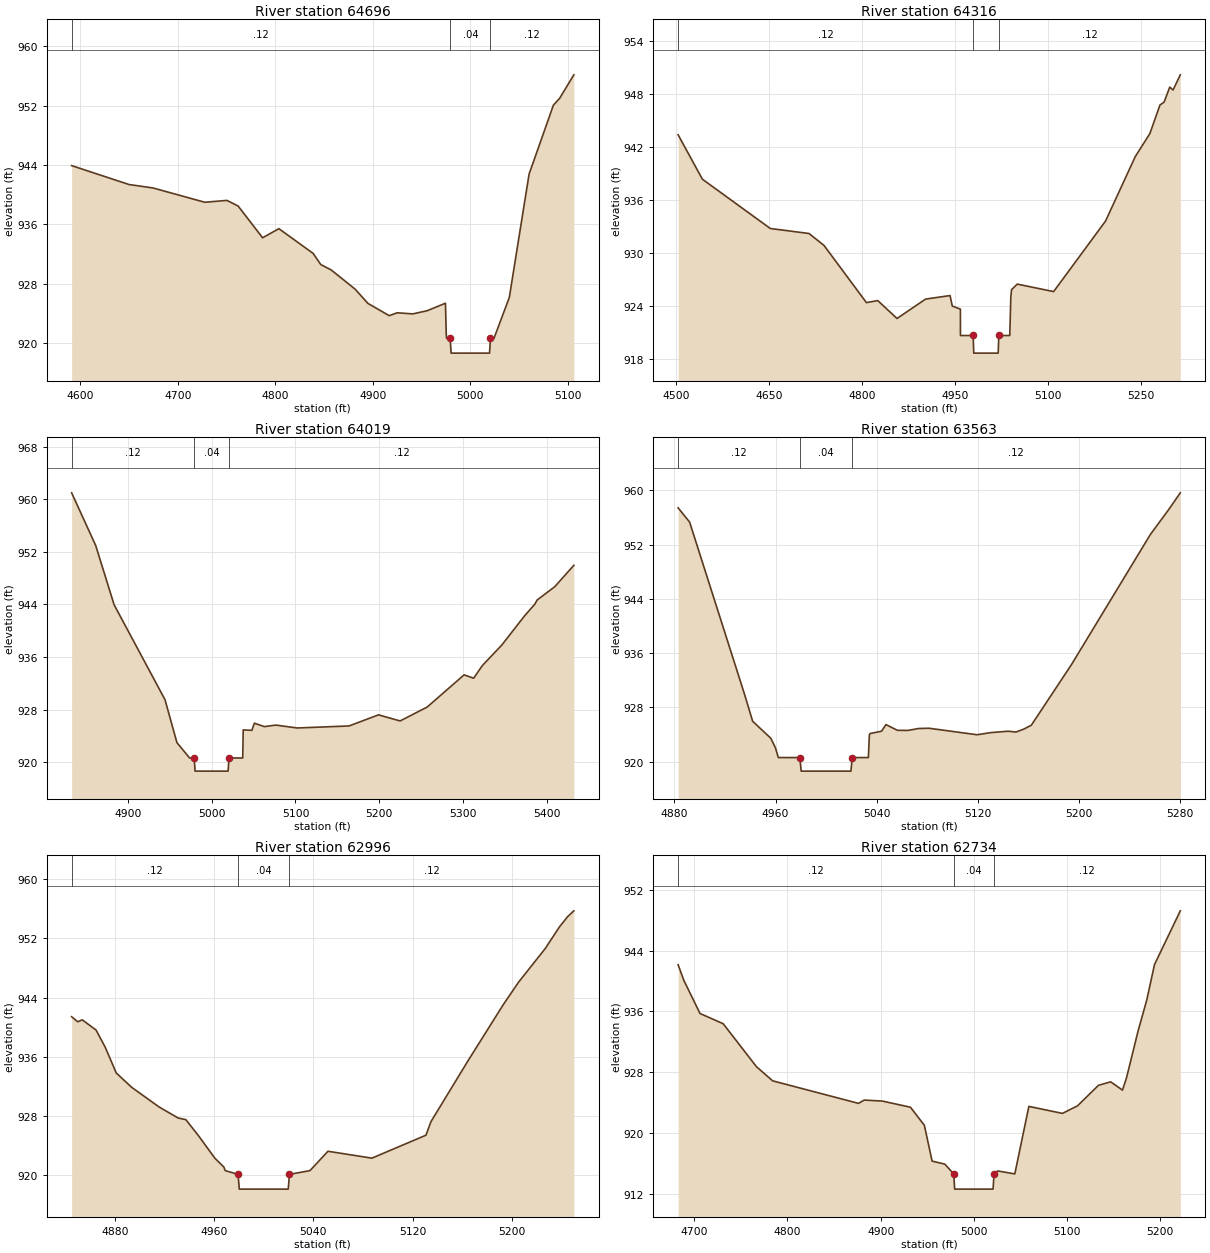
Type RM Length L Ch R = 1,64696,380,380,380
BEGIN DESCRIPTION:
North Hunting Creek 116.5
END DESCRIPTION:
XS GIS Cut Line= 4
      1461497.03       859509.61      1461519.92       859209.01
      1461524.50       859074.74      1461526.02       858995.39
#Sta/Elev= 30
  4591.0  943.92  4649.9  941.37  4674.4  940.91  4727.6  938.98  4750.3  939.23
  4761.8  938.47  4786.9  934.19  4803.6  935.42  4838.7  932.09  4846.6  930.58
  4857.2  929.86  4881.7  927.28  4895.0  925.34  4916.8  923.69  4925.0  924.08
  4941.0  923.93  4955.8  924.36  4974.5  925.37  4975.3  921.21  4975.7  920.64
  4979.3  920.64  4980.3  918.64  5019.7  918.64  5020.7  920.64  5024.3  920.64
  5040.0  926.14  5060.3  942.78  5085.2  952.06  5091.7  953.01  5106.2  956.16
#Mann=3,-1,0
  4591.0    0.12       0  4979.3    0.04       0  5020.7    0.12       0
Bank Sta=4979.3,5020.7
XS Rating Curve= 0
Exp/Cntr=0.3,0.1

Type RM Length L Ch R = 1,64316,297,297,297
BEGIN DESCRIPTION:
North Hunting Creek 116.0
END DESCRIPTION:
XS GIS Cut Line= 4
      1462039.12       859556.92      1462012.20       859314.64
      1461875.54       859043.39      1461616.69       858995.76
#Sta/Elev= 30
  4503.0  943.40  4542.2  938.36  4651.8  932.77  4714.3  932.20  4738.5  930.85
  4807.0  924.36  4825.3  924.59  4856.4  922.56  4902.5  924.76  4942.0  925.16
  4945.6  923.97  4958.7  923.62  4958.8  920.63  4979.3  920.63  4980.3  918.63
  5019.7  918.63  5020.7  920.63  5038.4  920.63  5040.1  925.03  5041.3  925.83
  5050.5  926.46  5109.2  925.61  5193.1  933.62  5240.9  940.91  5264.6  943.54
  5280.9  946.78  5287.5  947.10  5296.7  948.81  5302.0  948.48  5313.7  950.20
#Mann=3,-1,0
  4503.0    0.12       0  4979.3    0.04       0  5020.7    0.12       0
Bank Sta=4979.3,5020.7
XS Rating Curve= 0
Exp/Cntr=0.3,0.1

Type RM Length L Ch R = 1,64019,456,456,456
BEGIN DESCRIPTION:
North Hunting Creek 115.5
END DESCRIPTION:
XS GIS Cut Line= 4
      1462026.51       858714.59      1462023.45       858850.43
      1461786.95       859016.75      1461616.06       858986.24
#Sta/Elev= 30
  4833.2  961.00  4861.9  952.97  4883.8  943.96  4944.5  929.49  4958.7  922.96
  4973.8  920.62  4979.3  920.62  4980.3  918.62  5019.7  918.62  5020.7  920.62
  5037.1  920.62  5037.7  924.90  5048.0  924.83  5051.0  925.92  5062.9  925.40
  5076.7  925.63  5102.0  925.19  5163.9  925.50  5199.0  927.19  5224.7  926.26
  5257.0  928.38  5301.0  933.28  5312.4  932.77  5322.7  934.69  5346.0  937.83
  5373.1  942.27  5385.3  944.04  5388.0  944.67  5409.0  946.70  5431.8  949.96
#Mann=3,-1,0
  4833.2    0.12       0  4979.3    0.04       0  5020.7    0.12       0
Bank Sta=4979.3,5020.7
XS Rating Curve= 0
Exp/Cntr=0.3,0.1

Type RM Length L Ch R = 1,63563,567,567,567
BEGIN DESCRIPTION:
North Hunting Creek 115.0
END DESCRIPTION:
XS GIS Cut Line= 4
      1461703.71       858548.47      1461645.70       858606.48
      1461506.96       858751.43      1461434.48       858840.47
#Sta/Elev= 30
  4882.9  957.41  4892.0  955.31  4935.3  930.04  4941.9  925.96  4956.3  923.45
  4960.0  922.02  4962.2  920.61  4979.3  920.61  4980.3  918.61  5019.7  918.61
  5020.7  920.61  5033.5  920.61  5034.3  923.99  5034.9  924.15  5043.9  924.49
  5047.4  925.47  5056.5  924.62  5064.8  924.61  5073.3  924.89  5081.5  924.93
  5119.5  923.97  5130.6  924.29  5144.2  924.49  5150.3  924.37  5156.4  924.79
  5162.5  925.38  5194.3  934.32  5256.7  953.48  5271.2  957.15  5280.4  959.62
#Mann=3,-1,0
  4882.9    0.12       0  4979.3    0.04       0  5020.7    0.12       0
Bank Sta=4979.3,5020.7
XS Rating Curve= 0
Exp/Cntr=0.3,0.1

Type RM Length L Ch R = 1,62996,262,262,262
BEGIN DESCRIPTION:
North Hunting Creek 114.0
END DESCRIPTION:
XS GIS Cut Line= 4
      1461349.60       858204.77      1461248.13       858217.20
      1461103.19       858326.94      1461024.51       858418.04
#Sta/Elev= 30
  4845.3  941.40  4850.2  940.72  4853.9  940.98  4865.0  939.59  4872.4  937.25
  4881.2  933.80  4893.6  931.86  4915.8  929.19  4931.0  927.71  4937.3  927.48
  4947.5  925.30  4960.6  922.28  4967.9  921.07  4969.0  920.59  4979.3  920.09
  4980.3  918.09  5019.7  918.09  5020.7  920.09  5037.2  920.59  5051.7  923.21
  5087.1  922.28  5130.6  925.38  5134.6  927.20  5164.8  935.53  5192.9  943.04
  5205.1  946.05  5226.7  950.63  5238.3  953.59  5244.8  954.95  5249.7  955.72
#Mann=3,-1,0
  4845.3    0.12       0  4979.3    0.04       0  5020.7    0.12       0
Bank Sta=4979.3,5020.7
XS Rating Curve= 0
Exp/Cntr=0.3,0.1

Type RM Length L Ch R = 1,62734,116,116,116
BEGIN DESCRIPTION:
North Little Hunting Creek 113.5
END DESCRIPTION:
XS GIS Cut Line= 4
      1461357.39       858186.37      1461152.66       858108.23
      1461013.56       857951.94      1461047.95       857847.20
#Sta/Elev= 30
  4682.8  942.14  4689.0  940.07  4706.3  935.73  4731.2  934.38  4766.8  928.74
  4784.2  926.88  4876.2  923.92  4882.4  924.35  4901.9  924.22  4932.0  923.41
  4946.9  921.04  4955.2  916.33  4968.8  915.94  4978.4  914.65  4979.4  912.65
  5020.6  912.65  5021.6  914.65  5025.6  915.04  5043.9  914.65  5059.0  923.52
  5095.0  922.60  5111.2  923.60  5133.6  926.29  5146.7  926.75  5159.4  925.66
  5163.7  927.27  5176.2  933.47  5185.5  937.53  5193.7  942.15  5221.4  949.22
#Mann=3,-1,0
  4682.8    0.12       0  4978.4    0.04       0  5021.6    0.12       0
Bank Sta=4978.4,5021.6
XS Rating Curve= 0
Exp/Cntr=0.5,0.3

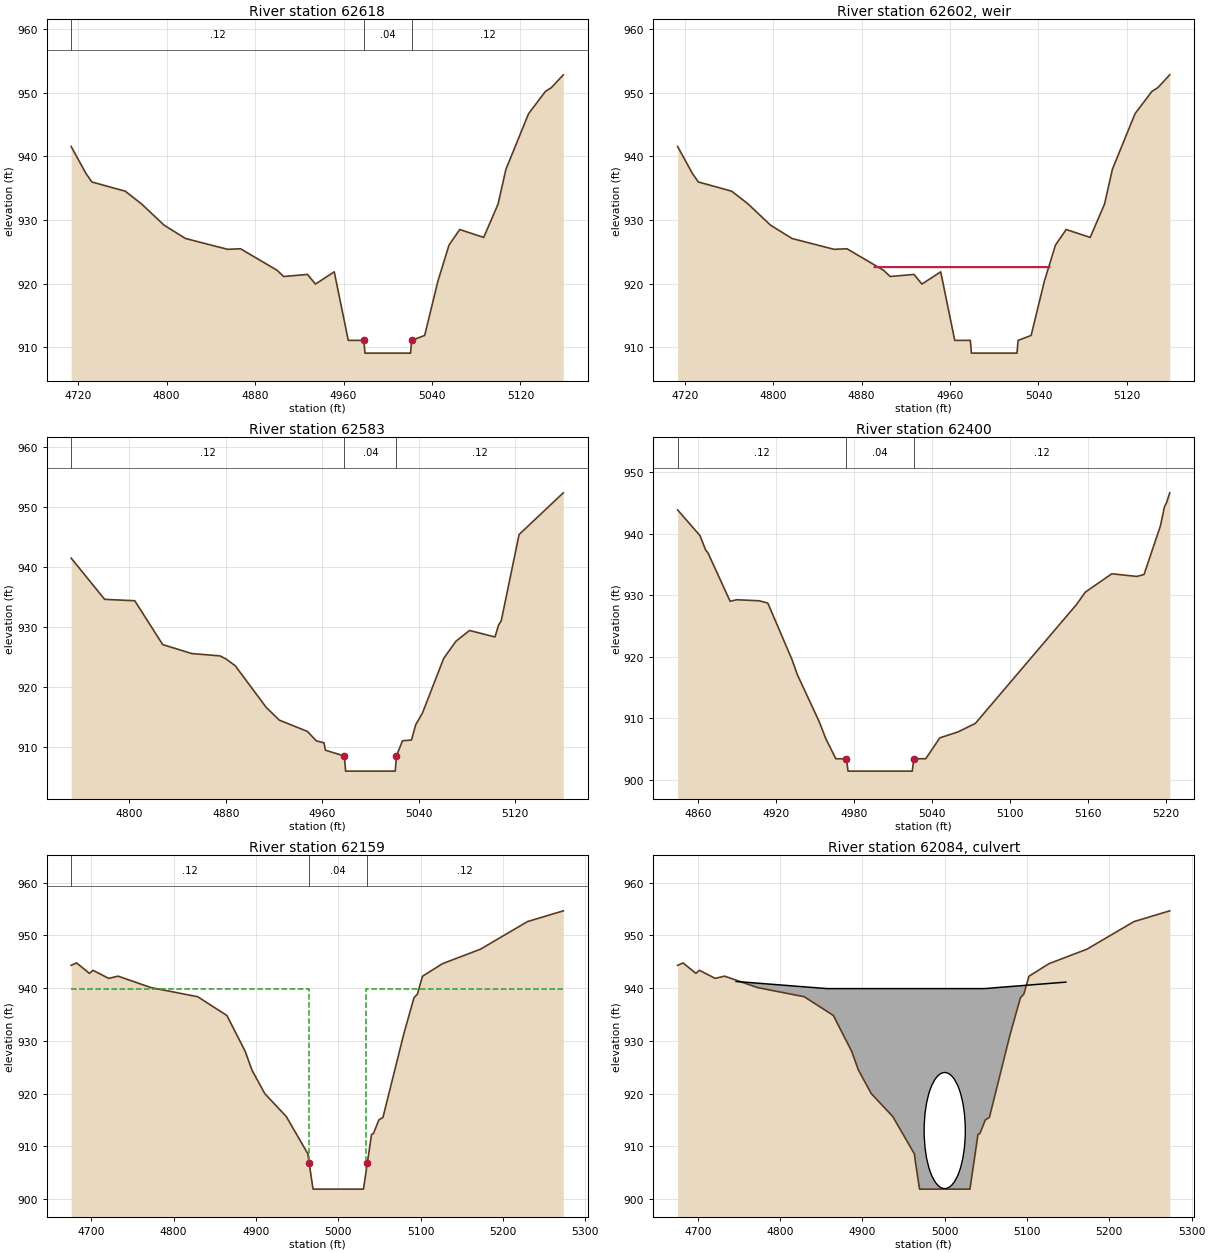
Type RM Length L Ch R = 1,62618,35,35,35
BEGIN DESCRIPTION:
Private Rd - US
END DESCRIPTION:
XS GIS Cut Line= 3
      1461361.98       858175.77      1461264.70       858140.59
      1461109.38       857836.17
#Sta/Elev= 30
  4713.6  941.56  4727.0  937.32  4732.3  935.99  4762.5  934.54  4777.3  932.54
  4797.7  929.20  4817.1  927.11  4855.1  925.41  4866.8  925.50  4899.8  922.13
  4905.9  921.14  4927.4  921.47  4934.6  919.95  4951.6  921.88  4964.3  911.11
  4978.4  911.11  4979.4  909.11  5020.6  909.11  5021.6  911.11  5033.4  911.89
  5045.4  920.43  5055.4  926.07  5065.1  928.52  5086.8  927.28  5099.8  932.52
  5106.9  937.98  5127.4  946.71  5142.7  950.22  5148.0  950.80  5158.8  952.81
#Mann=3,-1,0
  4713.6    0.12       0  4978.4    0.04       0  5021.6    0.12       0
Bank Sta=4978.4,5021.6
XS Rating Curve= 0
Exp/Cntr=0.5,0.3

Type RM Length L Ch R =5,62602,,,
BEGIN DESCRIPTION:
Private Rd - TOR
Structure ID: LDS_NLHC_07A
Approximate Survey Structure
END DESCRIPTION:
#Inline Weir SE= 3
  4891.7  922.62  4950.0  922.60  5050.0  922.60
IW Dist,WD,Coef,Skew,MaxSub,Min_El,Is_Ogee,SpillHt,DesHd
14.5,3,3,,0.95,,0,,,1,1

Type RM Length L Ch R = 1,62583,183,183,183
BEGIN DESCRIPTION:
Private Rd - DS
END DESCRIPTION:
XS GIS Cut Line= 3
      1461372.38       858146.80      1461279.19       858103.31
      1461146.65       857827.88
#Sta/Elev= 30
  4751.6  941.52  4779.4  934.65  4804.4  934.42  4827.6  927.12  4851.7  925.63
  4875.1  925.24  4880.2  924.72  4887.8  923.60  4913.5  916.67  4924.4  914.55
  4947.8  912.66  4955.0  911.11  4961.5  910.77  4962.6  909.55  4978.4  908.56
  4979.4  906.06  5020.6  906.06  5021.6  908.56  5026.6  911.11  5034.1  911.24
  5037.6  913.78  5043.2  915.73  5060.8  924.82  5071.0  927.68  5082.3  929.47
  5103.4  928.39  5106.4  930.39  5108.6  931.09  5123.4  945.44  5160.1  952.38
#Mann=3,-1,0
  4751.6    0.12       0  4978.4    0.04       0  5021.6    0.12       0
Bank Sta=4978.4,5021.6
XS Rating Curve= 0
Exp/Cntr=0.5,0.3

Type RM Length L Ch R = 1,62400,241,241,241
BEGIN DESCRIPTION:
North Hunting Creek 113.0
END DESCRIPTION:
XS GIS Cut Line= 4
      1461475.91       858043.27      1461407.57       857939.73
      1461341.31       857861.05      1461217.05       857774.07
#Sta/Elev= 30
  4844.2  943.87  4861.4  939.70  4865.8  937.34  4867.6  936.87  4884.6  929.02
  4889.8  929.27  4907.0  929.10  4913.6  928.73  4932.2  919.54  4936.3  917.10
  4953.3  909.37  4958.1  906.74  4965.9  903.42  4974.1  903.41  4975.3  901.41
  5024.7  901.41  5025.9  903.41  5035.1  903.43  5045.9  906.82  5060.0  907.79
  5073.3  909.18  5151.0  928.48  5157.8  930.50  5178.2  933.49  5197.5  933.06
  5203.0  933.37  5215.6  941.26  5218.7  944.37  5220.2  944.98  5222.8  946.65
#Mann=3,-1,0
  4844.2    0.12       0  4974.1    0.04       0  5025.9    0.12       0
Bank Sta=4974.1,5025.9
XS Rating Curve= 0
Exp/Cntr=0.5,0.3

Type RM Length L Ch R = 1,62159,127,127,127
BEGIN DESCRIPTION:
Buck Shoal Rd - US
END DESCRIPTION:
XS GIS Cut Line= 3
      1461835.75       857990.75      1461638.14       857867.25
      1461438.97       857561.54
#Sta/Elev= 30
  4675.5  944.31  4682.1  944.77  4697.7  942.79  4702.0  943.37  4721.1  941.84
  4732.5  942.26  4772.6  940.09  4829.3  938.36  4864.7  934.81  4886.9  928.03
  4895.2  924.44  4910.8  919.99  4936.9  915.65  4963.1  908.59  4964.6  906.90
  4969.4  901.90  5030.6  901.90  5035.4  906.90  5040.4  912.25  5042.8  912.45
  5049.3  915.01  5054.3  915.49  5079.5  931.24  5092.0  938.17  5096.2  938.87
  5102.3  942.24  5126.7  944.63  5172.9  947.38  5229.9  952.60  5273.4  954.64
#Mann=3,-1,0
  4675.5    0.12       0  4964.6    0.04       0  5035.4    0.12       0
#XS Ineff=2,0
    0.00 4965.00  939.90 5034.00    0.00  939.90
Permanent Ineff=
       F       F
Bank Sta=4964.6,5035.4
XS Rating Curve= 0
Exp/Cntr=0.5,0.3

Type RM Length L Ch R =2,62084,,,
BEGIN DESCRIPTION:
Buck Shoal Rd - TOR
Structure ID: LDS_NLHC_07
Approximate Survey Structure
END DESCRIPTION:
Bridge Culvert--1,0,-1,-1,0
Deck Dist Width WeirC Skew NumUp NumDn MinLoCord MaxHiCord MaxSubmerge Is_Ogee
30,90,3,,4,4,,,,0,1,1,,,
  4746.6  4856.9  5048.1  5147.1
  941.25  939.90  939.90  941.13
  881.90  881.90  881.90  881.90
  4746.6  4856.9  5048.1  5147.1
  941.25  939.90  939.90  941.13
  881.45  881.45  881.45  881.45
Culvert=4,22,50,90,0.013,0.5,1,29,1,902,5000,901.55,5000,Culvert #1,0,30
Culvert Bottom n=0.012
Culvert Bottom Depth=0
Culvert Depth Blocked=0
BC Design=,,0,,0,,,,,,

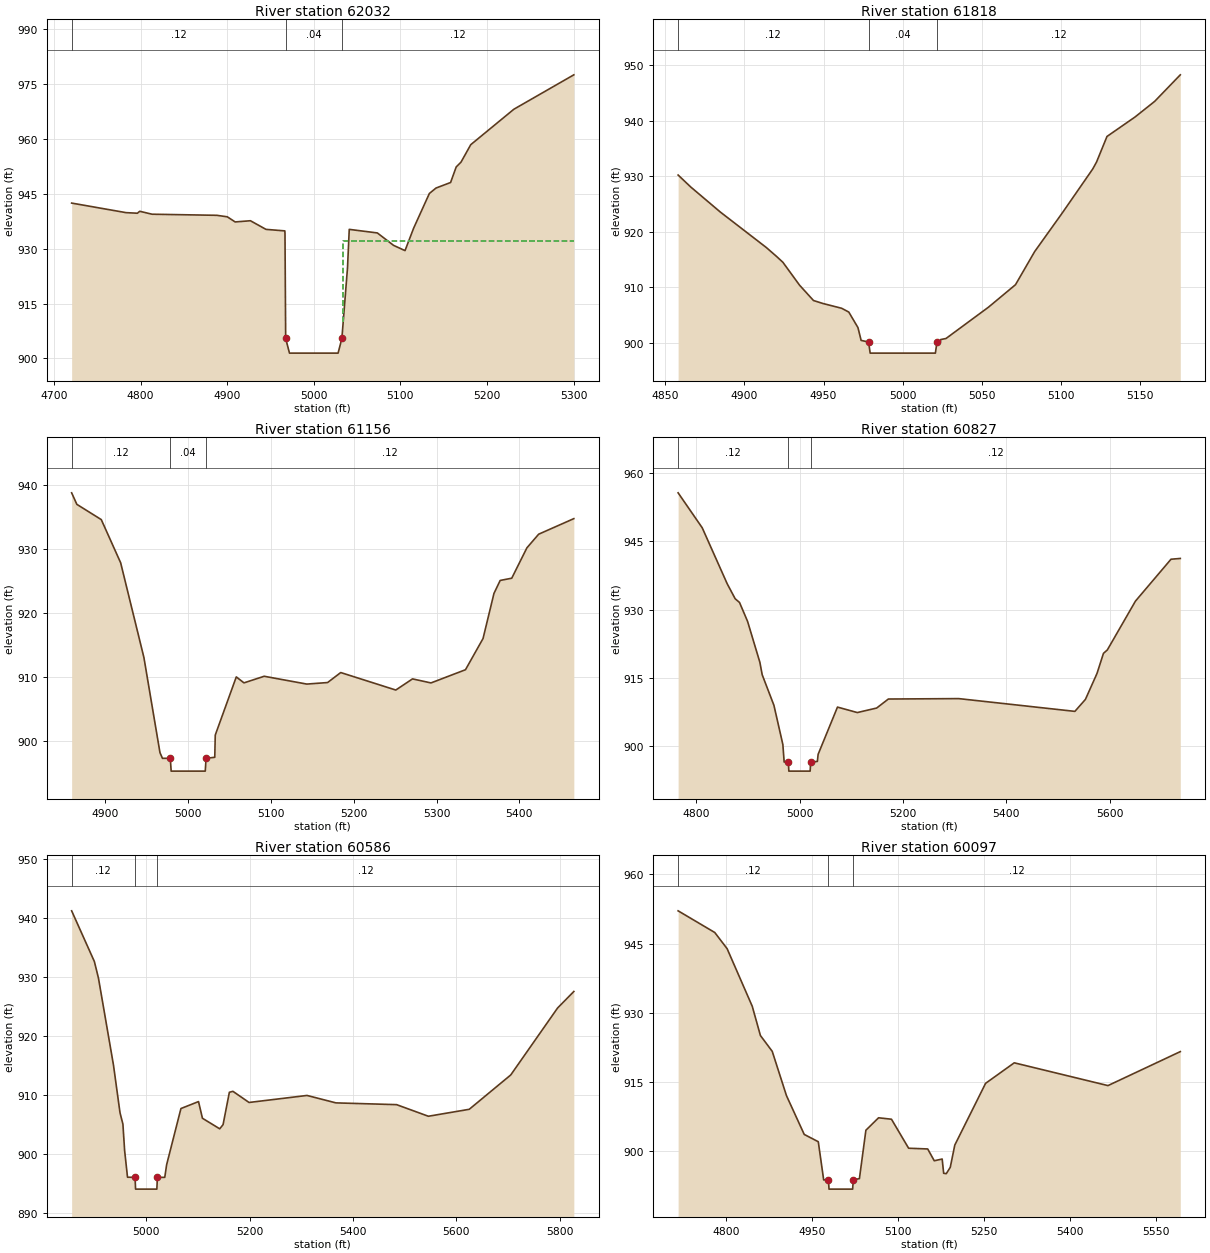
Type RM Length L Ch R = 1,62032,214,214,214
BEGIN DESCRIPTION:
Buck Shoal Rd - DS
END DESCRIPTION:
XS GIS Cut Line= 3
      1461895.99       857983.05      1461772.46       857890.40
      1461574.85       857513.70
#Sta/Elev= 30
  4720.5  942.42  4783.3  939.81  4796.4  939.65  4799.1  940.18  4813.4  939.38
  4888.1  939.08  4900.2  938.67  4909.3  937.27  4926.9  937.60  4944.9  935.24
  4966.6  934.83  4966.8  934.17  4967.6  905.45  4972.0  901.45  5028.1  901.45
  5032.5  905.45  5039.0  924.78  5041.0  935.24  5073.4  934.27  5092.2  930.87
  5105.4  929.44  5115.4  935.60  5133.5  945.04  5141.2  946.53  5158.0  948.04
  5164.5  952.29  5170.0  953.59  5181.3  958.37  5231.1  968.05  5300.3  977.44
#Mann=3,-1,0
  4720.5    0.12       0  4967.6    0.04       0  5032.5    0.12       0
#XS Ineff=2,0
    0.00 4965.00  932.00 5034.00    0.00  932.00
Permanent Ineff=
       F       F
Bank Sta=4967.6,5032.5
XS Rating Curve= 0
Exp/Cntr=0.5,0.3

Type RM Length L Ch R = 1,61818,662,662,662
BEGIN DESCRIPTION:
North Hunting Creek 112.0
END DESCRIPTION:
XS GIS Cut Line= 4
      1461925.23       857931.44      1461925.23       857825.85
      1461931.45       857736.81      1461937.66       857614.62
#Sta/Elev= 30
  4858.1  930.24  4866.1  928.08  4884.8  923.57  4913.7  917.22  4920.4  915.56
  4924.3  914.53  4934.8  910.42  4943.6  907.66  4949.6  907.12  4961.4  906.26
  4965.9  905.58  4971.7  902.78  4973.7  900.48  4978.4  900.19  4979.4  898.19
  5020.6  898.19  5021.6  900.19  5023.8  900.19  5023.9  900.63  5027.3  900.82
  5054.1  906.45  5071.2  910.50  5083.3  916.46  5100.5  923.31  5120.0  931.33
  5122.4  932.58  5129.0  937.18  5146.8  940.70  5159.1  943.49  5175.3  948.27
#Mann=3,-1,0
  4858.1    0.12       0  4978.4    0.04       0  5021.6    0.12       0
Bank Sta=4978.4,5021.6
XS Rating Curve= 0
Exp/Cntr=0.3,0.1

Type RM Length L Ch R = 1,61156,329,329,329
BEGIN DESCRIPTION:
North Hunting Creek 111.0
END DESCRIPTION:
XS GIS Cut Line= 4
      1462591.99       857900.35      1462602.33       857794.79
      1462422.19       857469.70      1462310.34       857405.49
#Sta/Elev= 30
  4859.2  938.73  4865.5  936.93  4895.0  934.55  4918.4  927.81  4946.5  913.02
  4965.9  898.17  4968.9  897.28  4978.4  897.28  4979.4  895.28  5020.6  895.28
  5021.6  897.28  5032.1  897.44  5032.7  900.91  5058.1  909.99  5067.4  909.06
  5091.8  910.09  5143.3  908.87  5168.4  909.11  5184.3  910.67  5250.8  907.94
  5271.0  909.68  5293.3  909.05  5335.0  911.11  5356.2  915.98  5369.4  923.02
  5376.9  925.05  5390.9  925.40  5409.2  930.14  5423.4  932.27  5465.9  934.70
#Mann=3,-1,0
  4859.2    0.12       0  4978.4    0.04       0  5021.6    0.12       0
Bank Sta=4978.4,5021.6
XS Rating Curve= 0
Exp/Cntr=0.3,0.1

Type RM Length L Ch R = 1,60827,241,241,241
BEGIN DESCRIPTION:
North Little Hunting Creek 110.5
END DESCRIPTION:
XS GIS Cut Line= 4
      1463051.45       857873.87      1462983.13       857776.57
      1462542.08       857281.68      1462355.76       857244.42
#Sta/Elev= 30
  4765.1  955.60  4811.8  947.92  4860.0  935.67  4875.5  932.36  4883.9  931.55
  4899.5  927.40  4923.3  918.42  4927.8  915.69  4950.5  908.98  4967.8  900.38
  4970.3  896.54  4978.4  896.54  4979.4  894.54  5020.6  894.54  5021.6  896.54
  5034.6  896.67  5036.0  898.21  5073.5  908.59  5111.9  907.39  5149.3  908.38
  5172.0  910.36  5308.1  910.45  5532.9  907.65  5553.3  910.28  5575.7  915.97
  5588.2  920.38  5595.7  921.13  5650.1  931.84  5718.9  941.03  5736.9  941.20
#Mann=3,-1,0
  4765.1    0.12       0  4978.4    0.04       0  5021.6    0.12       0
Bank Sta=4978.4,5021.6
XS Rating Curve= 0
Exp/Cntr=0.3,0.1

Type RM Length L Ch R = 1,60586,489,489,489
BEGIN DESCRIPTION:
North Hunting Creek 110.0
END DESCRIPTION:
XS GIS Cut Line= 4
      1463206.94       857699.50      1463138.63       857602.22
      1462697.58       857107.33      1462511.24       857070.06
#Sta/Elev= 30
  4855.7  941.25  4899.7  932.64  4907.6  929.82  4936.6  915.09  4949.3  906.97
  4954.9  905.05  4958.2  900.57  4963.8  896.03  4978.4  896.01  4979.4  894.01
  5020.6  894.01  5021.6  896.01  5035.9  896.01  5039.5  898.15  5067.2  907.69
  5101.2  908.87  5108.8  906.04  5142.2  904.25  5148.7  904.95  5160.9  910.45
  5167.8  910.61  5199.0  908.72  5311.2  909.91  5367.1  908.65  5484.5  908.35
  5546.0  906.38  5625.1  907.56  5705.4  913.39  5796.1  924.76  5827.5  927.56
#Mann=3,-1,0
  4855.7    0.12       0  4978.4    0.04       0  5021.6    0.12       0
#XS Ineff=2,0
       0                 5101.20    0.00  908.87
Permanent Ineff=
       F       F
Bank Sta=4978.4,5021.6
XS Rating Curve= 0
Exp/Cntr=0.3,0.1

Type RM Length L Ch R = 1,60097,371,371,371
BEGIN DESCRIPTION:
North Hunting Creek 109.0
END DESCRIPTION:
XS GIS Cut Line= 4
      1463730.15       857416.01      1463555.03       857321.56
      1463330.69       857132.64      1463210.64       856768.58
#Sta/Elev= 30
  4716.3  952.10  4780.2  947.40  4801.8  943.88  4845.6  931.39  4859.8  925.06
  4880.4  921.63  4905.2  912.03  4936.2  903.61  4960.7  902.03  4970.1  893.75
  4978.4  893.75  4979.4  891.75  5020.6  891.75  5021.6  893.75  5032.4  894.03
  5043.7  904.52  5065.8  907.22  5088.3  906.91  5118.2  900.62  5151.5  900.46
  5162.9  897.90  5176.7  898.28  5179.3  895.18  5183.9  895.11  5190.8  896.47
  5198.7  901.30  5252.4  914.69  5302.4  919.14  5465.8  914.20  5591.9  921.57
#Mann=3,-1,0
  4716.3    0.12       0  4978.4    0.04       0  5021.6    0.12       0
#XS Ineff=2,0
       0                 5065.80    0.00  907.22
Permanent Ineff=
       F       F
Bank Sta=4978.4,5021.6
XS Rating Curve= 0
Exp/Cntr=0.3,0.1

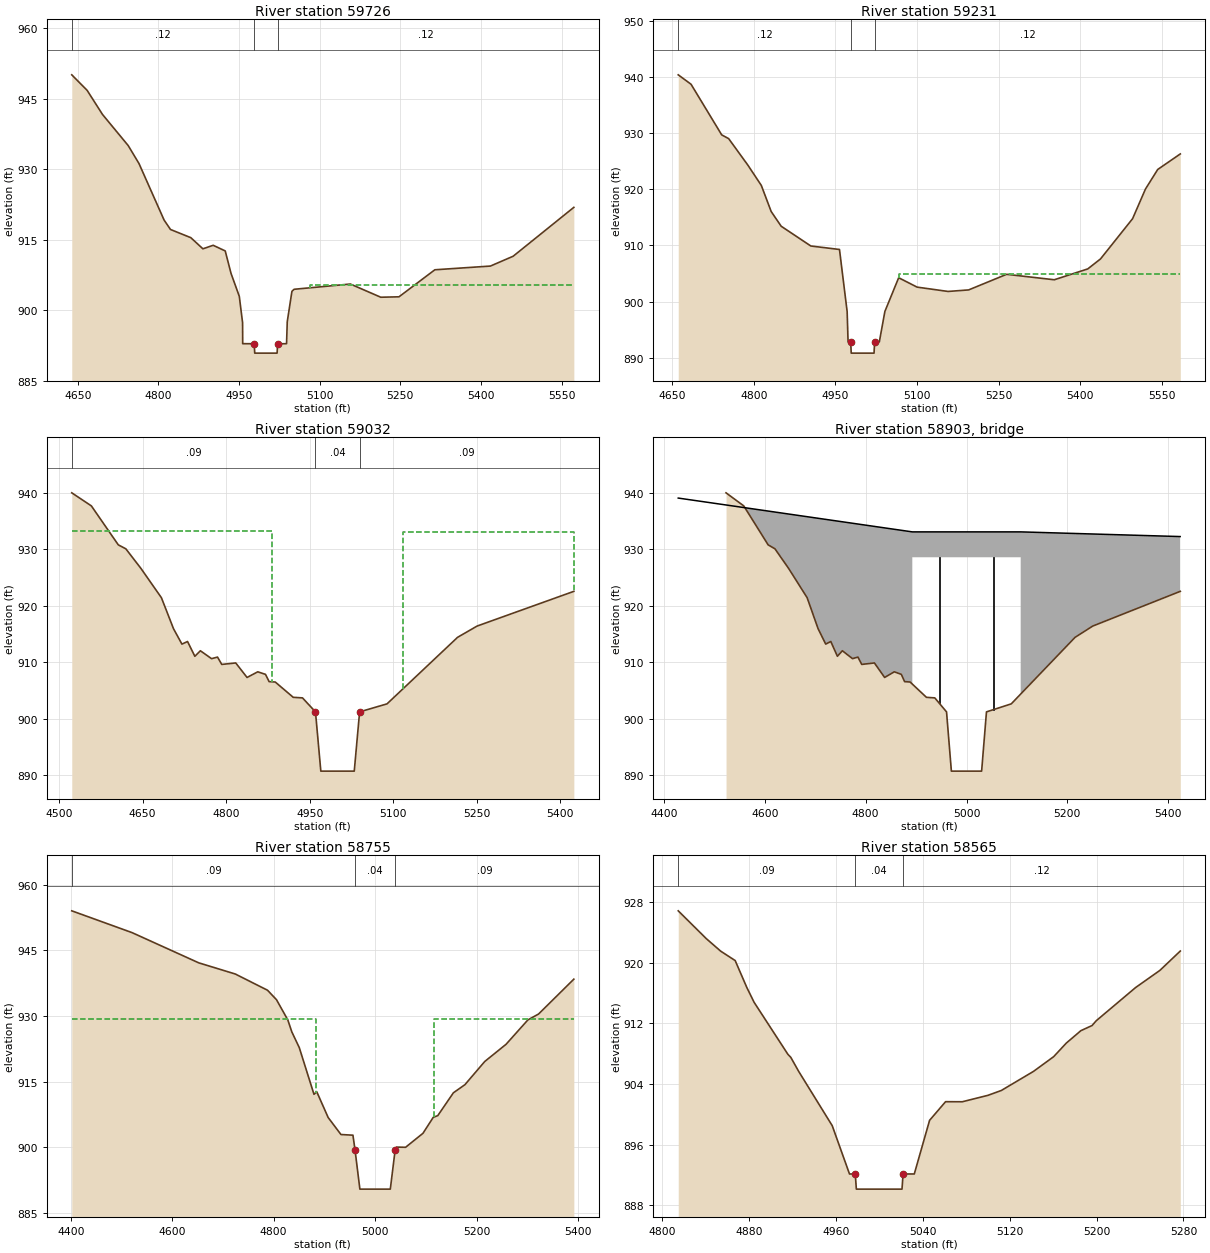
Type RM Length L Ch R = 1,59726,495,495,495
BEGIN DESCRIPTION:
North Hunting Creek 108.5
END DESCRIPTION:
XS GIS Cut Line= 4
      1464054.73       857171.28      1463883.24       857062.97
      1463341.82       856823.84      1463219.97       856756.15
#Sta/Elev= 30
  4638.8  950.10  4667.3  946.81  4696.0  941.67  4743.8  935.05  4763.9  931.22
  4810.6  919.20  4822.5  917.20  4860.3  915.46  4882.8  913.09  4901.9  913.84
  4924.3  912.64  4935.1  907.86  4950.5  902.98  4956.6  897.36  4956.8  892.91
  4978.2  892.90  4979.2  890.90  5020.8  890.90  5021.8  892.90  5038.4  892.90
  5039.7  897.57  5048.4  904.04  5052.4  904.48  5157.1  905.60  5213.7  902.79
  5247.6  902.88  5314.3  908.63  5417.7  909.42  5460.0  911.51  5572.9  921.91
#Mann=3,-1,0
  4638.8    0.12       0  4978.2    0.04       0  5021.8    0.12       0
#XS Ineff=2,0
       0                 5082.60    0.00  905.43
Permanent Ineff=
       F       F
Bank Sta=4978.2,5021.8
XS Rating Curve= 0
Exp/Cntr=0.3,0.1

Type RM Length L Ch R = 1,59231,199,199,199
BEGIN DESCRIPTION:
North Hunting Creek 108.0
END DESCRIPTION:
XS GIS Cut Line= 4
      1464057.05       856778.42      1463972.42       856550.13
      1463433.21       856469.45      1463333.29       856378.48
#Sta/Elev= 30
  4660.7  940.38  4684.3  938.70  4740.7  929.69  4753.5  929.02  4788.8  924.31
  4813.6  920.69  4831.7  916.05  4850.1  913.43  4904.7  909.91  4957.4  909.29
  4971.5  898.22  4973.2  892.84  4978.0  892.84  4979.0  890.84  5021.0  890.84
  5022.0  892.84  5030.7  892.84  5040.9  898.25  5066.3  904.26  5100.2  902.59
  5157.1  901.82  5195.0  902.09  5264.9  904.87  5352.6  903.90  5414.2  905.83
  5437.7  907.61  5496.7  914.77  5520.4  920.05  5542.9  923.53  5584.5  926.30
#Mann=3,-1,0
  4660.7    0.12       0  4978.0    0.04       0  5022.0    0.12       0
#XS Ineff=2,0
       0                 5066.30    0.00  904.86
Permanent Ineff=
       F       F
Bank Sta=4978,5022
XS Rating Curve= 0
Exp/Cntr=0.5,0.3

Type RM Length L Ch R = 1,59032,277,277,277
BEGIN DESCRIPTION:
Hwy 77 - US
END DESCRIPTION:
XS GIS Cut Line= 4
      1464062.58       856781.88      1463977.39       856541.11
      1463836.61       856229.92      1463693.97       855961.30
#Sta/Elev= 30
  4523.0  940.02  4558.2  937.70  4606.5  930.80  4620.0  930.10  4647.1  926.63
  4683.9  921.43  4705.6  915.94  4720.7  913.21  4730.8  913.67  4743.9  911.05
  4753.8  912.03  4773.9  910.63  4784.6  910.91  4792.2  909.61  4817.3  909.87
  4837.6  907.30  4856.8  908.30  4870.7  907.85  4877.2  906.56  4888.2  906.49
  4920.5  903.78  4937.1  903.68  4960.4  901.20  4970.0  890.70  5030.0  890.70
  5039.6  901.20  5088.8  902.62  5215.4  914.41  5250.5  916.41  5424.1  922.56
#Mann=3,-1,0
  4523.0    0.09       0  4960.4    0.04       0  5039.6    0.09       0
#XS Ineff=2,0
    0.00 4883.00  933.26 5117.00    0.00  933.11
Permanent Ineff=
       F       F
Bank Sta=4960.4,5039.6
XS Rating Curve= 0
Exp/Cntr=0.5,0.3

Type RM Length L Ch R =3,58903,,,
BEGIN DESCRIPTION:
Hwy 77 - TOR
Structure ID: LDS_NLHC_05
Approximate Survey Structure
END DESCRIPTION:
Bridge Culvert--1,0,-1,-1,0
Deck Dist Width WeirC Skew NumUp NumDn MinLoCord MaxHiCord MaxSubmerge Is_Ogee
106.5,90,3,,6,6,,,0.95,0,1.0,1,,,
  4428.2  4892.5  4892.5  5107.5  5107.5  5423.8
  939.09  933.10  933.10  933.10  933.10  932.27
  870.70  870.70  928.60  928.60  870.70  870.70
  4428.2  4892.5  4892.5  5107.5  5107.5  5423.8
  939.09  933.10  933.10  933.10  933.10  932.27
  870.70  870.70  928.60  928.60  870.70  870.70
Pier Skew, UpSta & Num, DnSta & Num=,4946.3,2,4946.3,2,0,0,0,0,0
     2.7     2.7
  897.48  928.60
     2.7     2.7
  903.02  928.60
Pier Skew, UpSta & Num, DnSta & Num=,5053.8,2,5053.8,2,0,0,0,0,0
     2.7     2.7
  901.22  928.60
     2.7     2.7
  899.92  928.60
Abutment Skew #Up #Dn=,2,2
  4892.5  4927.5
  928.60  903.69
  4892.5  4927.5
  928.60  903.96
Abutment Skew #Up #Dn=,2,2
  5072.5  5107.5
  901.71  928.60
  5072.5  5107.5
  901.26  928.60
BR Coef=1,1,0,1.25,0,,,0.8,0,2,0,
WSPro=,,,, 1 ,,,, 0 ,,,, 0 ,,,,-1 ,-1 ,-1 , 0 , 0 , 0 , 0 , 0
BC Design=,,0,,0,,,,,,

Type RM Length L Ch R = 1,58755,190,190,190
BEGIN DESCRIPTION:
Hwy 77 - DS
END DESCRIPTION:
XS GIS Cut Line= 3
      1464531.18       856626.28      1464205.22       856409.59
      1463973.68       855857.60
#Sta/Elev= 30
  4401.9  954.06  4520.7  949.08  4652.3  942.17  4724.3  939.62  4787.9  935.91
  4805.7  933.73  4827.9  929.12  4835.8  926.39  4850.5  922.80  4879.5  912.12
  4885.0  912.70  4907.5  906.81  4932.7  902.93  4956.3  902.78  4960.4  899.45
  4970.0  890.45  5030.0  890.45  5039.6  899.45  5042.2  900.06  5060.1  900.01
  5094.4  903.21  5114.7  906.86  5123.6  907.25  5154.4  912.47  5177.1  914.32
  5216.2  919.62  5258.3  923.56  5301.3  929.13  5322.3  930.47  5391.9  938.44
#Mann=3,-1,0
  4401.9    0.09       0  4960.4    0.04       0  5039.6    0.09       0
#XS Ineff=2,0
    0.00 4883.00  929.40 5117.00    0.00  929.40
Permanent Ineff=
       F       F
Bank Sta=4960.4,5039.6
XS Rating Curve= 0
Exp/Cntr=0.5,0.3

Type RM Length L Ch R = 1,58565,225,225,225
BEGIN DESCRIPTION:
North Hunting Creek 107.0
END DESCRIPTION:
XS GIS Cut Line= 4
      1464409.99       856276.98      1464349.96       856183.82
      1464194.66       856057.51      1464122.21       855925.03
#Sta/Elev= 30
  4815.1  926.87  4840.9  923.20  4854.2  921.54  4867.5  920.30  4878.2  916.75
  4884.9  914.79  4916.0  907.92  4918.7  907.51  4925.9  905.67  4956.8  898.49
  4972.7  892.11  4978.0  892.11  4979.0  890.11  5021.0  890.11  5022.0  892.11
  5032.3  892.11  5046.4  899.20  5061.1  901.66  5076.5  901.65  5100.1  902.50
  5112.4  903.14  5142.1  905.67  5160.6  907.61  5172.2  909.40  5185.6  911.04
  5195.9  911.72  5199.8  912.36  5236.0  916.74  5258.3  919.00  5277.1  921.56
#Mann=3,-1,0
  4815.1    0.09       0  4978.0    0.04       0  5022.0    0.12       0
Bank Sta=4978,5022
XS Rating Curve= 0
Exp/Cntr=0.3,0.1

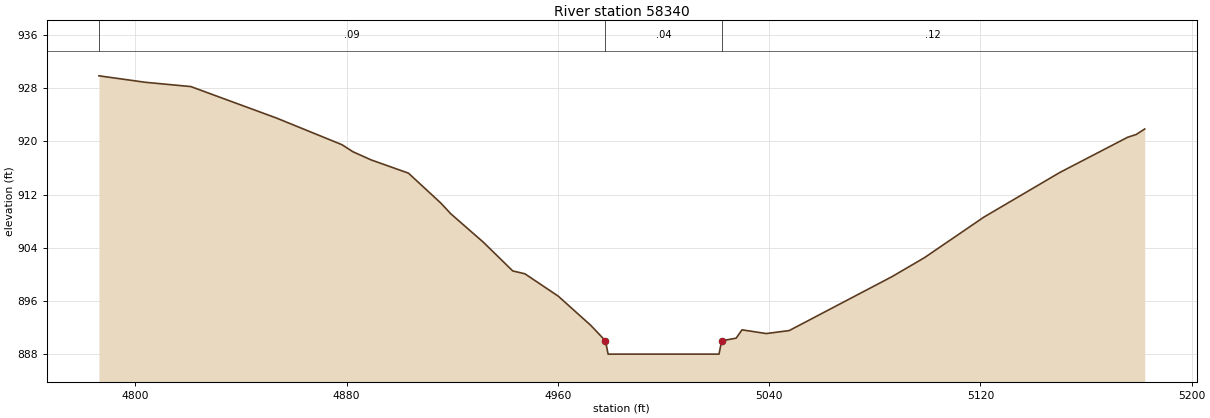
Type RM Length L Ch R = 1,58340,330,330,330
BEGIN DESCRIPTION:
North Little Hunting Creek 106.5
END DESCRIPTION:
XS GIS Cut Line= 4
      1464562.88       855953.81      1464377.71       855934.19
      1464310.25       855901.08      1464203.58       855818.92
#Sta/Elev= 30
  4786.2  929.88  4803.7  928.91  4821.0  928.26  4853.5  923.51  4878.2  919.51
  4882.4  918.44  4889.3  917.21  4903.4  915.22  4915.7  910.70  4919.4  909.11
  4931.7  904.84  4942.9  900.49  4947.5  900.06  4960.1  896.70  4972.4  892.31
  4978.0  889.96  4979.0  887.96  5021.0  887.96  5022.0  889.96  5027.5  890.37
  5029.7  891.62  5038.9  891.06  5047.6  891.51  5086.5  899.63  5098.8  902.49
  5121.3  908.60  5150.0  915.31  5175.7  920.62  5179.0  921.05  5182.2  921.87
#Mann=3,-1,0
  4786.2    0.09       0  4978.0    0.04       0  5022.0    0.12       0
Bank Sta=4978,5022
XS Rating Curve= 0
Exp/Cntr=0.3,0.1