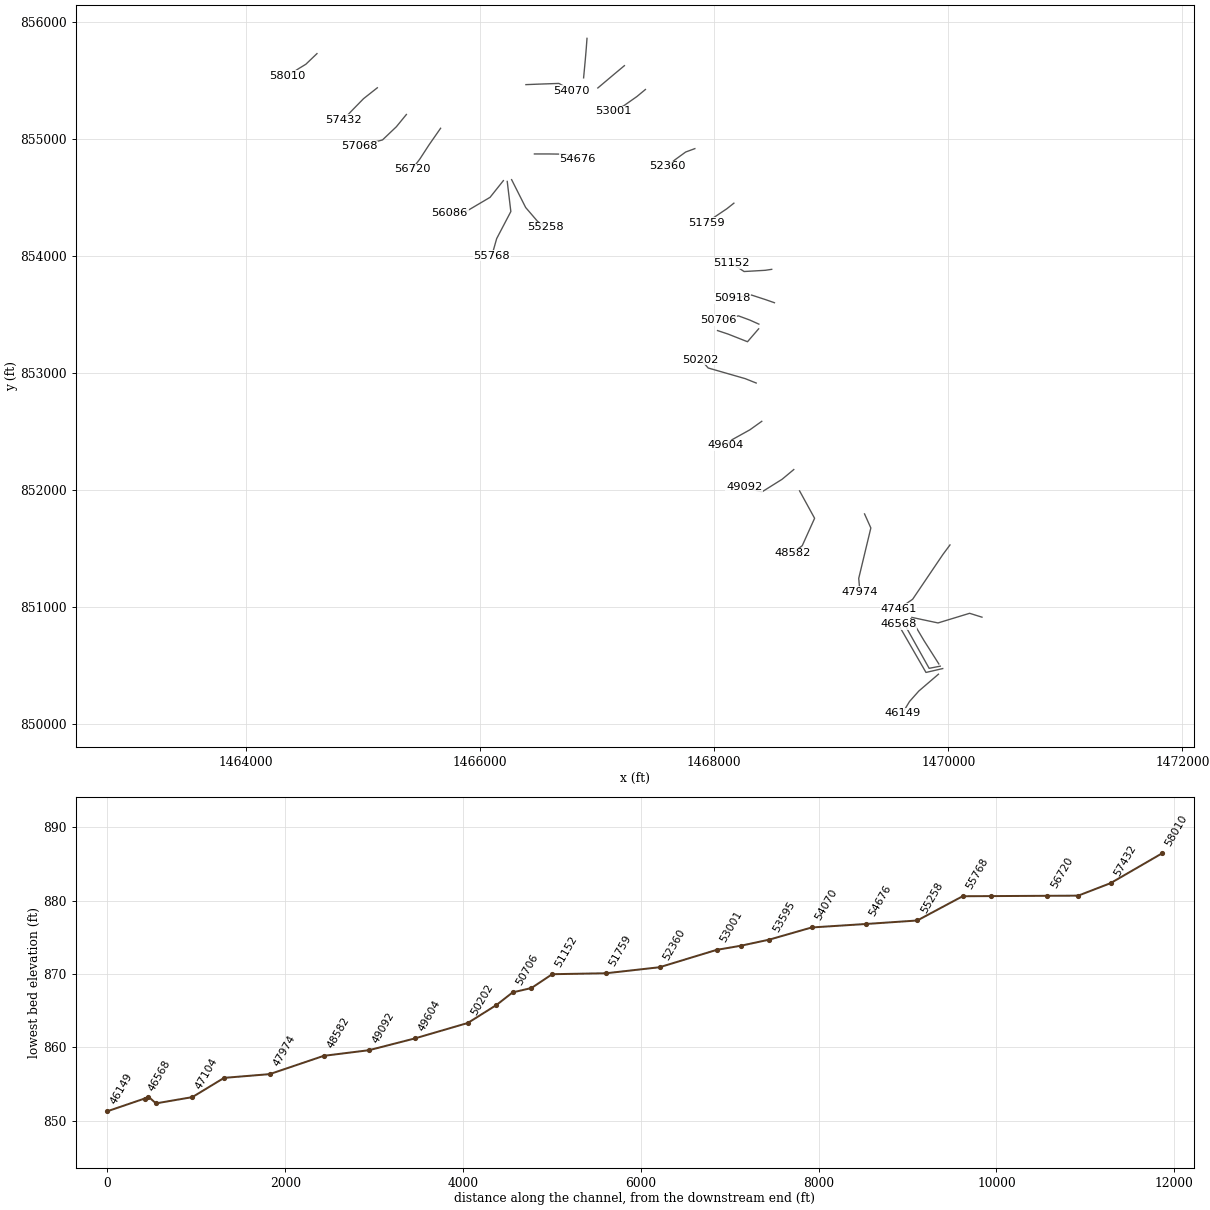
HEC-RAS study North Little Hunting Creek.prj: North Little Hunting Creek Limited Detail Study

--- North Little Hunting Creek.g01 (geometry) --- (continued)

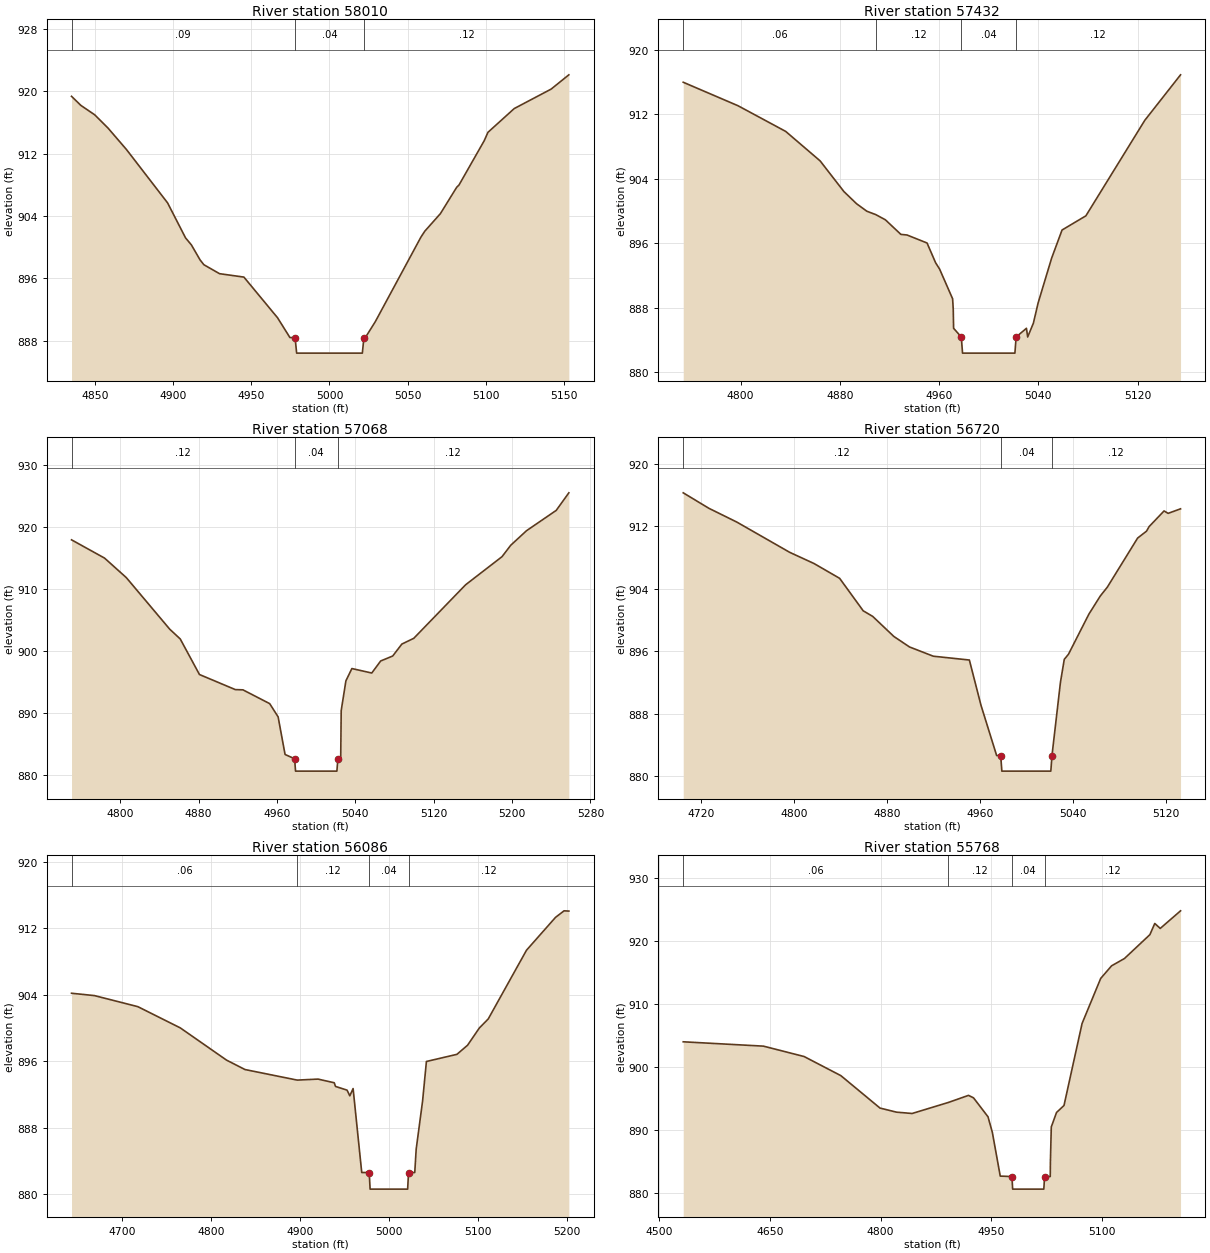
Type RM Length L Ch R = 1,58010,578,578,578
BEGIN DESCRIPTION:
North Hunting Creek 106.0
END DESCRIPTION:
XS GIS Cut Line= 4
      1464606.70       855728.26      1464511.47       855637.17
      1464453.49       855601.97      1464354.12       855537.79
#Sta/Elev= 30
  4835.1  919.38  4841.1  918.21  4849.9  917.01  4858.4  915.31  4870.3  912.53
  4896.5  905.70  4908.0  901.20  4911.7  900.31  4917.3  898.37  4919.7  897.76
  4929.7  896.61  4945.3  896.17  4966.8  890.95  4974.7  888.41  4978.0  888.41
  4979.0  886.41  5021.0  886.41  5022.0  888.41  5023.2  888.50  5029.2  890.42
  5058.4  901.29  5060.9  902.06  5070.9  904.32  5081.3  907.70  5082.8  908.00
  5098.9  913.68  5101.3  914.76  5118.1  917.81  5141.7  920.31  5153.0  922.14
#Mann=3,-1,0
  4835.1    0.09       0  4978.0    0.04       0  5022.0    0.12       0
Bank Sta=4978,5022
XS Rating Curve= 0
Exp/Cntr=0.3,0.1

Type RM Length L Ch R = 1,57432,364,364,364
BEGIN DESCRIPTION:
North Hunting Creek 105.0
END DESCRIPTION:
XS GIS Cut Line= 4
      1465122.35       855436.35      1465004.29       855343.14
      1464913.18       855249.96      1464830.38       855163.02
#Sta/Elev= 30
  4753.8  915.96  4797.9  913.05  4836.4  909.86  4864.1  906.21  4883.3  902.40
  4893.5  900.89  4901.8  899.96  4909.0  899.54  4916.7  898.90  4929.2  897.09
  4934.2  897.01  4950.3  896.02  4957.2  893.57  4960.4  892.79  4970.9  889.10
  4971.4  887.85  4971.7  885.44  4977.9  884.36  4978.9  882.36  5021.1  882.36
  5022.1  884.36  5030.4  885.44  5031.4  884.36  5036.0  886.08  5039.8  888.58
  5050.7  894.14  5059.1  897.63  5078.3  899.39  5125.8  911.24  5154.6  916.88
#Mann=4,-1,0
  4753.8    0.06       0  4909.0    0.12       0  4977.9    0.04       0
  5022.1    0.12       0
Bank Sta=4977.9,5022.1
XS Rating Curve= 0
Exp/Cntr=0.3,0.1

Type RM Length L Ch R = 1,57068,348,348,348
BEGIN DESCRIPTION:
North Hunting Creek 104.5
END DESCRIPTION:
XS GIS Cut Line= 4
      1465370.59       855208.21      1465284.89       855103.47
      1465166.80       854991.09      1464964.87       854935.85
#Sta/Elev= 30
  4750.2  917.91  4783.9  914.97  4806.1  911.83  4850.4  903.53  4861.2  901.94
  4880.8  896.22  4917.4  893.79  4925.2  893.75  4952.5  891.53  4961.1  889.40
  4968.2  883.34  4977.9  882.66  4978.9  880.66  5021.1  880.66  5022.1  882.66
  5025.0  882.67  5025.5  890.41  5030.3  895.20  5036.4  897.18  5056.7  896.46
  5065.8  898.40  5078.1  899.20  5087.4  901.12  5099.6  902.05  5152.5  910.67
  5189.7  915.20  5198.6  917.04  5214.7  919.38  5245.0  922.65  5257.9  925.48
#Mann=3,-1,0
  4750.2    0.12       0  4977.9    0.04       0  5022.1    0.12       0
Bank Sta=4977.9,5022.1
XS Rating Curve= 0
Exp/Cntr=0.3,0.1

Type RM Length L Ch R = 1,56720,634,634,634
BEGIN DESCRIPTION:
North Hunting Creek 104.0
END DESCRIPTION:
XS GIS Cut Line= 4
      1465662.74       855090.51      1465563.36       854947.65
      1465486.75       854829.62      1465418.43       854738.53
#Sta/Elev= 30
  4704.3  916.31  4726.5  914.32  4750.5  912.56  4796.1  908.68  4817.0  907.25
  4839.1  905.35  4859.4  901.19  4867.6  900.47  4885.9  897.89  4899.4  896.55
  4919.8  895.37  4950.9  894.88  4960.9  889.09  4974.4  882.64  4977.9  882.64
  4978.9  880.64  5021.1  880.64  5022.1  882.64  5029.4  892.03  5032.7  894.97
  5036.3  895.62  5053.9  900.76  5063.8  903.10  5069.8  904.22  5095.9  910.51
  5103.6  911.40  5105.8  911.98  5118.7  913.99  5122.2  913.68  5132.9  914.26
#Mann=3,-1,0
  4704.3    0.12       0  4977.9    0.04       0  5022.1    0.12       0
Bank Sta=4977.9,5022.1
XS Rating Curve= 0
Exp/Cntr=0.3,0.1

Type RM Length L Ch R = 1,56086,318,318,318
BEGIN DESCRIPTION:
North Hunting Creek 103.0
END DESCRIPTION:
XS GIS Cut Line= 4
      1466199.03       854643.23      1466085.16       854500.39
      1465888.45       854384.43      1465741.40       854367.86
#Sta/Elev= 30
  4643.3  904.17  4669.0  903.89  4717.8  902.56  4765.6  900.00  4817.6  896.12
  4838.3  894.99  4897.0  893.72  4920.4  893.84  4938.6  893.40  4940.0  892.96
  4953.0  892.51  4956.1  891.83  4959.8  892.70  4969.5  882.60  4977.9  882.60
  4978.9  880.60  5021.1  880.60  5022.1  882.60  5029.1  882.60  5030.7  885.40
  5037.9  891.20  5042.2  895.96  5076.5  896.82  5088.4  897.91  5101.7  899.99
  5111.7  901.08  5154.7  909.35  5187.3  913.30  5196.9  914.09  5202.3  914.06
#Mann=4,-1,0
  4643.3    0.06       0  4897.0    0.12       0  4977.9    0.04       0
  5022.1    0.12       0
Bank Sta=4977.9,5022.1
XS Rating Curve= 0
Exp/Cntr=0.3,0.1

Type RM Length L Ch R = 1,55768,510,510,510
BEGIN DESCRIPTION:
North Hunting Creek 102.5
END DESCRIPTION:
XS GIS Cut Line= 4
      1466232.05       854636.50      1466262.85       854379.06
      1466141.85       854148.05      1466100.04       854000.62
#Sta/Elev= 30
  4532.9  904.01  4641.5  903.32  4696.5  901.67  4746.3  898.63  4799.3  893.47
  4821.7  892.82  4842.8  892.61  4892.0  894.37  4919.1  895.49  4925.9  895.10
  4945.5  892.09  4951.4  889.61  4962.1  882.65  4977.9  882.58  4978.9  880.58
  5021.1  880.58  5022.1  882.58  5029.8  882.58  5030.0  884.89  5031.2  890.47
  5038.3  892.77  5048.4  893.88  5072.9  906.93  5098.1  914.09  5112.8  916.09
  5130.3  917.26  5164.7  921.05  5171.3  922.83  5178.7  922.04  5206.2  924.84
#Mann=4,-1,0
  4532.9    0.06       0  4892.0    0.12       0  4977.9    0.04       0
  5022.1    0.12       0
#XS Ineff=2,0
    0.00 4917.10  895.39               0
Permanent Ineff=
       F       F
Bank Sta=4977.9,5022.1
XS Rating Curve= 0
Exp/Cntr=0.3,0.1

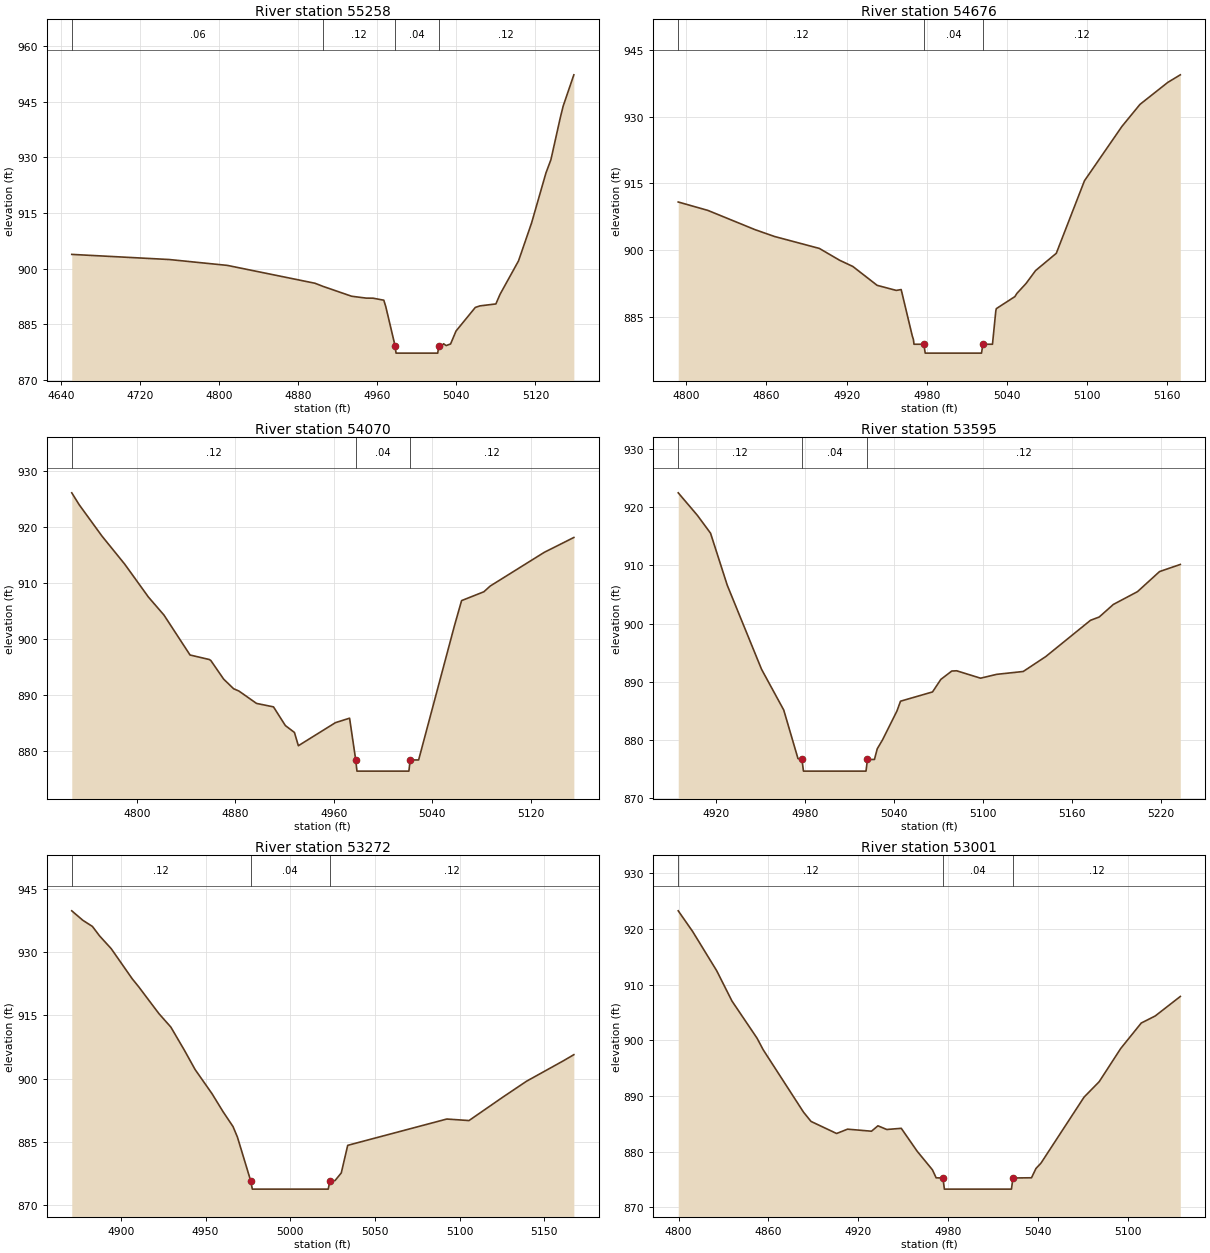
Type RM Length L Ch R = 1,55258,582,582,582
BEGIN DESCRIPTION:
North Hunting Creek 102.0
END DESCRIPTION:
XS GIS Cut Line= 4
      1466269.47       854651.52      1466389.55       854413.42
      1466491.01       854295.39      1466559.32       854243.65
#Sta/Elev= 30
  4650.8  903.86  4749.3  902.48  4808.2  900.90  4896.9  896.09  4905.0  895.25
  4934.0  892.59  4948.8  892.09  4955.6  892.07  4966.5  891.53  4968.5  889.82
  4977.9  879.28  4978.9  877.28  5021.1  877.28  5022.1  879.28  5025.2  879.29
  5027.0  879.80  5029.6  879.31  5034.1  879.75  5039.6  883.23  5059.1  889.58
  5063.8  890.00  5079.9  890.52  5084.2  893.15  5102.8  902.10  5116.0  912.29
  5130.6  925.80  5135.6  929.36  5144.9  940.44  5148.0  943.79  5158.8  952.20
#Mann=4,-1,0
  4650.8    0.06       0  4905.0    0.12       0  4977.9    0.04       0
  5022.1    0.12       0
Bank Sta=4977.9,5022.1
XS Rating Curve= 0
Exp/Cntr=0.3,0.1

Type RM Length L Ch R = 1,54676,606,606,606
BEGIN DESCRIPTION:
North Hunting Creek 101.0
END DESCRIPTION:
XS GIS Cut Line= 4
      1466464.09       854871.03      1466590.40       854871.03
      1466733.28       854868.96      1466832.67       854829.62
#Sta/Elev= 30
  4793.9  910.82  4816.1  908.93  4851.4  904.60  4866.0  903.06  4899.6  900.37
  4914.9  897.69  4924.7  896.31  4942.9  892.06  4957.2  890.92  4960.9  891.11
  4969.2  880.70  4970.1  879.84  4970.5  878.80  4977.9  878.80  4978.9  876.80
  5021.1  876.80  5022.1  878.80  5029.3  878.80  5031.8  886.32  5032.2  886.82
  5046.1  889.53  5047.6  890.25  5054.4  892.46  5061.6  895.39  5077.1  899.27
  5098.2  915.60  5126.3  927.85  5139.8  932.80  5160.6  937.74  5170.0  939.45
#Mann=3,-1,0
  4793.9    0.12       0  4977.9    0.04       0  5022.1    0.12       0
Bank Sta=4977.9,5022.1
XS Rating Curve= 0
Exp/Cntr=0.3,0.1

Type RM Length L Ch R = 1,54070,475,475,475
BEGIN DESCRIPTION:
North Hunting Creek 100.0
END DESCRIPTION:
XS GIS Cut Line= 4
      1466391.62       855463.24      1466497.22       855467.38
      1466673.23       855473.59      1466782.97       855411.47
#Sta/Elev= 30
  4747.2  926.06  4753.2  923.94  4771.7  918.34  4790.2  913.32  4809.5  907.43
  4822.1  904.22  4843.3  897.08  4859.0  896.27  4860.2  896.09  4870.6  892.77
  4878.7  891.05  4883.0  890.64  4897.3  888.43  4911.1  887.81  4920.7  884.48
  4928.1  883.24  4931.3  880.87  4961.4  884.99  4972.9  885.79  4977.9  878.33
  4978.9  876.33  5021.1  876.33  5022.1  878.33  5029.0  878.33  5058.1  902.31
  5063.9  906.80  5082.0  908.38  5087.2  909.41  5131.1  915.43  5155.1  918.08
#Mann=3,-1,0
  4747.2    0.12       0  4977.9    0.04       0  5022.1    0.12       0
Bank Sta=4977.9,5022.1
XS Rating Curve= 0
Exp/Cntr=0.3,0.1

Type RM Length L Ch R = 1,53595,323,323,323
BEGIN DESCRIPTION:
North Hunting Creek 99.0
END DESCRIPTION:
XS GIS Cut Line= 4
      1466913.42       855858.74      1466907.21       855773.84
      1466898.93       855676.52      1466884.43       855521.19
#Sta/Elev= 30
  4894.4  922.47  4907.3  918.61  4916.2  915.54  4927.5  906.59  4950.6  892.18
  4965.6  885.17  4975.2  876.84  4977.9  876.68  4978.9  874.68  5021.1  874.68
  5022.1  876.68  5026.8  876.68  5028.7  878.52  5032.2  880.02  5042.0  885.01
  5044.4  886.69  5066.0  888.28  5071.6  890.43  5079.0  891.87  5082.3  891.91
  5098.4  890.64  5109.3  891.30  5127.2  891.79  5142.4  894.35  5172.6  900.58
  5178.5  901.15  5188.0  903.30  5204.3  905.50  5219.2  908.95  5233.2  910.17
#Mann=3,-1,0
  4894.4    0.12       0  4977.9    0.04       0  5022.1    0.12       0
Bank Sta=4977.9,5022.1
XS Rating Curve= 0
Exp/Cntr=0.3,0.1

Type RM Length L Ch R = 1,53272,271,271,271
BEGIN DESCRIPTION:
North Little Hunting Creek 98.5
END DESCRIPTION:
XS GIS Cut Line= 3
      1467232.95       855625.32      1467148.24       855554.73
      1467005.93       855434.76
#Sta/Elev= 28
  4871.0  939.75  4877.5  937.52  4883.2  936.05  4887.4  933.82  4894.3  930.78
  4906.7  923.65  4910.5  921.77  4922.4  915.43  4929.5  912.21  4937.6  906.66
  4943.8  902.17  4953.8  896.44  4960.3  892.19  4966.2  888.65  4968.8  886.16
  4976.6  875.84  4977.6  873.84  5022.4  873.84  5023.4  875.84  5026.4  875.86
  5030.1  877.67  5033.9  884.21  5092.4  890.44  5105.5  890.08  5125.5  895.63
  5139.5  899.40  5161.4  904.27  5167.4  905.68
#Mann=3,-1,0
  4871.0    0.12       0  4976.6    0.04       0  5023.4    0.12       0
Bank Sta=4976.6,5023.4
XS Rating Curve= 0
Exp/Cntr=0.3,0.1

Type RM Length L Ch R = 1,53001,641,641,641
BEGIN DESCRIPTION:
North Hunting Creek 98.0
END DESCRIPTION:
XS GIS Cut Line= 4
      1467412.41       855421.80      1467339.98       855361.78
      1467228.16       855283.09      1467135.02       855235.49
#Sta/Elev= 30
  4799.8  923.26  4809.4  919.56  4825.5  912.50  4835.7  907.06  4852.4  900.41
  4856.6  898.29  4883.5  887.10  4888.5  885.44  4905.6  883.27  4912.9  884.05
  4928.9  883.68  4933.2  884.65  4939.1  883.99  4948.8  884.20  4959.4  880.09
  4969.6  876.75  4972.1  875.31  4976.6  875.28  4977.6  873.28  5022.4  873.28
  5023.4  875.28  5035.8  875.32  5038.8  877.00  5042.1  877.94  5070.9  889.80
  5081.0  892.57  5095.4  898.54  5109.1  903.11  5118.4  904.37  5135.2  907.88
#Mann=3,-1,0
  4799.8    0.12       0  4976.6    0.04       0  5023.4    0.12       0
Bank Sta=4976.6,5023.4
XS Rating Curve= 0
Exp/Cntr=0.3,0.1

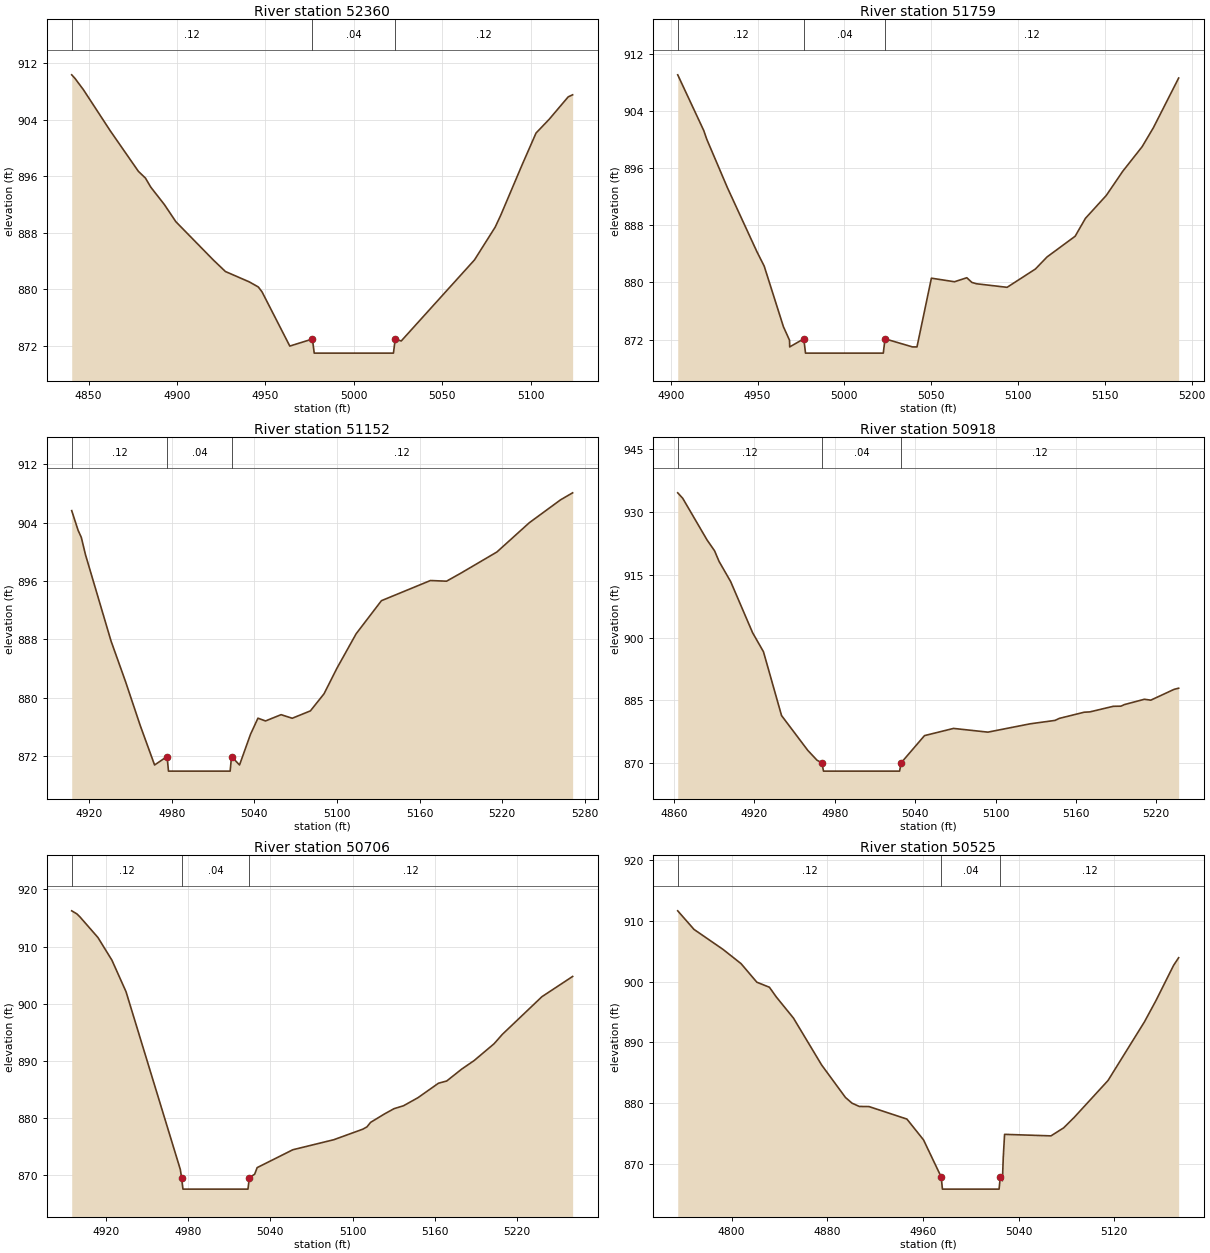
Type RM Length L Ch R = 1,52360,601,601,601
BEGIN DESCRIPTION:
North Hunting Creek 97.0
END DESCRIPTION:
XS GIS Cut Line= 4
      1467834.81       854916.57      1467756.18       854887.60
      1467665.07       854821.34      1467598.81       854765.43
#Sta/Elev= 28
  4840.5  910.34  4842.3  909.85  4847.1  908.24  4862.3  902.41  4878.2  896.67
  4882.2  895.71  4885.2  894.43  4892.9  891.96  4899.4  889.53  4920.7  884.08
  4927.4  882.48  4940.9  881.01  4946.0  880.29  4948.1  879.60  4963.8  871.92
  4976.6  872.92  4977.6  870.92  5022.4  870.92  5023.4  872.92  5026.8  872.64
  5068.2  884.12  5079.9  888.76  5083.0  890.42  5095.1  897.57  5103.0  902.09
  5110.4  904.03  5121.2  907.22  5123.7  907.51
#Mann=3,-1,0
  4840.5    0.12       0  4976.6    0.04       0  5023.4    0.12       0
Bank Sta=4976.6,5023.4
XS Rating Curve= 0
Exp/Cntr=0.3,0.1

Type RM Length L Ch R = 1,51759,607,607,607
BEGIN DESCRIPTION:
North Hunting Creek 96.0
END DESCRIPTION:
XS GIS Cut Line= 4
      1468168.22       854450.68      1468108.19       854403.07
      1468012.94       854338.88      1467932.22       854285.06
#Sta/Elev= 30
  4904.0  909.05  4919.0  901.25  4920.7  900.05  4932.7  893.21  4949.6  884.30
  4953.8  882.28  4964.9  873.78  4968.4  871.90  4968.5  870.97  4976.6  872.10
  4977.6  870.10  5022.4  870.10  5023.4  872.10  5039.2  870.97  5041.8  870.97
  5050.1  880.59  5063.4  880.09  5070.5  880.65  5073.4  880.00  5076.0  879.81
  5093.7  879.31  5110.0  881.87  5116.7  883.56  5132.9  886.46  5138.8  888.96
  5150.8  892.16  5160.3  895.55  5171.5  899.00  5178.0  901.67  5192.5  908.60
#Mann=3,-1,0
  4904.0    0.12       0  4976.6    0.04       0  5023.4    0.12       0
Bank Sta=4976.6,5023.4
XS Rating Curve= 0
Exp/Cntr=0.3,0.1

Type RM Length L Ch R = 1,51152,234,234,234
BEGIN DESCRIPTION:
North Hunting Creek 95.0
END DESCRIPTION:
XS GIS Cut Line= 4
      1468491.29       853885.41      1468435.35       853877.12
      1468255.20       853866.77      1468149.61       853937.16
#Sta/Elev= 30
  4907.3  905.64  4911.9  902.97  4914.3  901.96  4917.3  899.61  4935.9  887.77
  4946.4  882.23  4957.0  876.26  4967.5  870.81  4976.6  871.97  4977.6  869.97
  5022.4  869.97  5023.4  871.97  5029.2  870.81  5037.2  875.02  5042.6  877.22
  5048.1  876.84  5059.4  877.70  5067.5  877.21  5080.7  878.22  5090.6  880.56
  5100.0  884.07  5113.9  888.77  5132.3  893.31  5167.9  896.07  5179.6  895.98
  5190.1  897.09  5216.2  899.98  5239.7  903.98  5262.5  907.13  5271.2  908.08
#Mann=3,-1,0
  4907.3    0.12       0  4976.6    0.04       0  5023.4    0.12       0
Bank Sta=4976.6,5023.4
XS Rating Curve= 0
Exp/Cntr=0.3,0.1

Type RM Length L Ch R = 1,50918,212,212,212
BEGIN DESCRIPTION:
North Little Hunting Creek 94.5
END DESCRIPTION:
XS GIS Cut Line= 4
      1468514.57       853600.19      1468437.27       853627.16
      1468318.20       853665.92      1468153.91       853637.05
#Sta/Elev= 30
  4862.8  934.55  4866.5  933.26  4884.7  923.29  4890.3  920.71  4893.6  918.21
  4902.3  913.36  4918.7  901.14  4926.8  896.60  4940.3  881.36  4959.9  873.04
  4966.8  870.69  4970.4  870.09  4971.6  868.09  5028.4  868.09  5029.6  870.09
  5047.0  876.57  5068.7  878.29  5094.3  877.40  5125.9  879.39  5144.4  880.20
  5147.7  880.69  5166.2  882.16  5170.5  882.24  5187.9  883.57  5193.6  883.60
  5196.2  883.98  5211.1  885.25  5215.9  885.04  5233.4  887.63  5236.7  887.89
#Mann=3,-1,0
  4862.8    0.12       0  4970.4    0.04       0  5029.6    0.12       0
Bank Sta=4970.4,5029.6
XS Rating Curve= 0
Exp/Cntr=0.3,0.1

Type RM Length L Ch R = 1,50706,181,181,181
BEGIN DESCRIPTION:
North Hunting Creek 94.0
END DESCRIPTION:
XS GIS Cut Line= 4
      1468381.48       853417.45      1468302.83       853452.64
      1468207.58       853487.84      1468033.62       853452.63
#Sta/Elev= 30
  4895.2  916.26  4899.0  915.72  4901.3  915.17  4914.3  911.59  4924.5  907.62
  4934.8  902.09  4974.4  870.92  4975.3  869.49  4976.3  867.49  5023.7  867.49
  5024.7  869.49  5028.6  870.11  5030.4  871.26  5056.4  874.39  5086.3  876.15
  5107.5  878.00  5110.5  878.41  5113.1  879.19  5123.2  880.66  5130.2  881.59
  5137.1  882.10  5147.5  883.49  5162.6  886.05  5168.6  886.44  5179.5  888.52
  5188.6  890.02  5203.1  892.96  5209.2  894.62  5238.0  901.21  5260.4  904.76
#Mann=3,-1,0
  4895.2    0.12       0  4975.3    0.04       0  5024.7    0.12       0
Bank Sta=4975.3,5024.7
XS Rating Curve= 0
Exp/Cntr=0.3,0.1

Type RM Length L Ch R = 1,50525,323,323,323
BEGIN DESCRIPTION:
North Little Hunting Creek 93.5
END DESCRIPTION:
XS GIS Cut Line= 4
      1468379.81       853377.35      1468284.51       853267.00
      1468118.94       853332.22      1468028.58       853362.34
#Sta/Elev= 30
  4754.9  911.66  4768.5  908.60  4792.8  905.30  4807.9  902.95  4821.1  899.89
  4831.6  899.06  4837.4  897.45  4851.7  893.98  4875.3  886.24  4895.2  880.89
  4900.7  879.95  4906.8  879.41  4914.9  879.39  4946.6  877.33  4960.5  873.90
  4975.3  867.78  4976.3  865.78  5023.7  865.78  5024.7  867.78  5026.5  867.16
  5027.2  871.00  5028.3  874.81  5067.1  874.56  5077.7  875.88  5086.5  877.60
  5114.8  883.68  5145.3  893.36  5154.8  896.82  5169.7  902.68  5173.9  903.93
#Mann=3,-1,0
  4754.9    0.12       0  4975.3    0.04       0  5024.7    0.12       0
Bank Sta=4975.3,5024.7
XS Rating Curve= 0
Exp/Cntr=0.3,0.1

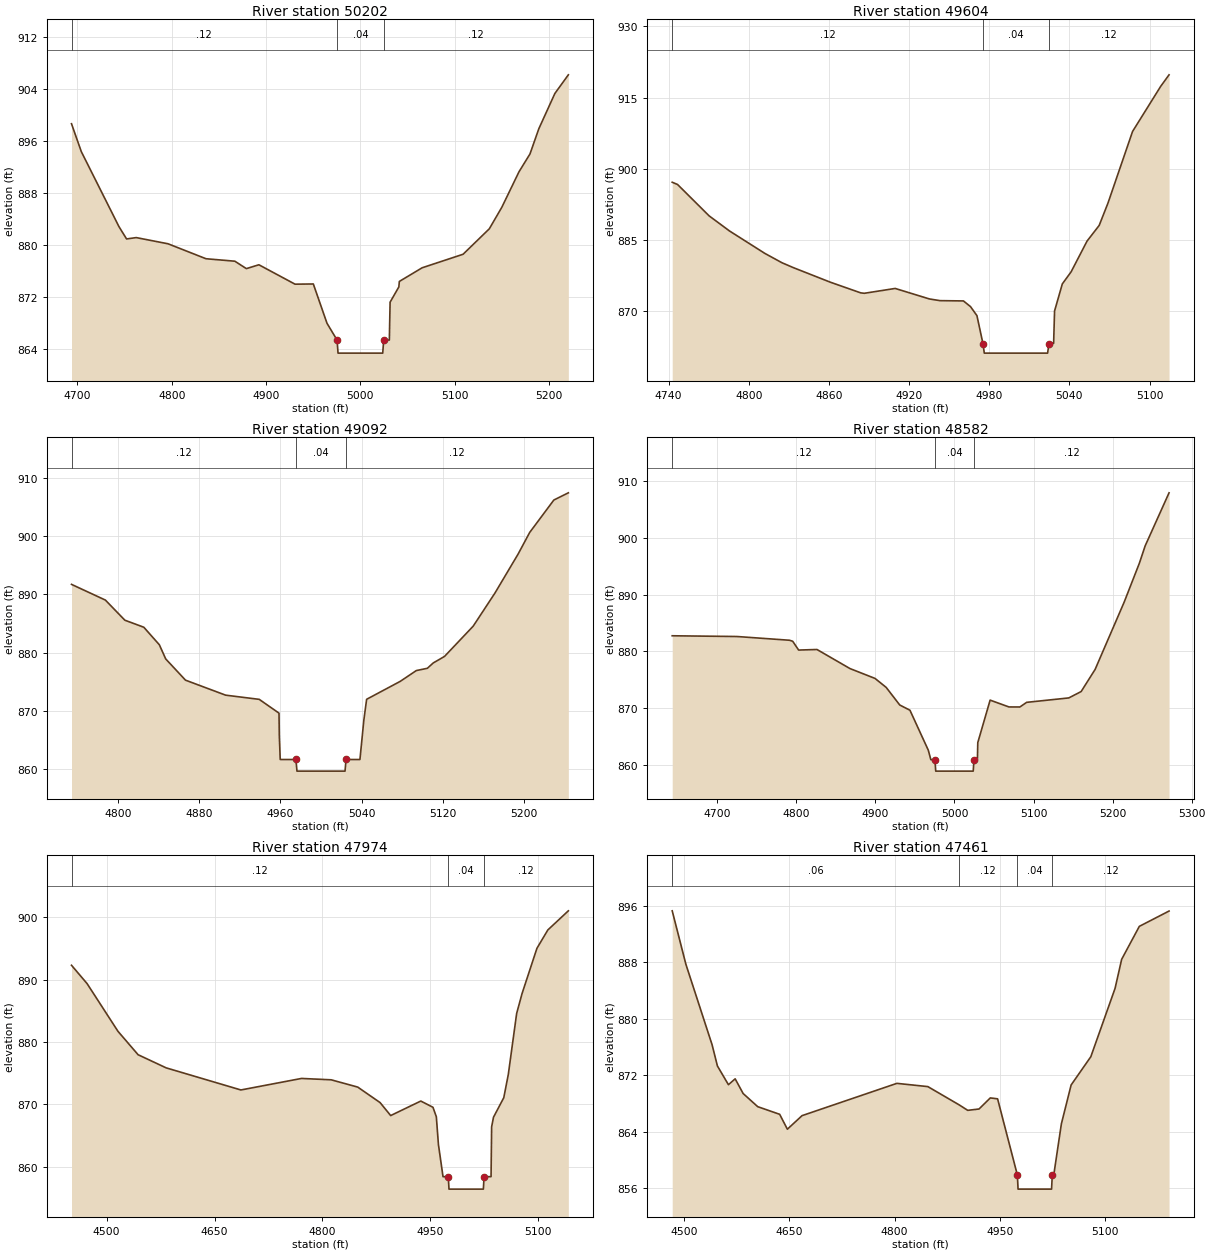
Type RM Length L Ch R = 1,50202,598,598,598
BEGIN DESCRIPTION:
North Hunting Creek 93.0
END DESCRIPTION:
XS GIS Cut Line= 4
      1468358.76       852914.26      1468265.55       852951.54
      1467948.75       853042.65      1467884.59       853115.09
#Sta/Elev= 30
  4693.7  898.59  4704.1  894.30  4744.0  882.78  4752.1  880.88  4762.3  881.09
  4796.0  880.14  4836.3  877.84  4866.9  877.46  4879.1  876.32  4892.4  876.91
  4930.7  873.93  4950.1  873.96  4964.6  867.92  4975.3  865.33  4976.3  863.33
  5023.7  863.33  5024.7  865.33  5030.7  865.34  5031.5  871.16  5040.8  873.51
  5041.3  874.35  5065.5  876.45  5108.9  878.53  5136.7  882.44  5150.0  885.76
  5168.2  891.21  5179.8  893.94  5189.2  897.82  5206.2  903.24  5220.5  906.11
#Mann=3,-1,0
  4693.7    0.12       0  4975.3    0.04       0  5024.7    0.12       0
Bank Sta=4975.3,5024.7
XS Rating Curve= 0
Exp/Cntr=0.3,0.1

Type RM Length L Ch R = 1,49604,512,512,512
BEGIN DESCRIPTION:
North Hunting Creek 92.0
END DESCRIPTION:
XS GIS Cut Line= 4
      1468406.38       852587.12      1468304.90       852514.64
      1468155.81       852431.81      1468095.76       852384.19
#Sta/Elev= 30
  4742.7  897.20  4746.7  896.73  4770.3  890.13  4785.6  886.94  4812.1  882.21
  4824.8  880.26  4833.3  879.23  4861.1  876.15  4883.8  873.91  4886.5  873.82
  4909.6  874.84  4935.2  872.63  4943.1  872.27  4960.7  872.21  4966.0  871.01
  4970.8  869.11  4975.3  863.22  4976.3  861.22  5023.7  861.22  5024.7  863.22
  5028.2  863.27  5028.9  870.09  5034.7  875.79  5041.3  878.34  5053.2  884.80
  5062.3  888.11  5068.8  892.75  5087.3  907.90  5108.4  917.42  5114.6  919.82
#Mann=3,-1,0
  4742.7    0.12       0  4975.3    0.04       0  5024.7    0.12       0
#XS Ineff=2,0
    0.00 4909.60  874.84               0
Permanent Ineff=
       F       F
Bank Sta=4975.3,5024.7
XS Rating Curve= 0
Exp/Cntr=0.3,0.1

Type RM Length L Ch R = 1,49092,510,510,510
BEGIN DESCRIPTION:
North Hunting Creek 91.0
END DESCRIPTION:
XS GIS Cut Line= 4
      1468679.70       852175.07      1468580.29       852092.23
      1468408.43       851984.55      1468255.20       852021.82
#Sta/Elev= 30
  4754.0  891.74  4787.4  889.04  4806.6  885.58  4825.3  884.37  4840.6  881.36
  4846.9  878.92  4866.4  875.27  4906.0  872.69  4939.1  871.97  4958.6  869.60
  4958.9  865.77  4959.8  861.63  4975.3  861.63  4976.3  859.63  5023.7  859.63
  5024.7  861.63  5038.4  861.63  5042.3  868.46  5045.0  871.98  5078.1  875.06
  5094.0  876.92  5104.9  877.31  5110.6  878.22  5121.8  879.35  5150.1  884.56
  5171.5  890.24  5194.3  896.93  5205.8  900.67  5229.6  906.24  5243.9  907.48
#Mann=3,-1,0
  4754.0    0.12       0  4975.3    0.04       0  5024.7    0.12       0
Bank Sta=4975.3,5024.7
XS Rating Curve= 0
Exp/Cntr=0.3,0.1

Type RM Length L Ch R = 1,48582,608,608,608
BEGIN DESCRIPTION:
North Hunting Creek 90.0
END DESCRIPTION:
XS GIS Cut Line= 4
      1468729.38       851992.83      1468857.76       851758.85
      1468752.16       851524.87      1468669.32       851460.67
#Sta/Elev= 30
  4643.0  882.73  4724.9  882.60  4791.5  881.94  4795.4  881.76  4802.9  880.21
  4826.1  880.31  4867.8  876.95  4899.5  875.21  4913.6  873.63  4930.8  870.52
  4943.7  869.60  4966.9  862.55  4970.1  860.89  4975.3  860.86  4976.3  858.86
  5023.7  858.86  5024.7  860.86  5029.0  860.90  5029.5  863.89  5045.1  871.38
  5068.9  870.18  5082.7  870.17  5091.3  870.99  5144.6  871.77  5160.2  872.89
  5177.9  876.80  5214.6  888.65  5233.9  895.54  5241.2  898.59  5271.4  907.94
#Mann=3,-1,0
  4643.0    0.12       0  4975.3    0.04       0  5024.7    0.12       0
Bank Sta=4975.3,5024.7
XS Rating Curve= 0
Exp/Cntr=0.3,0.1

Type RM Length L Ch R = 1,47974,513,513,513
BEGIN DESCRIPTION:
North Hunting Creek 89.0
END DESCRIPTION:
XS GIS Cut Line= 4
      1469284.30       851796.15      1469338.15       851676.03
      1469234.62       851245.33      1469244.97       851129.40
#Sta/Elev= 30
  4451.1  892.31  4472.8  889.36  4515.7  881.71  4543.7  877.95  4582.7  875.84
  4686.7  872.29  4771.0  874.14  4812.3  873.92  4849.2  872.75  4880.3  870.26
  4895.0  868.18  4936.9  870.51  4953.8  869.51  4958.5  867.99  4961.4  863.55
  4967.8  858.37  4975.1  858.37  4976.1  856.37  5023.9  856.37  5024.9  858.37
  5034.6  858.37  5035.4  866.37  5038.0  867.91  5052.3  871.05  5058.6  874.78
  5070.2  884.57  5077.7  887.76  5098.4  895.03  5113.6  897.98  5142.1  901.05
#Mann=3,-1,0
  4451.1    0.12       0  4975.1    0.04       0  5024.9    0.12       0
#XS Ineff=2,0
    0.00 4936.90  870.51               0
Permanent Ineff=
       F       F
Bank Sta=4975.1,5024.9
XS Rating Curve= 0
Exp/Cntr=0.3,0.1

Type RM Length L Ch R = 1,47461,357,357,357
BEGIN DESCRIPTION:
North Hunting Creek 88.0
END DESCRIPTION:
XS GIS Cut Line= 4
      1470014.20       851531.06      1469954.17       851450.32
      1469695.34       851067.25      1469575.25       850984.44
#Sta/Elev= 30
  4482.7  895.25  4502.2  887.69  4539.6  876.29  4547.2  873.29  4562.9  870.64
  4572.5  871.47  4583.9  869.39  4604.7  867.53  4636.0  866.45  4647.0  864.34
  4667.9  866.26  4803.2  870.83  4847.4  870.37  4892.0  867.79  4904.3  867.01
  4920.4  867.20  4936.5  868.77  4946.9  868.64  4975.1  857.86  4976.1  855.86
  5023.9  855.86  5024.9  857.86  5027.4  858.11  5037.9  865.10  5051.8  870.60
  5079.9  874.60  5114.5  884.28  5123.9  888.39  5149.1  893.05  5191.5  895.22
#Mann=4,-1,0
  4482.7    0.06       0  4892.0    0.12       0  4975.1    0.04       0
  5024.9    0.12       0
#XS Ineff=2,0
    0.00 4821.90  870.39               0
Permanent Ineff=
       F       F
Bank Sta=4975.1,5024.9
XS Rating Curve= 0
Exp/Cntr=0.3,0.1

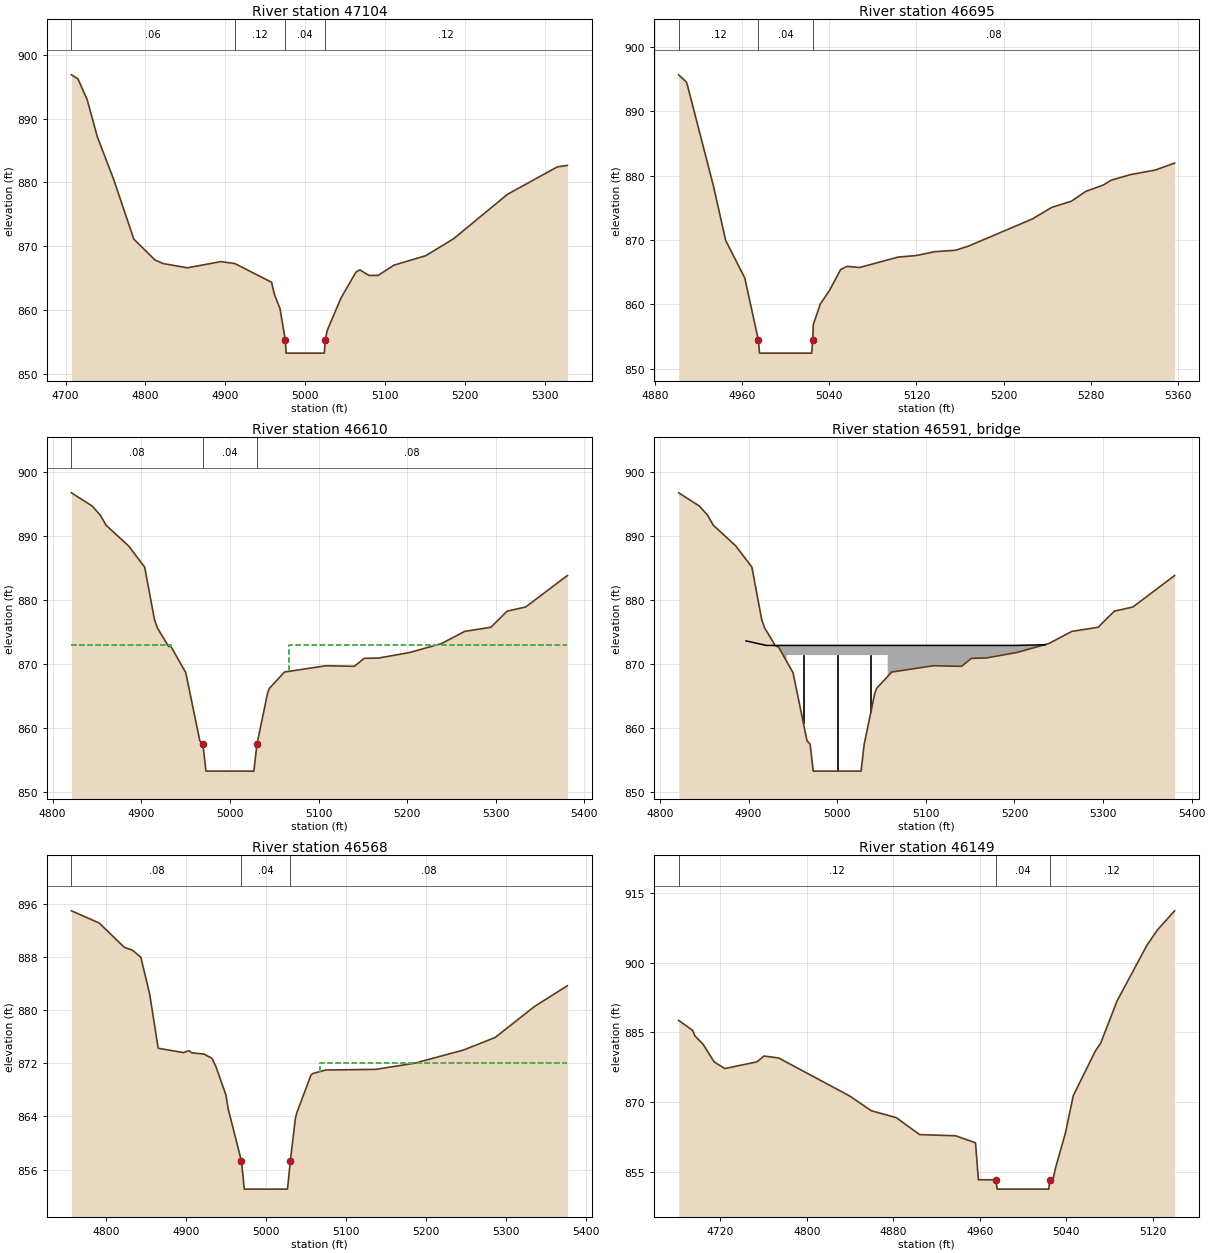
Type RM Length L Ch R = 1,47104,409,409,409
BEGIN DESCRIPTION:
North Hunting Creek 87.0
END DESCRIPTION:
XS GIS Cut Line= 4
      1470287.52       850914.03      1470181.94       850947.16
      1469911.99       850864.82      1469689.10       850911.96
#Sta/Elev= 30
  4707.4  896.85  4715.6  896.20  4727.1  892.95  4739.8  887.12  4759.9  880.58
  4785.5  871.10  4811.8  867.85  4822.3  867.27  4852.5  866.61  4894.4  867.58
  4912.0  867.27  4957.9  864.34  4961.4  862.43  4968.4  860.23  4975.1  855.24
  4976.1  853.24  5023.9  853.24  5024.9  855.24  5027.6  856.83  5044.6  861.83
  5063.3  865.91  5068.4  866.29  5079.7  865.42  5091.2  865.42  5110.9  867.02
  5150.9  868.51  5185.7  871.17  5253.0  878.12  5315.4  882.42  5328.1  882.66
#Mann=4,-1,0
  4707.4    0.06       0  4912.0    0.12       0  4975.1    0.04       0
  5024.9    0.12       0
#XS Ineff=2,0
    0.00 4894.40  867.58               0
Permanent Ineff=
       F       F
Bank Sta=4975.1,5024.9
XS Rating Curve= 0
Exp/Cntr=0.3,0.1

Type RM Length L Ch R = 1,46695,85,85,85
BEGIN DESCRIPTION:
North Hunting Creek 86.0
END DESCRIPTION:
XS GIS Cut Line= 4
      1469918.98       850514.37      1469869.27       850593.08
      1469792.66       850713.17      1469680.82       850901.64
#Sta/Elev= 30
  4902.0  895.65  4909.0  894.54  4910.1  893.96  4933.7  878.48  4945.1  869.90
  4962.6  864.07  4975.1  854.39  4976.1  852.39  5023.9  852.39  5024.9  854.39
  5025.4  856.83  5031.8  860.01  5040.4  862.18  5050.5  865.39  5056.4  865.88
  5067.9  865.70  5102.9  867.31  5120.1  867.57  5136.9  868.16  5155.8  868.38
  5167.5  869.01  5226.3  873.25  5244.0  875.04  5262.1  876.01  5275.1  877.52
  5291.3  878.52  5298.5  879.27  5316.5  880.15  5339.0  880.85  5356.7  881.93
#Mann=3,-1,0
  4902.0    0.12       0  4975.1    0.04       0  5024.9    0.08       0
Bank Sta=4975.1,5024.9
XS Rating Curve= 0
Exp/Cntr=0.5,0.3

Type RM Length L Ch R = 1,46610,42,42,42
BEGIN DESCRIPTION:
Sloans Mill Rd - US
END DESCRIPTION:
XS GIS Cut Line= 3
      1469931.37       850495.75      1469836.14       850477.12
      1469610.44       850880.89
#Sta/Elev= 30
  4821.2  896.69  4844.5  894.64  4853.6  893.24  4860.3  891.63  4885.6  888.42
  4903.8  885.11  4914.9  876.91  4918.2  875.62  4930.7  872.76  4933.6  872.71
  4950.2  868.65  4966.0  858.05  4969.5  857.50  4973.0  853.30  5027.0  853.30
  5030.5  857.50  5042.5  865.46  5044.6  866.22  5061.6  868.75  5108.4  869.73
  5140.4  869.64  5151.6  870.89  5167.7  870.93  5203.0  871.80  5238.8  873.19
  5264.9  875.09  5294.5  875.73  5312.8  878.24  5333.7  878.89  5380.8  883.80
#Mann=3,-1,0
  4821.2    0.08       0  4969.5    0.04       0  5030.5    0.08       0
#XS Ineff=2,0
    0.00 4933.00  872.90 5067.00    0.00  872.90
Permanent Ineff=
       F       F
Bank Sta=4969.5,5030.5
XS Rating Curve= 0
Exp/Cntr=0.5,0.3

Type RM Length L Ch R =3,46591,,,
BEGIN DESCRIPTION:
Sloans Mill Rd - TOR
Structure ID: LDS_NLHC_04
Approximate Survey Structure
END DESCRIPTION:
Bridge Culvert--1,0,-1,-1,0
Deck Dist Width WeirC Skew NumUp NumDn MinLoCord MaxHiCord MaxSubmerge Is_Ogee
9,20,3,,8,8,,,,0,1,1,,,
  4897.1  4919.9  4943.0  4943.0  5057.0  5057.0  5200.4  5234.8
  873.61  872.90  872.90  872.90  872.90  872.90  872.90  873.00
  833.30  833.30  833.30  871.40  871.40  833.30  833.30  833.30
  4897.1  4919.9  4943.0  4943.0  5057.0  5057.0  5200.4  5234.8
  873.61  872.90  872.90  872.90  872.90  872.90  872.90  873.00
  833.30  833.30  833.30  871.40  871.40  833.30  833.30  833.30
Pier Skew, UpSta & Num, DnSta & Num=,4962,2,4962,2,0,0,0,0,0
       1       1
  860.71  871.40
       1       1
  859.65  871.40
Pier Skew, UpSta & Num, DnSta & Num=,5000,2,5000,2,0,0,0,0,0
       1       1
  853.30  871.40
       1       1
  853.05  871.40
Pier Skew, UpSta & Num, DnSta & Num=,5038,2,5038,2,0,0,0,0,0
       1       1
  862.48  871.40
       1       1
  864.23  871.40
BR Coef=1,1,0,1.25,0,,,0.8,0,2,0,
WSPro=,,,, 1 ,,,, 0 ,,,, 0 ,,,,-1 ,-1 ,-1 , 0 , 0 , 0 , 0 , 0
BC Design=,,0,,0,,,,,,

Type RM Length L Ch R = 1,46568,419,419,419
BEGIN DESCRIPTION:
Sloans Mill Rd - DS
END DESCRIPTION:
XS GIS Cut Line= 3
      1469952.12       850475.05      1469809.22       850441.92
      1469573.15       850851.93
#Sta/Elev= 30
  4757.0  894.92  4791.5  893.10  4823.1  889.43  4833.3  889.00  4843.7  887.93
  4854.7  882.44  4865.4  874.24  4897.2  873.59  4903.7  873.88  4907.7  873.55
  4922.7  873.37  4932.6  872.72  4937.6  871.47  4950.1  867.20  4952.8  865.15
  4969.5  857.25  4973.0  853.05  5027.0  853.05  5030.5  857.25  5036.8  863.66
  5038.7  864.56  5056.3  870.20  5058.6  870.44  5074.7  870.97  5137.3  871.07
  5185.6  871.99  5246.8  873.97  5286.6  875.87  5335.7  880.53  5376.8  883.65
#Mann=3,-1,0
  4757.0    0.08       0  4969.5    0.04       0  5030.5    0.08       0
#XS Ineff=2,0
    0.00 4933.00  872.00 5067.00    0.00  872.00
Permanent Ineff=
       F       F
Bank Sta=4969.5,5030.5
XS Rating Curve= 0
Exp/Cntr=0.5,0.3

Type RM Length L Ch R = 1,46149,290,290,290
BEGIN DESCRIPTION:
North Little Hunting Creek 85.5
END DESCRIPTION:
XS GIS Cut Line= 4
      1469915.56       850426.77      1469748.28       850283.39
      1469668.63       850193.78      1469606.93       850092.27
#Sta/Elev= 30
  4681.4  887.58  4694.3  885.44  4696.3  884.27  4703.9  882.48  4714.2  878.66
  4724.1  877.23  4753.7  878.66  4760.3  879.92  4773.9  879.50  4839.7  871.33
  4859.6  868.17  4882.9  866.67  4904.3  863.04  4937.7  862.78  4956.1  861.28
  4958.8  853.33  4975.1  853.32  4976.1  851.32  5023.9  851.32  5024.9  853.32
  5027.8  853.35  5030.0  855.73  5039.3  863.36  5046.6  871.42  5067.1  881.02
  5072.0  882.71  5087.2  891.80  5114.7  903.70  5124.7  907.08  5140.4  911.12
#Mann=3,-1,0
  4681.4    0.12       0  4975.1    0.04       0  5024.9    0.12       0
Bank Sta=4975.1,5024.9
XS Rating Curve= 0
Exp/Cntr=0.3,0.1