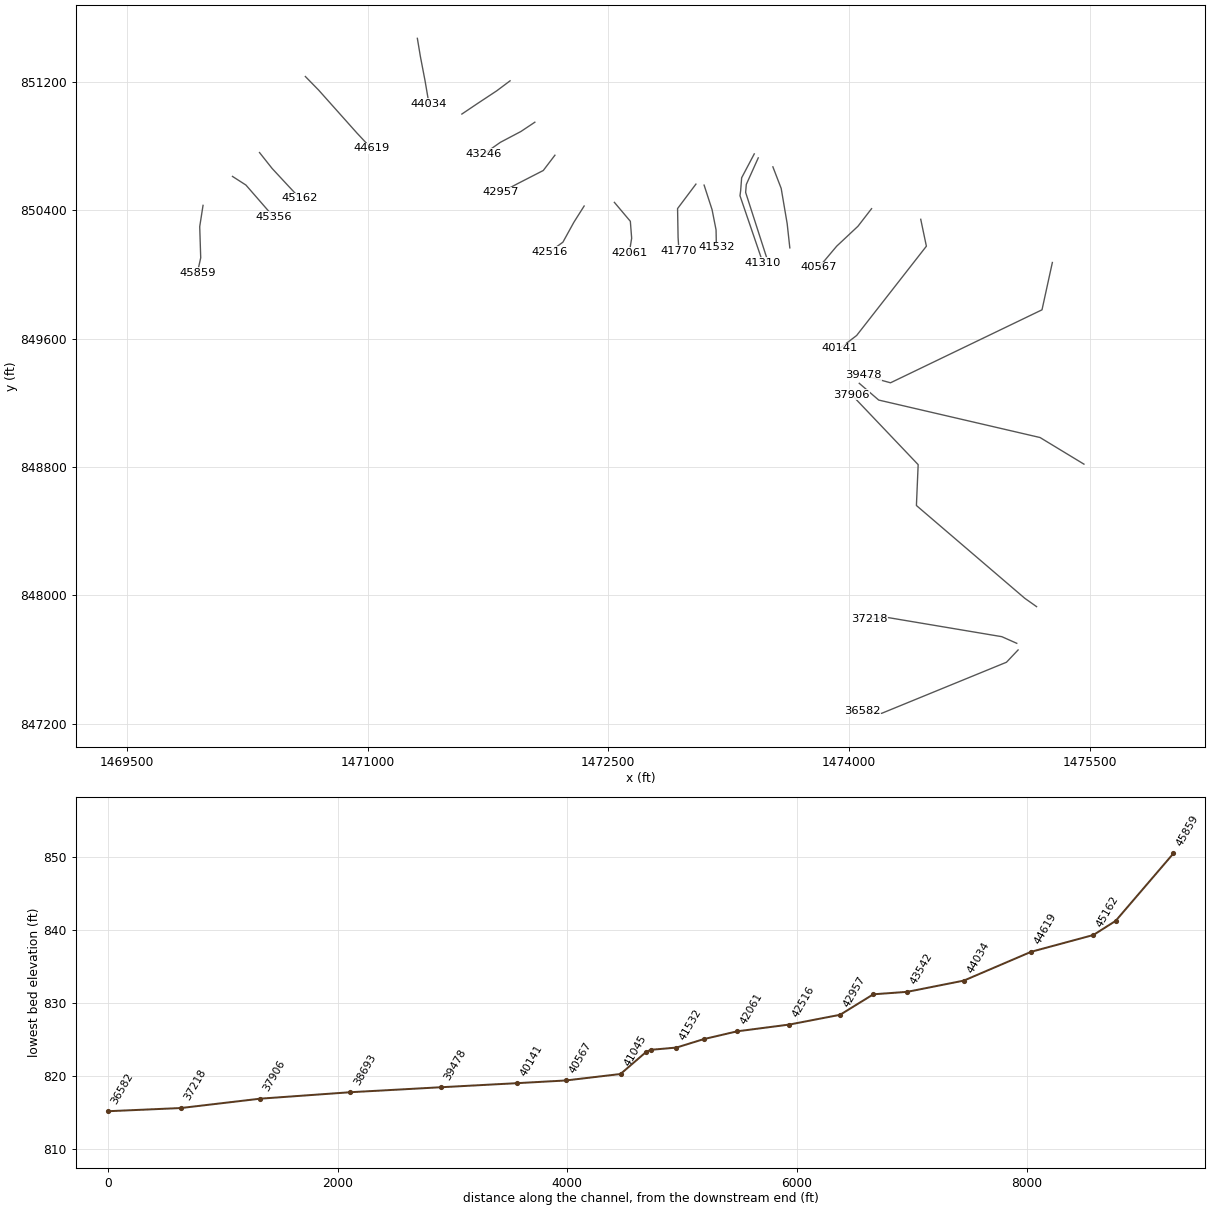
HEC-RAS study North Little Hunting Creek.prj: North Little Hunting Creek Limited Detail Study

--- North Little Hunting Creek.g01 (geometry) --- (continued)

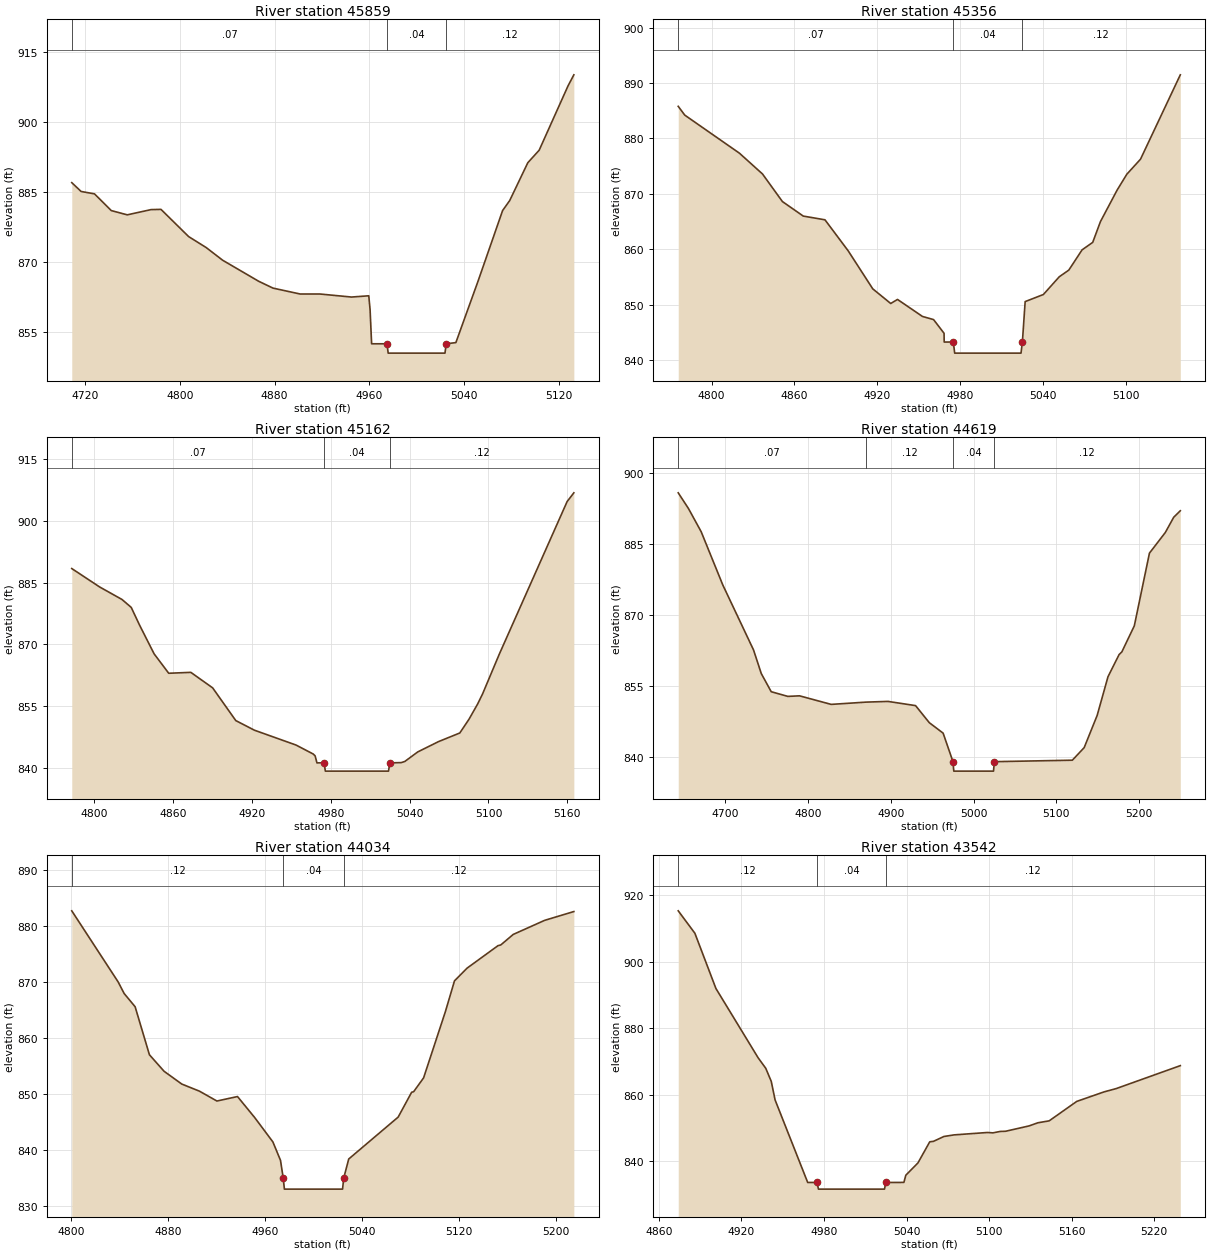
Type RM Length L Ch R = 1,45859,503,503,503
BEGIN DESCRIPTION:
North Hunting Creek 85.0
END DESCRIPTION:
XS GIS Cut Line= 4
      1469974.88       850431.58      1469954.17       850299.04
      1469960.38       850104.40      1469939.68       850011.26
#Sta/Elev= 30
  4708.6  887.04  4716.5  885.15  4727.8  884.64  4742.0  881.06  4755.5  880.15
  4775.6  881.27  4784.0  881.32  4807.4  875.49  4822.2  873.15  4836.1  870.44
  4866.6  865.93  4878.7  864.47  4901.6  863.21  4918.3  863.21  4945.0  862.56
  4959.6  862.83  4960.7  859.87  4962.0  852.56  4975.0  852.56  4976.0  850.56
  5024.0  850.56  5025.0  852.56  5033.2  852.81  5052.1  866.07  5072.7  881.07
  5078.7  883.21  5094.0  891.30  5103.6  893.98  5128.0  907.75  5132.9  910.11
#Mann=3,-1,0
  4708.6    0.07       0  4975.0    0.04       0  5025.0    0.12       0
Bank Sta=4975,5025
XS Rating Curve= 0
Exp/Cntr=0.3,0.1

Type RM Length L Ch R = 1,45356,194,194,194
BEGIN DESCRIPTION:
North Little Hunting Creek 84.5
END DESCRIPTION:
XS GIS Cut Line= 3
      1470158.45       850611.97      1470242.12       850558.19
      1470415.35       850359.06
#Sta/Elev= 30
  4775.9  885.80  4780.6  884.22  4820.2  877.35  4836.9  873.60  4851.3  868.63
  4866.4  866.01  4882.1  865.34  4898.9  859.75  4916.7  852.89  4929.7  850.25
  4934.6  850.98  4952.7  847.91  4960.7  847.35  4968.3  844.88  4968.4  843.30
  4975.0  843.30  4976.0  841.30  5024.0  841.30  5025.0  843.30  5027.0  850.59
  5040.2  851.87  5051.7  855.07  5058.6  856.27  5068.2  859.92  5075.9  861.27
  5081.5  865.02  5093.6  870.71  5100.6  873.56  5110.5  876.27  5139.3  891.48
#Mann=3,-1,0
  4775.9    0.07       0  4975.0    0.04       0  5025.0    0.12       0
Bank Sta=4975,5025
XS Rating Curve= 0
Exp/Cntr=0.3,0.1

Type RM Length L Ch R = 1,45162,543,543,543
BEGIN DESCRIPTION:
North Hunting Creek 84.0
END DESCRIPTION:
XS GIS Cut Line= 4
      1470326.87       850760.82      1470405.57       850661.41
      1470511.17       850547.52      1470579.49       850475.06
#Sta/Elev= 30
  4783.2  888.38  4804.4  883.92  4821.4  880.89  4828.4  878.98  4834.7  874.72
  4845.8  867.74  4856.9  863.04  4873.7  863.26  4890.3  859.51  4907.9  851.59
  4922.0  849.27  4953.7  845.67  4966.7  843.51  4968.2  843.06  4969.6  841.36
  4975.0  841.36  4976.0  839.36  5024.0  839.36  5025.0  841.36  5033.7  841.42
  5036.4  841.70  5046.2  844.00  5062.0  846.50  5078.2  848.59  5085.2  851.92
  5091.7  855.57  5095.5  858.03  5108.2  867.64  5159.8  904.59  5164.9  906.70
#Mann=3,-1,0
  4783.2    0.07       0  4975.0    0.04       0  5025.0    0.12       0
Bank Sta=4975,5025
XS Rating Curve= 0
Exp/Cntr=0.3,0.1

Type RM Length L Ch R = 1,44619,585,585,585
BEGIN DESCRIPTION:
North Hunting Creek 83.0
END DESCRIPTION:
XS GIS Cut Line= 4
      1470612.60       851235.01      1470695.46       851150.08
      1470933.58       850882.97      1471022.64       850787.70
#Sta/Elev= 30
  4642.9  895.89  4655.2  892.59  4670.6  887.68  4696.8  876.40  4733.9  862.68
  4743.3  857.67  4755.3  853.84  4775.4  852.85  4789.5  852.97  4827.8  851.16
  4870.0  851.64  4896.4  851.79  4929.8  850.90  4946.4  847.29  4963.1  845.08
  4975.0  839.05  4976.0  837.05  5024.0  837.05  5025.0  839.05  5119.3  839.36
  5133.6  842.02  5149.3  848.83  5162.4  857.02  5175.8  861.69  5179.1  862.25
  5194.2  867.77  5212.5  883.14  5231.7  887.51  5241.8  890.72  5249.8  892.10
#Mann=4,-1,0
  4642.9    0.07       0  4870.0    0.12       0  4975.0    0.04       0
  5025.0    0.12       0
Bank Sta=4975,5025
XS Rating Curve= 0
Exp/Cntr=0.3,0.1

Type RM Length L Ch R = 1,44034,492,492,492
BEGIN DESCRIPTION:
North Hunting Creek 82.0
END DESCRIPTION:
XS GIS Cut Line= 4
      1471310.44       851473.12      1471329.08       851361.29
      1471358.07       851210.13      1471382.92       851065.14
#Sta/Elev= 30
  4800.5  882.79  4838.8  870.09  4843.7  868.04  4852.8  865.66  4864.6  857.09
  4876.7  854.14  4891.3  851.86  4905.9  850.59  4920.3  848.83  4937.3  849.63
  4951.3  845.93  4966.5  841.53  4972.8  838.23  4975.0  835.10  4976.0  833.10
  5024.0  833.10  5025.0  835.10  5029.1  838.48  5069.9  845.96  5081.0  850.39
  5082.7  850.50  5090.9  852.97  5108.8  864.74  5116.4  870.29  5126.8  872.56
  5152.3  876.57  5154.6  876.70  5164.9  878.58  5190.8  881.09  5214.9  882.66
#Mann=3,-1,0
  4800.5    0.12       0  4975.0    0.04       0  5025.0    0.12       0
Bank Sta=4975,5025
XS Rating Curve= 0
Exp/Cntr=0.3,0.1

Type RM Length L Ch R = 1,43542,296,296,296
BEGIN DESCRIPTION:
North Hunting Creek 81.0
END DESCRIPTION:
XS GIS Cut Line= 4
      1471888.16       851208.07      1471805.33       851145.94
      1471683.16       851065.18      1471587.87       851000.97
#Sta/Elev= 30
  4874.1  915.24  4886.2  908.50  4901.5  891.88  4932.2  871.03  4937.7  867.90
  4941.7  863.97  4944.5  858.37  4968.2  833.56  4975.0  833.56  4976.0  831.56
  5024.0  831.56  5025.0  833.56  5038.1  833.58  5039.5  835.74  5048.3  839.43
  5056.9  845.79  5059.6  845.93  5067.2  847.39  5074.6  847.87  5098.9  848.59
  5102.8  848.48  5108.2  848.91  5111.9  848.95  5129.1  850.57  5135.5  851.51
  5143.7  852.09  5163.7  857.93  5183.5  860.79  5192.4  861.79  5239.0  868.69
#Mann=3,-1,0
  4874.1    0.12       0  4975.0    0.04       0  5025.0    0.12       0
Bank Sta=4975,5025
XS Rating Curve= 0
Exp/Cntr=0.3,0.1

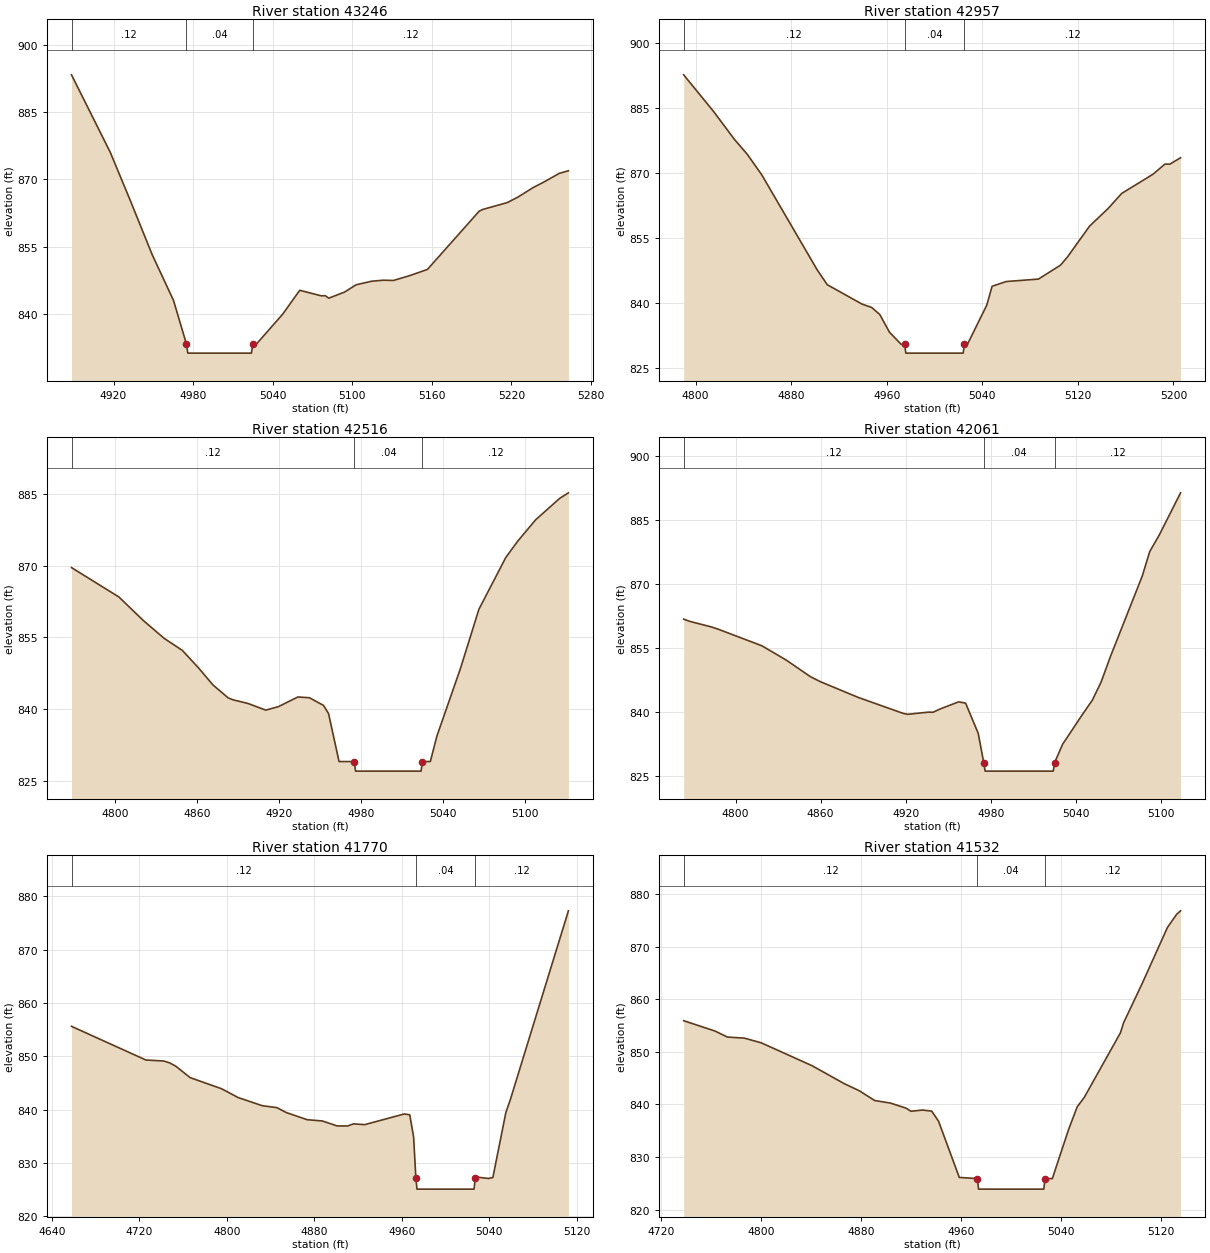
Type RM Length L Ch R = 1,43246,289,289,289
BEGIN DESCRIPTION:
North Little Hunting Creek 80.5
END DESCRIPTION:
XS GIS Cut Line= 4
      1472042.60       850950.07      1471955.99       850892.34
      1471827.53       850824.49      1471725.06       850752.33
#Sta/Elev= 30
  4888.3  893.36  4917.6  876.01  4932.7  865.25  4949.1  853.23  4965.2  843.00
  4975.0  833.22  4976.0  831.22  5024.0  831.22  5025.0  833.22  5027.7  833.23
  5047.5  839.90  5060.4  845.25  5076.8  844.00  5079.6  844.05  5082.3  843.49
  5094.1  844.84  5102.9  846.48  5114.5  847.27  5123.3  847.50  5131.1  847.45
  5143.7  848.56  5156.7  849.91  5195.7  862.91  5198.5  863.31  5216.8  864.82
  5225.0  866.07  5236.4  868.18  5244.7  869.45  5256.1  871.36  5263.0  871.94
#Mann=3,-1,0
  4888.3    0.12       0  4975.0    0.04       0  5025.0    0.12       0
Bank Sta=4975,5025
XS Rating Curve= 0
Exp/Cntr=0.3,0.1

Type RM Length L Ch R = 1,42957,441,441,441
BEGIN DESCRIPTION:
North Hunting Creek 80.0
END DESCRIPTION:
XS GIS Cut Line= 4
      1472167.68       850744.22      1472095.22       850648.98
      1471937.85       850568.23      1471832.28       850512.34
#Sta/Elev= 30
  4790.0  892.65  4815.1  884.17  4832.5  877.75  4843.2  874.32  4855.3  869.60
  4901.7  847.67  4910.2  844.21  4939.2  839.74  4947.4  838.95  4954.2  837.32
  4962.3  833.24  4972.1  830.44  4975.0  830.41  4976.0  828.41  5024.0  828.41
  5025.0  830.41  5027.5  830.41  5043.8  839.51  5048.2  843.84  5060.1  844.94
  5087.0  845.50  5105.5  848.72  5111.4  850.64  5129.8  857.72  5145.3  861.78
  5156.7  865.27  5182.9  869.70  5192.8  872.03  5197.1  872.04  5206.0  873.51
#Mann=3,-1,0
  4790.0    0.12       0  4975.0    0.04       0  5025.0    0.12       0
Bank Sta=4975,5025
XS Rating Curve= 0
Exp/Cntr=0.3,0.1

Type RM Length L Ch R = 1,42516,455,455,455
BEGIN DESCRIPTION:
North Hunting Creek 79.0
END DESCRIPTION:
XS GIS Cut Line= 4
      1472349.92       850427.45      1472285.72       850325.96
      1472217.38       850201.72      1472134.54       850141.67
#Sta/Elev= 30
  4767.8  869.59  4802.5  863.46  4820.5  858.52  4835.8  854.79  4849.0  852.30
  4860.7  848.70  4871.5  845.07  4882.6  842.38  4885.8  842.00  4897.2  841.20
  4910.2  839.81  4919.6  840.56  4933.7  842.56  4942.2  842.40  4952.5  840.80
  4956.2  839.09  4963.9  829.07  4975.0  829.07  4976.0  827.07  5024.0  827.07
  5025.0  829.07  5030.8  829.08  5035.6  834.38  5052.8  848.45  5066.4  860.88
  5086.1  871.70  5094.9  875.13  5108.0  879.58  5125.6  884.05  5132.0  885.21
#Mann=3,-1,0
  4767.8    0.12       0  4975.0    0.04       0  5025.0    0.12       0
#XS Ineff=2,0
    0.00 4933.70  842.56               0
Permanent Ineff=
       F       F
Bank Sta=4975,5025
XS Rating Curve= 0
Exp/Cntr=0.3,0.1

Type RM Length L Ch R = 1,42061,291,291,291
BEGIN DESCRIPTION:
North Hunting Creek 78.0
END DESCRIPTION:
XS GIS Cut Line= 4
      1472538.34       850450.20      1472637.73       850332.18
      1472646.01       850226.57      1472631.52       850137.56
#Sta/Elev= 30
  4763.4  861.75  4767.7  861.23  4782.7  859.95  4787.4  859.44  4818.5  855.52
  4835.6  852.19  4852.7  848.29  4859.6  847.13  4886.4  843.42  4918.0  839.69
  4921.2  839.45  4935.9  839.96  4939.2  839.93  4944.3  840.71  4957.3  842.37
  4962.2  842.08  4971.1  835.01  4975.0  828.14  4976.0  826.14  5024.0  826.14
  5025.0  828.14  5030.6  832.42  5044.5  839.37  5051.6  842.78  5057.7  846.96
  5064.3  852.96  5086.8  871.86  5092.0  877.55  5098.7  881.42  5113.8  891.35
#Mann=3,-1,0
  4763.4    0.12       0  4975.0    0.04       0  5025.0    0.12       0
Bank Sta=4975,5025
XS Rating Curve= 0
Exp/Cntr=0.3,0.1

Type RM Length L Ch R = 1,41770,238,238,238
BEGIN DESCRIPTION:
North Little Hunting Creek 77.5
END DESCRIPTION:
XS GIS Cut Line= 4
      1473046.44       850564.01      1472932.07       850411.53
      1472935.34       850230.68      1472940.79       850147.84
#Sta/Elev= 30
  4657.9  855.61  4726.0  849.29  4742.2  849.11  4747.6  848.76  4753.4  848.12
  4766.4  845.99  4795.2  843.90  4810.2  842.26  4832.4  840.72  4845.8  840.36
  4854.2  839.45  4873.5  838.09  4887.3  837.86  4900.8  836.93  4910.5  836.92
  4915.8  837.31  4926.1  837.17  4962.3  839.17  4967.3  839.01  4970.8  834.87
  4972.9  827.07  4973.9  825.07  5026.1  825.07  5027.1  827.07  5029.4  827.31
  5039.3  827.07  5043.3  827.25  5055.2  839.45  5059.3  841.87  5112.4  877.28
#Mann=3,-1,0
  4657.9    0.12       0  4972.9    0.04       0  5027.1    0.12       0
Bank Sta=4972.9,5027.1
XS Rating Curve= 0
Exp/Cntr=0.3,0.1

Type RM Length L Ch R = 1,41532,222,222,222
BEGIN DESCRIPTION:
North Hunting Creek 77.0
END DESCRIPTION:
XS GIS Cut Line= 4
      1473097.42       850557.84      1473147.10       850404.65
      1473171.95       850278.34      1473174.02       850170.63
#Sta/Elev= 30
  4738.0  855.92  4763.1  853.95  4773.0  852.81  4786.5  852.61  4800.1  851.71
  4840.5  847.39  4866.6  843.94  4878.3  842.63  4890.8  840.75  4903.5  840.26
  4915.9  839.30  4919.8  838.71  4929.1  838.94  4936.4  838.74  4941.9  836.82
  4958.5  826.13  4972.9  825.91  4973.9  823.91  5026.1  823.91  5027.1  825.91
  5032.9  825.91  5045.9  835.22  5052.8  839.55  5058.5  841.36  5087.4  853.62
  5089.9  855.51  5104.7  862.94  5125.0  873.64  5132.4  876.15  5135.5  876.80
#Mann=3,-1,0
  4738.0    0.12       0  4972.9    0.04       0  5027.1    0.12       0
Bank Sta=4972.9,5027.1
XS Rating Curve= 0
Exp/Cntr=0.5,0.3

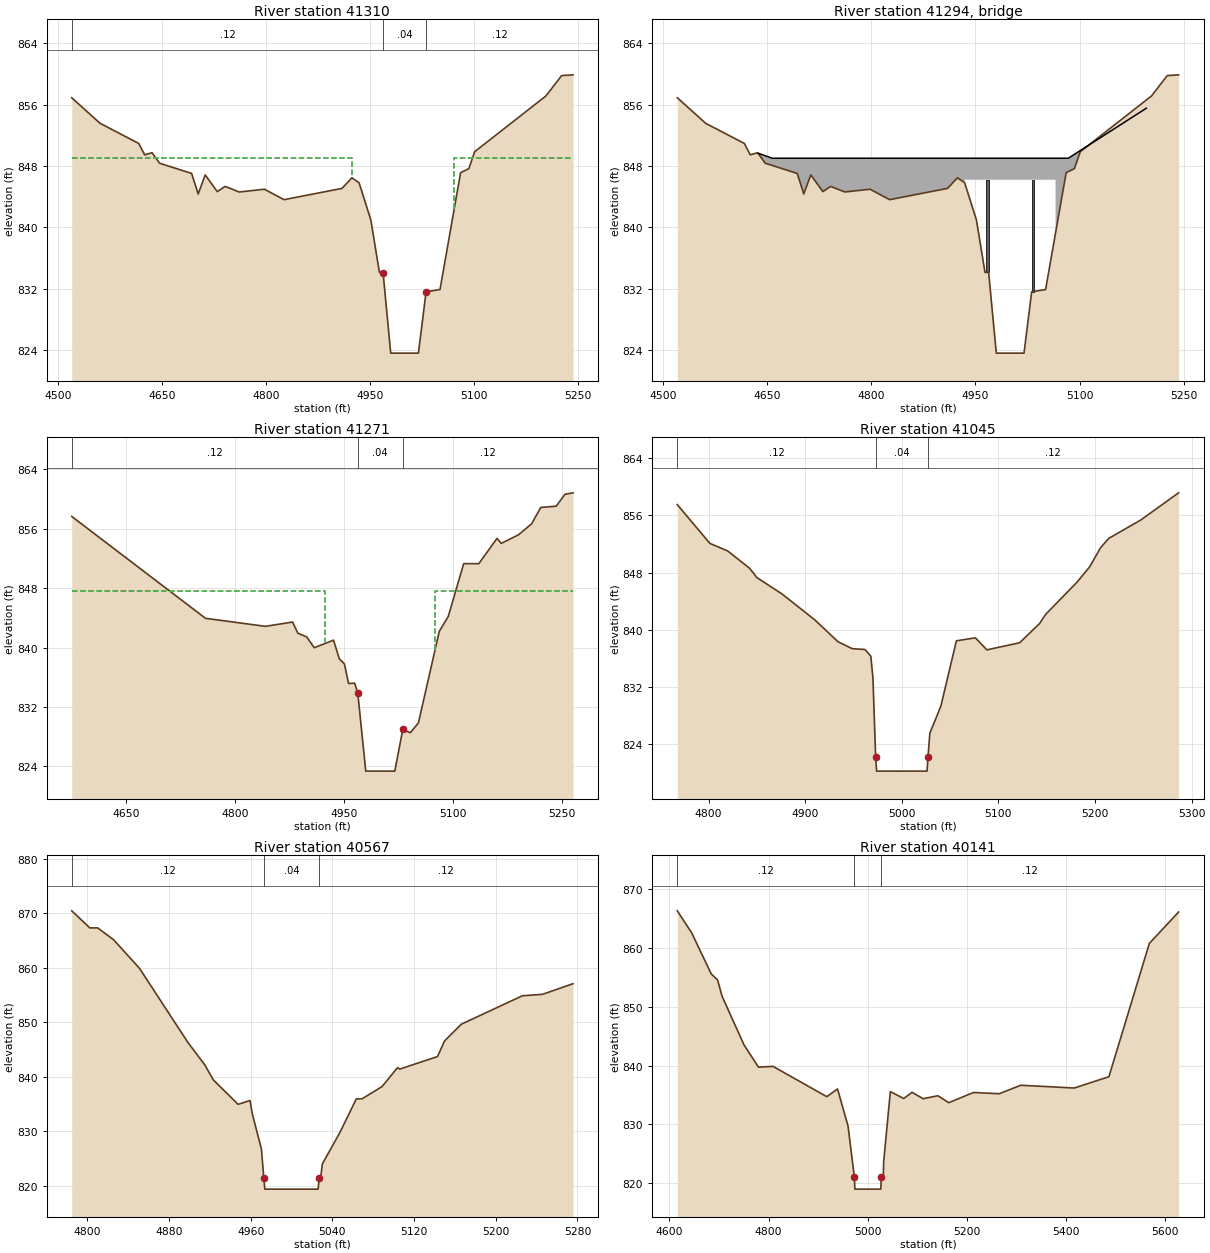
Type RM Length L Ch R = 1,41310,39,39,39
BEGIN DESCRIPTION:
Hamptonville Rd - US
END DESCRIPTION:
XS GIS Cut Line= 5
      1473410.05       850752.47      1473331.39       850603.43
      1473325.18       850522.67      1473321.04       850491.62
      1473463.93       850073.30
#Sta/Elev= 30
  4520.0  856.88  4560.9  853.55  4616.6  850.93  4625.2  849.44  4635.8  849.72
  4646.7  848.35  4692.9  847.02  4702.4  844.34  4712.5  846.82  4729.9  844.65
  4741.2  845.33  4761.6  844.60  4797.9  844.96  4826.2  843.60  4909.8  845.07
  4924.0  846.45  4934.4  845.80  4951.4  840.94  4963.7  834.13  4969.0  834.10
  4980.0  823.60  5020.0  823.60  5031.0  831.59  5051.1  831.89  5080.8  847.12
  5092.7  847.64  5101.1  849.85  5203.9  857.12  5226.5  859.77  5242.9  859.87
#Mann=3,-1,0
  4520.0    0.12       0  4969.0    0.04       0  5031.0    0.12       0
#XS Ineff=2,0
    0.00 4924.50  849.00 5071.50    0.00  849.00
Permanent Ineff=
       F       F
Bank Sta=4969,5031
XS Rating Curve= 0
Exp/Cntr=0.5,0.3

Type RM Length L Ch R =3,41294,,,
BEGIN DESCRIPTION:
Hamptonville Rd - TOR
Structure ID: LDS_NLHC_03
Approximate Survey Structure
END DESCRIPTION:
Bridge Culvert--1,0,-1,-1,0
Deck Dist Width WeirC Skew NumUp NumDn MinLoCord MaxHiCord MaxSubmerge Is_Ogee
5.5,21,3,,8,8,,,,0,1,1,,,
  4636.8  4657.0  4934.5  4934.5  5065.5  5065.5  5083.9  5196.4
  849.64  849.00  849.00  849.00  849.00  849.00  849.00  855.52
  803.60  803.60  803.60  846.20  846.20  803.60  803.60  803.60
  4636.8  4657.0  4934.5  4934.5  5065.5  5065.5  5083.9  5196.4
  849.64  849.00  849.00  849.00  849.00  849.00  849.00  855.52
  803.60  803.60  803.60  846.20  846.20  803.60  803.60  803.60
Pier Skew, UpSta & Num, DnSta & Num=,4967.3,2,4967.3,2,0,0,0,0,0
       3       3
  834.11  846.20
       3       3
  834.38  846.20
Pier Skew, UpSta & Num, DnSta & Num=,5032.8,2,5032.8,2,0,0,0,0,0
       3       3
  830.42  846.20
       3       3
  825.92  846.20
BR Coef=1,1,0,1.25,0,,,0.8,0,2,0,
WSPro=,,,, 1 ,,,, 0 ,,,, 0 ,,,,-1 ,-1 ,-1 , 0 , 0 , 0 , 0 , 0
BC Design=,,0,,0,,,,,,

Type RM Length L Ch R = 1,41271,226,226,226
BEGIN DESCRIPTION:
Hamptonville Rd - DS
END DESCRIPTION:
XS GIS Cut Line= 4
      1473434.93       850727.68      1473360.38       850562.02
      1473356.24       850512.32      1473497.05       850075.39
#Sta/Elev= 30
  4574.9  857.67  4759.2  843.94  4841.8  842.86  4879.2  843.44  4886.4  841.94
  4898.7  841.43  4909.0  839.98  4935.6  841.00  4943.6  838.47  4950.6  837.79
  4956.3  835.16  4964.7  835.20  4969.0  833.85  4980.0  823.35  5020.0  823.35
  5031.0  828.98  5041.3  828.52  5052.5  829.84  5081.2  842.16  5093.7  844.21
  5114.9  851.31  5135.7  851.30  5160.8  854.71  5166.7  854.04  5190.4  855.19
  5208.5  856.68  5221.1  858.88  5242.4  859.05  5254.3  860.65  5265.5  860.85
#Mann=3,-1,0
  4574.9    0.12       0  4969.0    0.04       0  5031.0    0.12       0
#XS Ineff=2,0
    0.00 4924.50  847.65 5075.50    0.00  847.65
Permanent Ineff=
       F       F
Bank Sta=4969,5031
XS Rating Curve= 0
Exp/Cntr=0.5,0.3

Type RM Length L Ch R = 1,41045,478,478,478
BEGIN DESCRIPTION:
North Hunting Creek 76.0
END DESCRIPTION:
XS GIS Cut Line= 4
      1473526.05       850671.73      1473577.80       850537.17
      1473615.07       850317.68      1473631.64       850166.48
#Sta/Elev= 30
  4767.6  857.48  4801.3  852.07  4819.8  851.01  4842.5  848.59  4849.9  847.30
  4875.4  845.07  4909.7  841.42  4933.9  838.35  4948.5  837.38  4961.9  837.26
  4967.9  836.33  4970.1  833.29  4972.9  822.28  4973.9  820.28  5026.1  820.28
  5027.1  822.28  5029.0  825.56  5040.4  829.35  5056.5  838.47  5076.2  838.89
  5088.0  837.21  5122.0  838.20  5142.7  840.90  5148.6  842.12  5181.2  846.64
  5194.3  848.77  5205.7  851.46  5214.2  852.77  5247.4  855.34  5286.5  859.13
#Mann=3,-1,0
  4767.6    0.12       0  4972.9    0.04       0  5027.1    0.12       0
Bank Sta=4972.9,5027.1
XS Rating Curve= 0
Exp/Cntr=0.3,0.1

Type RM Length L Ch R = 1,40567,426,426,426
BEGIN DESCRIPTION:
North Hunting Creek 75.0
END DESCRIPTION:
XS GIS Cut Line= 4
      1474141.02       850410.87      1474056.12       850301.12
      1473923.60       850176.88      1473813.84       850046.41
#Sta/Elev= 30
  4784.8  870.46  4802.5  867.33  4810.2  867.33  4825.8  865.16  4851.2  859.90
  4898.6  846.30  4915.0  842.22  4923.6  839.41  4947.7  834.95  4959.4  835.65
  4961.7  833.17  4970.6  826.72  4972.9  821.39  4973.9  819.39  5026.1  819.39
  5027.1  821.39  5028.5  821.42  5030.3  824.03  5047.6  829.85  5063.5  835.95
  5069.2  835.97  5088.7  838.21  5103.8  841.67  5106.1  841.42  5143.0  843.72
  5150.0  846.60  5166.4  849.66  5226.1  854.87  5245.9  855.14  5275.7  857.09
#Mann=3,-1,0
  4784.8    0.12       0  4972.9    0.04       0  5027.1    0.12       0
Bank Sta=4972.9,5027.1
XS Rating Curve= 0
Exp/Cntr=0.3,0.1

Type RM Length L Ch R = 1,40141,663,663,663
BEGIN DESCRIPTION:
North Hunting Creek 74.0
END DESCRIPTION:
XS GIS Cut Line= 4
      1474447.47       850344.59      1474482.67       850176.88
      1474047.84       849619.87      1473942.27       849539.15
#Sta/Elev= 30
  4615.8  866.28  4644.9  862.52  4684.1  855.58  4697.0  854.55  4706.1  851.77
  4750.4  843.50  4779.4  839.74  4808.9  839.86  4917.3  834.72  4938.9  836.03
  4960.1  829.73  4972.9  821.02  4973.9  819.02  5026.1  819.02  5027.1  821.02
  5031.2  821.02  5031.9  823.64  5045.4  835.58  5072.4  834.41  5089.2  835.46
  5111.6  834.37  5141.2  834.88  5163.3  833.70  5213.1  835.43  5264.9  835.22
  5308.4  836.66  5416.3  836.19  5486.2  838.11  5567.7  860.74  5626.7  866.08
#Mann=3,-1,0
  4615.8    0.12       0  4972.9    0.04       0  5027.1    0.12       0
Bank Sta=4972.9,5027.1
XS Rating Curve= 0
Exp/Cntr=0.3,0.1

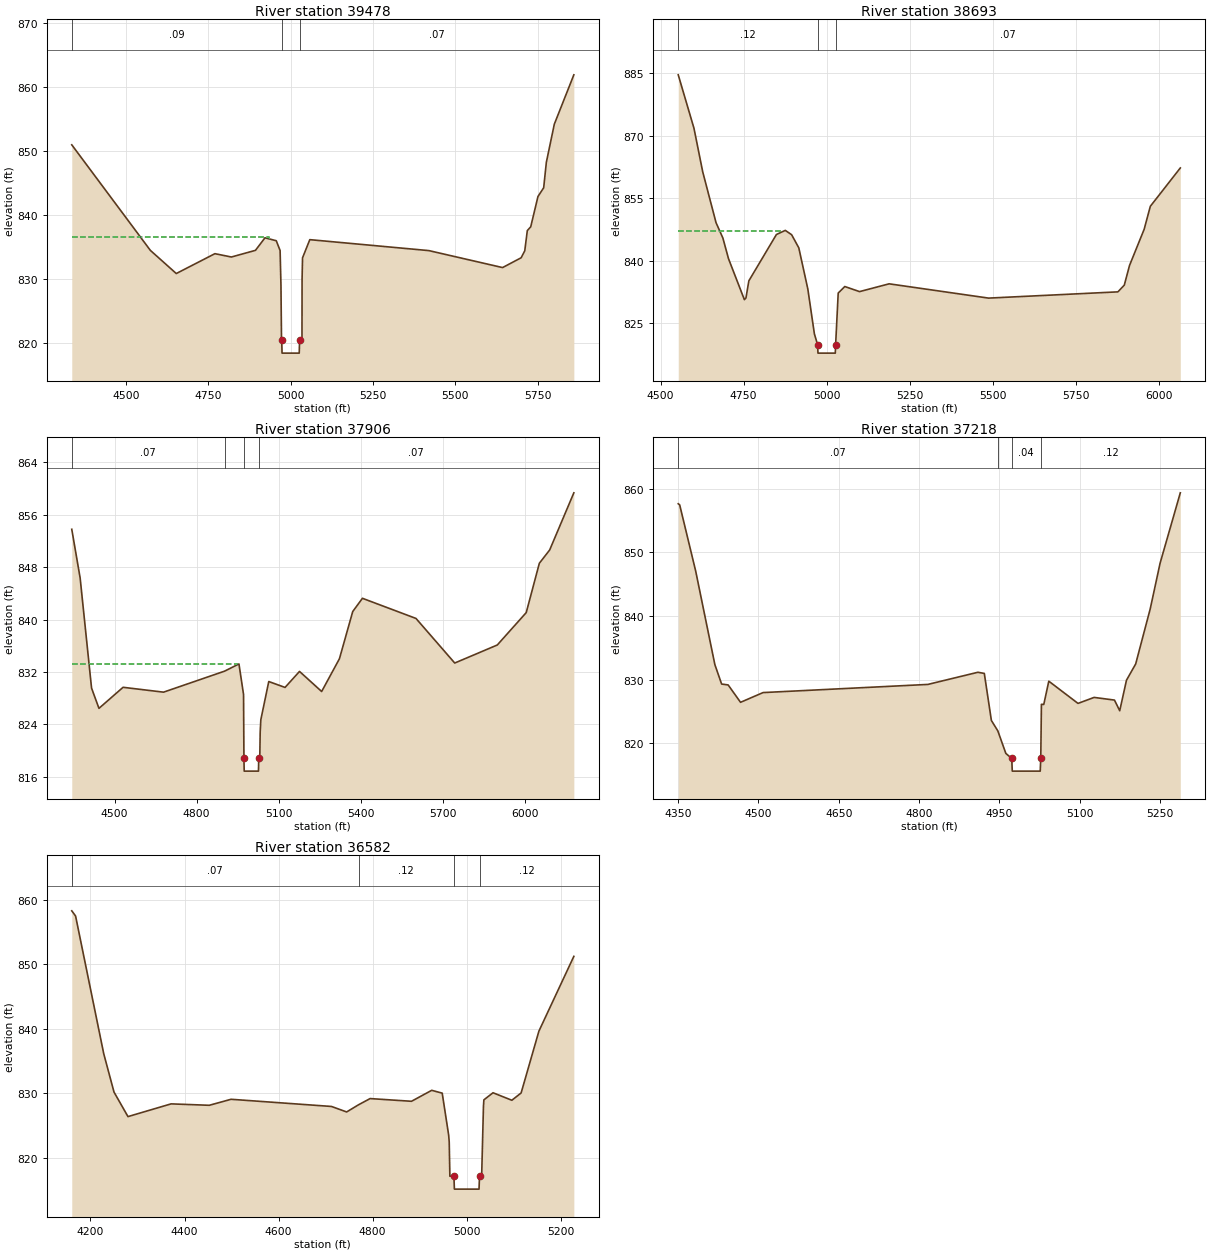
Type RM Length L Ch R = 1,39478,785,785,785
BEGIN DESCRIPTION:
North Hunting Creek 73.0
END DESCRIPTION:
XS GIS Cut Line= 4
      1475267.76       850075.30      1475203.19       849780.13
      1474259.20       849325.05      1474091.28       849371.41
#Sta/Elev= 30
  4335.5  850.99  4574.2  834.50  4652.8  830.89  4770.1  833.99  4820.1  833.47
  4893.2  834.51  4922.1  836.47  4956.4  836.01  4968.0  834.48  4970.6  829.06
  4972.3  820.47  4972.9  820.46  4973.9  818.46  5026.1  818.46  5027.1  820.46
  5034.4  820.47  5034.7  829.96  5036.1  833.34  5058.2  836.18  5419.6  834.47
  5643.4  831.82  5699.8  833.35  5710.8  834.44  5718.5  837.59  5728.9  838.19
  5750.9  842.92  5768.2  844.28  5776.3  848.25  5800.5  854.21  5859.8  861.92
#Mann=3,-1,0
  4335.5    0.09       0  4972.9    0.04       0  5027.1    0.07       0
#XS Ineff=2,0
    0.00 4933.90  836.64 5058.20    0.00  836.18
Permanent Ineff=
       F       F
Bank Sta=4972.9,5027.1
XS Rating Curve= 0
Exp/Cntr=0.3,0.1

Type RM Length L Ch R = 1,38693,787,787,787
BEGIN DESCRIPTION:
North Hunting Creek 72.0
END DESCRIPTION:
XS GIS Cut Line= 4
      1475464.53       848817.71      1475190.89       848983.74
      1474185.41       849217.43      1474064.39       849321.71
#Sta/Elev= 30
  4553.1  884.60  4600.5  871.77  4626.9  861.29  4667.0  849.09  4687.5  845.43
  4704.5  840.46  4752.3  830.62  4757.0  831.01  4765.8  835.14  4848.8  846.26
  4875.5  847.25  4894.6  846.21  4916.2  843.06  4943.4  833.18  4963.2  822.39
  4972.9  819.78  4973.9  817.78  5026.1  817.78  5027.1  819.78  5034.9  832.20
  5054.7  833.77  5099.2  832.55  5188.3  834.42  5487.7  830.99  5877.3  832.49
  5896.5  834.11  5912.3  838.84  5956.3  847.51  5974.9  853.03  6065.2  862.24
#Mann=3,-1,0
  4553.1    0.12       0  4972.9    0.04       0  5027.1    0.07       0
#XS Ineff=2,0
    0.00 4865.60  847.06 5054.70    0.00  833.77
Permanent Ineff=
       F       F
Bank Sta=4972.9,5027.1
XS Rating Curve= 0
Exp/Cntr=0.3,0.1

Type RM Length L Ch R = 1,37906,688,688,688
BEGIN DESCRIPTION:
North Hunting Creek 71.0
END DESCRIPTION:
XS GIS Cut Line= 5
      1475169.37       847929.06      1475095.57       847981.33
      1474420.55       848559.70      1474431.40       848814.62
      1474016.26       849251.28
#Sta/Elev= 30
  4343.0  853.76  4373.6  846.35  4415.4  829.55  4442.5  826.46  4530.7  829.67
  4678.8  828.93  4902.0  832.13  4954.7  833.23  4971.5  828.57  4972.9  818.89
  4973.9  816.89  5026.1  816.89  5027.1  818.89  5030.9  818.89  5032.4  822.85
  5034.8  824.74  5063.8  830.55  5123.3  829.65  5176.3  832.09  5257.3  829.03
  5322.3  834.02  5371.0  841.22  5406.5  843.24  5602.4  840.17  5744.2  833.37
  5899.9  836.12  6005.8  841.06  6053.8  848.58  6091.6  850.61  6180.0  859.32
#Mann=4,-1,0
  4343.0    0.07       0  4902.0    0.12       0  4972.9    0.04       0
  5027.1    0.07       0
#XS Ineff=2,0
    0.00 4951.40  833.27               0
Permanent Ineff=
       F       F
Bank Sta=4972.9,5027.1
XS Rating Curve= 0
Exp/Cntr=0.3,0.1

Type RM Length L Ch R = 1,37218,636,636,636
BEGIN DESCRIPTION:
North Hunting Creek 70.0
END DESCRIPTION:
XS GIS Cut Line= 4
      1475045.87       847700.39      1474952.71       847741.80
      1474225.91       847863.96      1474128.63       847849.47
#Sta/Elev= 30
  4350.3  857.61  4353.0  857.44  4382.9  847.03  4418.7  832.34  4431.3  829.29
  4443.5  829.15  4466.6  826.42  4508.7  827.95  4816.3  829.23  4909.7  831.14
  4921.7  830.96  4934.9  823.57  4947.0  821.92  4961.9  818.39  4972.9  817.61
  4973.9  815.61  5026.1  815.61  5027.1  817.61  5028.3  826.11  5032.7  826.08
  5042.1  829.74  5096.6  826.25  5126.7  827.19  5164.7  826.77  5174.5  825.10
  5187.1  829.89  5204.3  832.45  5231.5  841.12  5249.8  848.26  5287.6  859.33
#Mann=4,-1,0
  4350.3    0.07       0  4947.0    0.12       0  4972.9    0.04       0
  5027.1    0.12       0
Bank Sta=4972.9,5027.1
XS Rating Curve= 0
Exp/Cntr=0.3,0.1

Type RM Length L Ch R = 1,36582,582,582,582
BEGIN DESCRIPTION:
North Hunting Creek 69.0
END DESCRIPTION:
XS GIS Cut Line= 4
      1475054.18       847658.98      1474981.70       847582.36
      1474203.13       847263.48      1474082.99       847275.91
#Sta/Elev= 30
  4160.2  858.26  4168.3  857.46  4228.2  836.13  4250.0  830.20  4279.7  826.40
  4371.4  828.37  4452.6  828.15  4498.9  829.08  4712.4  827.97  4744.7  827.12
  4770.0  828.23  4794.6  829.19  4882.6  828.77  4925.6  830.47  4947.9  830.03
  4961.7  823.50  4962.8  822.45  4964.2  817.17  4972.8  817.17  4973.8  815.17
  5026.2  815.17  5027.2  817.17  5031.8  817.22  5035.6  827.96  5036.5  828.99
  5055.9  830.09  5096.0  828.93  5115.7  830.06  5153.5  839.63  5227.8  851.21
#Mann=4,-1,0
  4160.2    0.07       0  4770.0    0.12       0  4972.8    0.04       0
  5027.2    0.12       0
Bank Sta=4972.8,5027.2
XS Rating Curve= 0
Exp/Cntr=0.3,0.1