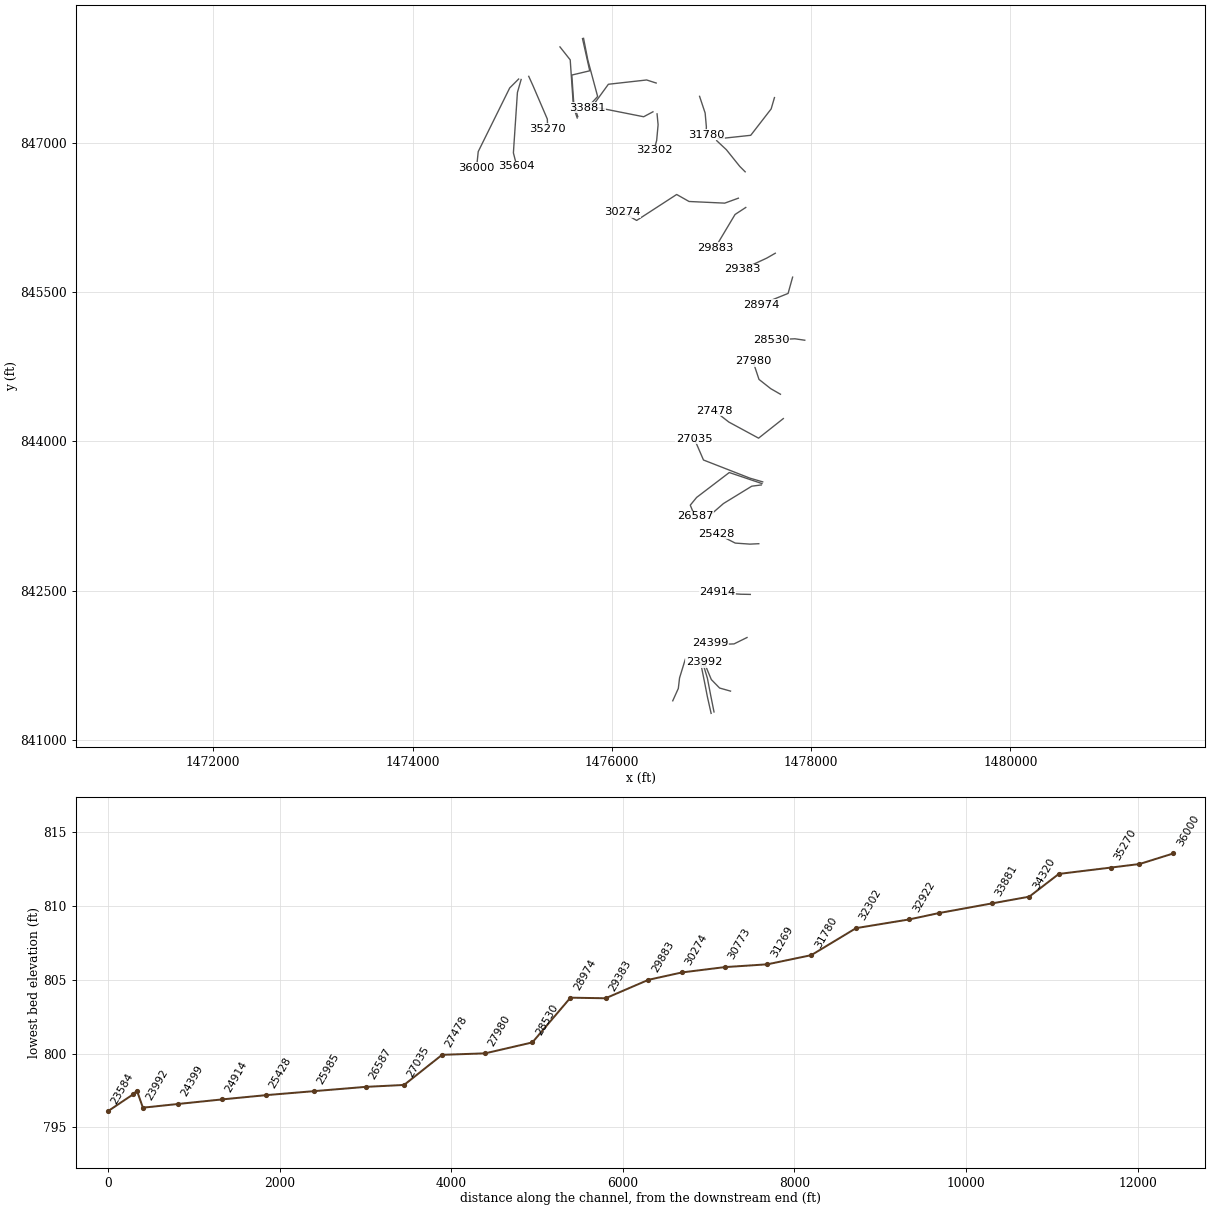
HEC-RAS study North Little Hunting Creek.prj: North Little Hunting Creek Limited Detail Study

--- North Little Hunting Creek.g01 (geometry) --- (continued)

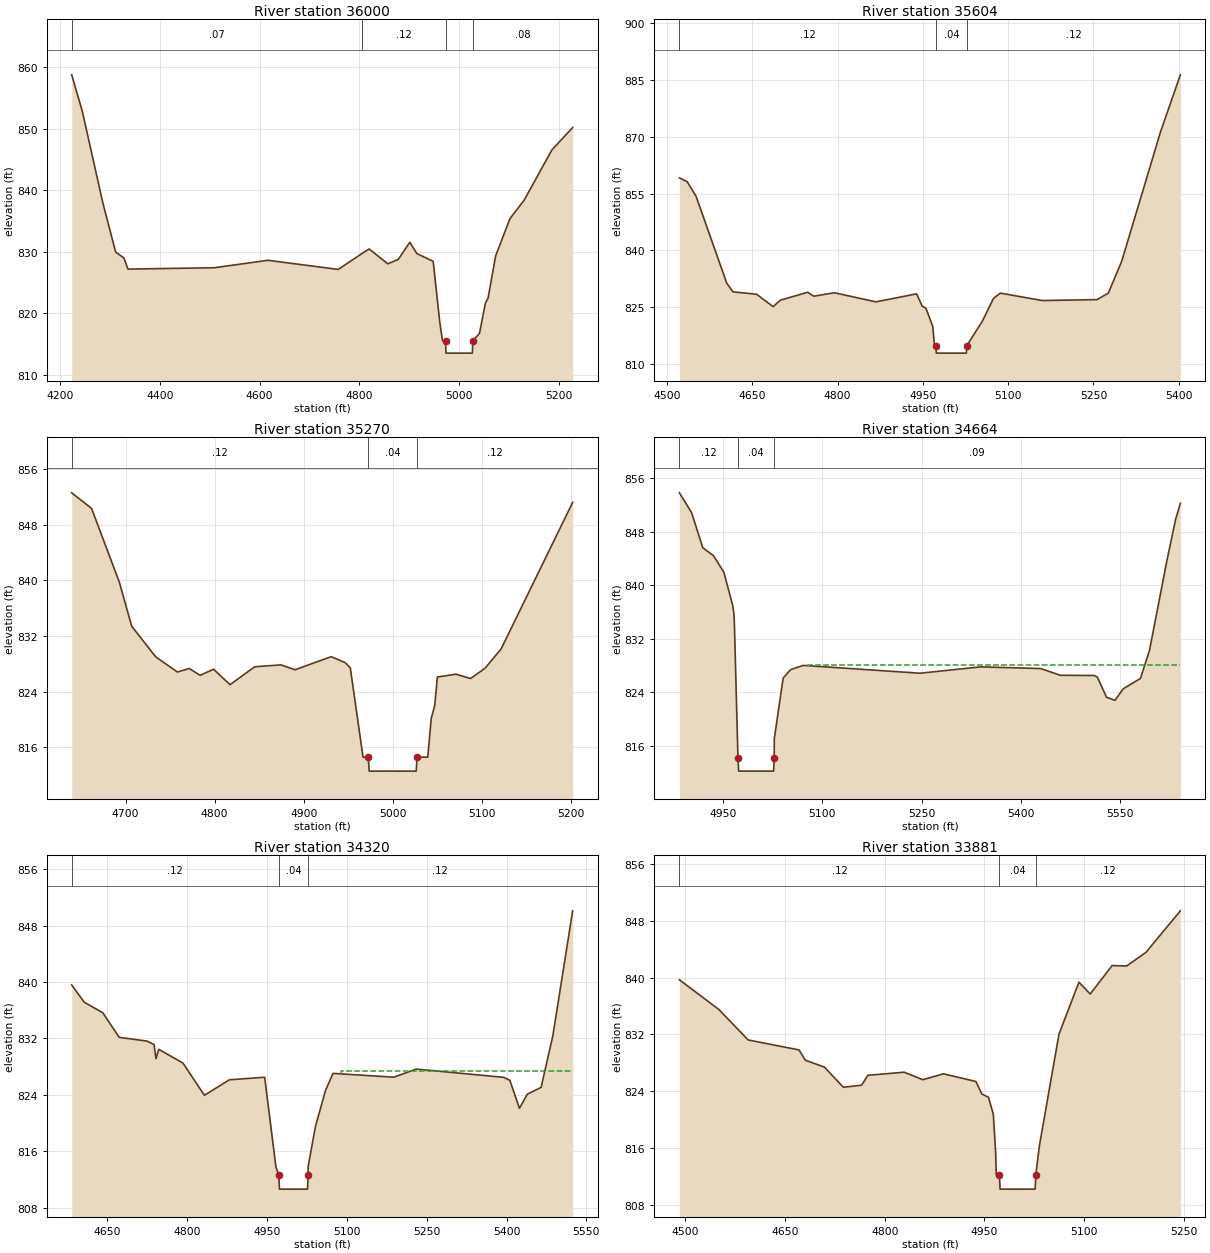
Type RM Length L Ch R = 1,36000,396,396,396
BEGIN DESCRIPTION:
North Hunting Creek 68.0
END DESCRIPTION:
XS GIS Cut Line= 4
      1475064.51       847640.32      1474975.03       847550.85
      1474658.94       846911.28      1474642.11       846747.90
#Sta/Elev= 30
  4223.3  858.77  4244.6  852.83  4285.6  838.00  4311.4  829.97  4328.0  829.01
  4336.1  827.21  4509.1  827.43  4616.6  828.64  4757.6  827.16  4805.0  829.73
  4819.6  830.48  4856.9  828.07  4878.0  828.79  4901.0  831.57  4915.3  829.72
  4947.9  828.47  4961.1  818.59  4966.6  815.56  4972.6  815.56  4973.6  813.56
  5026.4  813.56  5027.4  815.56  5040.7  816.76  5052.8  821.77  5057.9  822.47
  5073.1  829.36  5101.9  835.42  5130.1  838.39  5186.1  846.60  5227.5  850.20
#Mann=4,-1,0
  4223.3    0.07       0  4805.0    0.12       0  4972.6    0.04       0
  5027.4    0.08       0
Bank Sta=4972.6,5027.4
XS Rating Curve= 0
Exp/Cntr=0.3,0.1

Type RM Length L Ch R = 1,35604,334,334,334
BEGIN DESCRIPTION:
North Hunting Creek 67.5
END DESCRIPTION:
XS GIS Cut Line= 4
      1475089.64       847635.63      1475052.33       847505.07
      1475011.91       846898.70      1475046.11       846765.01
#Sta/Elev= 30
  4521.5  859.16  4535.2  858.15  4550.8  854.28  4604.9  831.30  4615.6  829.04
  4657.3  828.40  4686.4  825.13  4699.1  826.82  4747.2  828.93  4757.9  827.88
  4794.0  828.80  4867.4  826.39  4938.9  828.51  4948.8  825.22  4955.2  824.73
  4967.3  819.90  4970.3  814.84  4972.6  814.84  4973.6  812.84  5026.4  812.84
  5027.4  814.84  5054.8  821.35  5074.2  827.31  5086.2  828.70  5159.8  826.74
  5256.4  826.98  5276.2  828.69  5299.8  837.13  5368.1  871.32  5403.0  886.39
#Mann=3,-1,0
  4521.5    0.12       0  4972.6    0.04       0  5027.4    0.12       0
Bank Sta=4972.6,5027.4
XS Rating Curve= 0
Exp/Cntr=0.3,0.1

Type RM Length L Ch R = 1,35270,606,606,606
BEGIN DESCRIPTION:
North Hunting Creek 67.0
END DESCRIPTION:
XS GIS Cut Line= 4
      1475165.97       847667.30      1475207.40       847576.14
      1475352.34       847238.63      1475356.49       847143.37
#Sta/Elev= 30
  4639.4  852.60  4661.7  850.36  4692.8  839.80  4706.8  833.43  4733.8  829.02
  4758.1  826.85  4771.5  827.35  4783.6  826.37  4798.8  827.24  4817.3  825.03
  4845.0  827.60  4874.5  827.87  4890.3  827.17  4930.9  829.05  4946.6  828.20
  4952.4  827.44  4966.7  814.60  4972.6  814.60  4973.6  812.60  5026.4  812.60
  5027.4  814.60  5039.4  814.61  5043.3  820.17  5047.2  822.02  5050.2  826.13
  5071.2  826.53  5087.5  825.91  5103.8  827.39  5121.8  830.16  5202.2  851.22
#Mann=3,-1,0
  4639.4    0.12       0  4972.6    0.04       0  5027.4    0.12       0
Bank Sta=4972.6,5027.4
XS Rating Curve= 0
Exp/Cntr=0.3,0.1

Type RM Length L Ch R = 1,34664,344,344,344
BEGIN DESCRIPTION:
North Hunting Creek 66.0
END DESCRIPTION:
XS GIS Cut Line= 4
      1475479.28       847962.92      1475582.19       847832.90
      1475614.61       847360.21      1475652.57       847249.03
#Sta/Elev= 30
  4884.1  853.84  4902.5  850.88  4919.4  845.62  4935.5  844.44  4951.2  841.97
  4964.7  836.95  4966.5  835.70  4967.2  834.23  4972.6  814.17  4973.6  812.17
  5026.4  812.17  5027.4  814.17  5027.5  817.02  5040.9  826.10  5052.0  827.36
  5071.3  828.00  5247.7  826.83  5339.3  827.78  5430.1  827.53  5459.8  826.52
  5511.0  826.49  5515.7  826.26  5529.6  823.23  5542.4  822.77  5554.8  824.49
  5580.9  826.05  5594.6  830.27  5621.0  843.76  5634.0  849.86  5641.2  852.28
#Mann=3,-1,0
  4884.1    0.12       0  4972.6    0.04       0  5027.4    0.09       0
#XS Ineff=2,0
       0                 5078.20    0.00  827.99
Permanent Ineff=
       F       F
Bank Sta=4972.6,5027.4
XS Rating Curve= 0
Exp/Cntr=0.3,0.1

Type RM Length L Ch R = 1,34320,439,439,439
BEGIN DESCRIPTION:
North Hunting Creek 65.5
END DESCRIPTION:
XS GIS Cut Line= 5
      1475705.55       848045.96      1475778.05       847722.83
      1475598.34       847680.27      1475618.83       847382.31
      1475658.23       847262.53
#Sta/Elev= 30
  4583.6  839.59  4607.2  837.14  4642.0  835.65  4672.8  832.16  4724.9  831.63
  4738.3  831.14  4741.8  829.14  4747.1  830.46  4792.5  828.51  4832.8  823.94
  4879.6  826.14  4945.9  826.50  4967.2  813.69  4972.6  812.63  4973.6  810.63
  5026.4  810.63  5027.4  812.63  5027.6  813.86  5041.2  819.50  5060.2  824.64
  5074.2  827.05  5188.6  826.51  5230.3  827.66  5394.7  826.49  5406.2  826.07
  5424.3  822.10  5439.1  824.10  5464.9  825.06  5487.1  832.43  5524.2  850.11
#Mann=3,-1,0
  4583.6    0.12       0  4972.6    0.04       0  5027.4    0.12       0
#XS Ineff=2,0
       0                 5089.00    0.00  827.38
Permanent Ineff=
       F       F
Bank Sta=4972.6,5027.4
XS Rating Curve= 0
Exp/Cntr=0.3,0.1

Type RM Length L Ch R = 1,33881,613,613,613
BEGIN DESCRIPTION:
North Hunting Creek 65.0
END DESCRIPTION:
XS GIS Cut Line= 4
      1475716.07       848049.00      1475759.12       847830.67
      1475857.52       847464.76      1475754.05       847352.51
#Sta/Elev= 30
  4490.9  839.71  4550.3  835.52  4594.4  831.22  4671.0  829.81  4680.4  828.36
  4709.2  827.39  4737.7  824.54  4765.1  824.84  4774.6  826.23  4829.2  826.67
  4857.3  825.61  4888.3  826.44  4937.2  825.36  4946.2  823.59  4956.1  823.14
  4963.4  820.75  4966.9  815.44  4967.9  812.17  4972.6  812.17  4973.6  810.17
  5026.4  810.17  5027.4  812.17  5032.7  816.23  5062.3  832.04  5092.3  839.37
  5109.3  837.70  5142.3  841.72  5164.2  841.66  5193.1  843.57  5245.0  849.44
#Mann=3,-1,0
  4490.9    0.12       0  4972.6    0.04       0  5027.4    0.12       0
#XS Ineff=2,0
    0.00 4888.30  826.44               0
Permanent Ineff=
       F       F
Bank Sta=4972.6,5027.4
XS Rating Curve= 0
Exp/Cntr=0.3,0.1

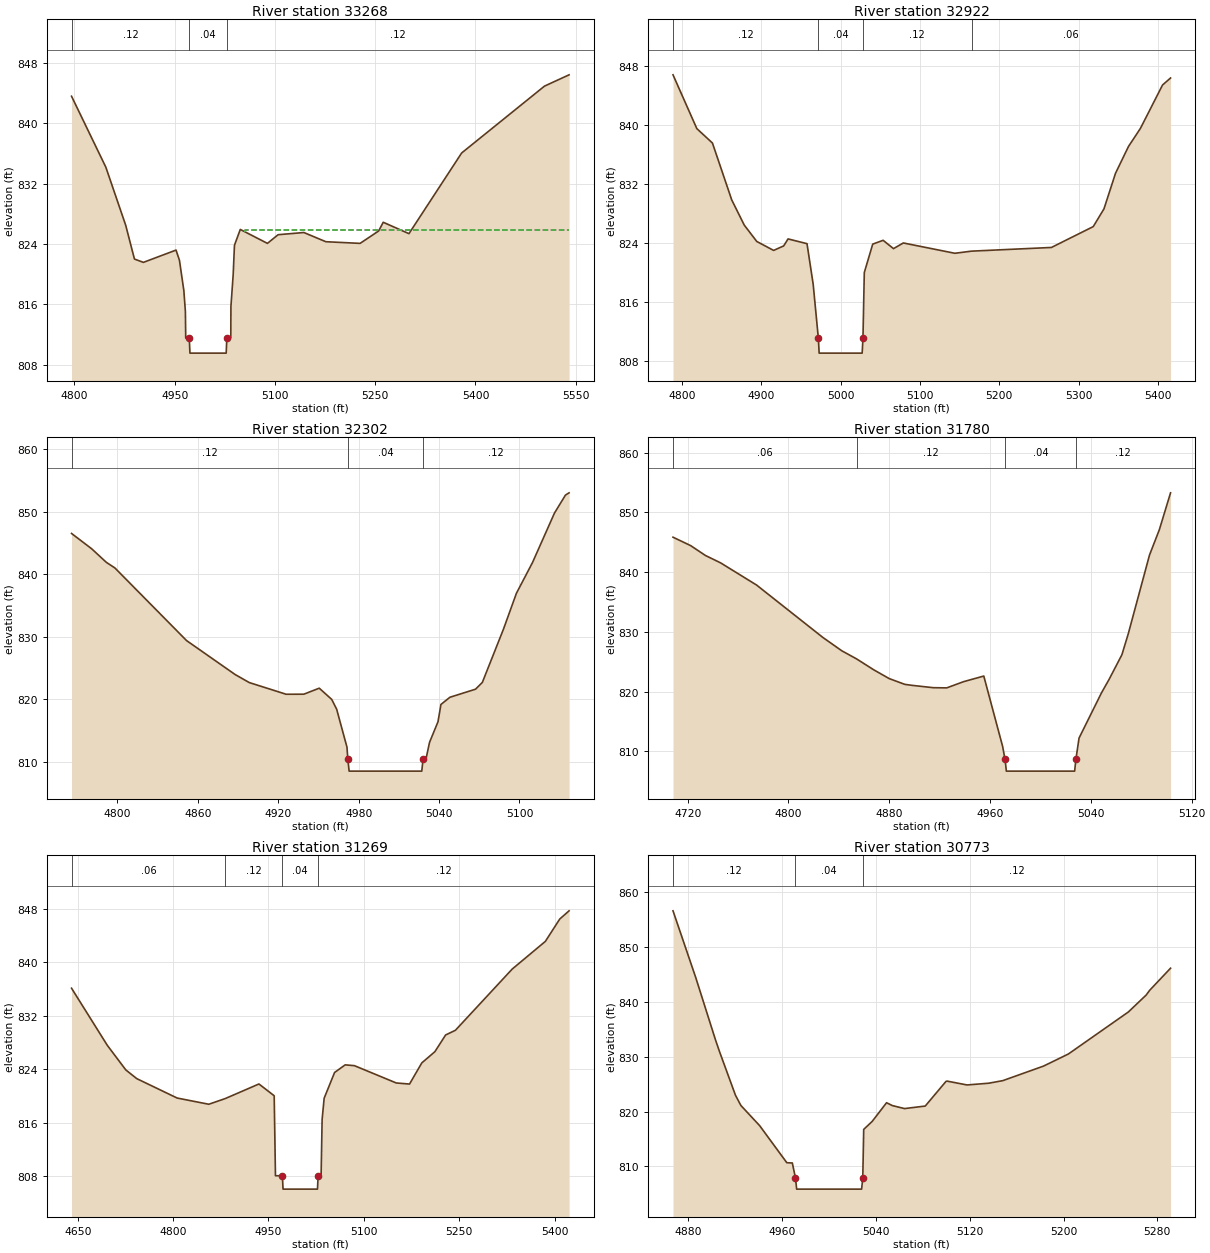
Type RM Length L Ch R = 1,33268,346,346,346
BEGIN DESCRIPTION:
North Hunting Creek 63.0
END DESCRIPTION:
XS GIS Cut Line= 4
      1476444.81       847600.05      1476349.50       847630.80
      1475965.14       847587.75      1475814.11       847379.45
#Sta/Elev= 30
  4795.8  843.60  4847.1  834.19  4876.9  826.46  4889.9  822.00  4903.3  821.56
  4952.1  823.19  4957.2  821.84  4963.8  817.81  4966.1  815.03  4966.6  811.52
  4971.9  811.52  4972.9  809.52  5027.1  809.52  5028.1  811.52  5034.0  811.55
  5034.2  815.71  5037.6  819.97  5039.5  823.83  5048.2  825.93  5088.8  824.08
  5104.8  825.23  5143.3  825.52  5176.2  824.30  5227.4  824.08  5255.2  825.73
  5262.0  826.88  5300.5  825.37  5379.3  836.07  5503.2  844.94  5540.0  846.44
#Mann=3,-1,0
  4795.8    0.12       0  4971.9    0.04       0  5028.1    0.12       0
#XS Ineff=2,0
       0                 5055.40    0.00  825.82
Permanent Ineff=
       F       F
Bank Sta=4971.9,5028.1
XS Rating Curve= 0
Exp/Cntr=0.3,0.1

Type RM Length L Ch R = 1,32922,620,620,620
BEGIN DESCRIPTION:
North Hunting Creek 62.0
END DESCRIPTION:
XS GIS Cut Line= 3
      1476412.54       847311.12      1476319.34       847261.41
      1475807.84       847362.88
#Sta/Elev= 30
  4788.7  846.83  4818.7  839.54  4838.4  837.58  4862.7  829.87  4878.5  826.45
  4894.3  824.23  4915.5  823.02  4928.2  823.63  4933.7  824.58  4957.6  823.93
  4965.4  818.40  4971.9  811.09  4972.9  809.09  5027.1  809.09  5028.1  811.09
  5029.8  820.02  5040.4  823.87  5053.5  824.39  5066.6  823.26  5079.0  824.03
  5143.9  822.63  5165.0  822.92  5265.7  823.42  5318.4  826.25  5331.9  828.66
  5346.4  833.47  5362.8  837.12  5377.8  839.56  5405.7  845.45  5415.8  846.40
#Mann=4,-1,0
  4788.7    0.12       0  4971.9    0.04       0  5028.1    0.12       0
  5165.0    0.06       0
Bank Sta=4971.9,5028.1
XS Rating Curve= 0
Exp/Cntr=0.3,0.1

Type RM Length L Ch R = 1,32302,522,522,522
BEGIN DESCRIPTION:
North Hunting Creek 61.0
END DESCRIPTION:
XS GIS Cut Line= 4
      1476453.93       847290.41      1476464.28       847180.65
      1476449.79       847023.28      1476422.88       846923.94
#Sta/Elev= 30
  4765.8  846.53  4780.8  844.08  4791.7  841.92  4798.2  841.00  4851.6  829.39
  4887.9  823.95  4898.4  822.67  4925.9  820.80  4939.1  820.81  4950.6  821.77
  4959.9  819.98  4963.6  818.41  4971.3  812.33  4971.9  810.50  4972.9  808.50
  5027.1  808.50  5028.1  810.50  5030.3  810.50  5032.9  813.11  5039.2  816.40
  5041.4  819.17  5048.1  820.32  5067.2  821.61  5072.3  822.70  5088.0  831.19
  5097.7  836.95  5109.7  841.87  5126.1  849.79  5134.3  852.67  5137.0  853.03
#Mann=3,-1,0
  4765.8    0.12       0  4971.9    0.04       0  5028.1    0.12       0
Bank Sta=4971.9,5028.1
XS Rating Curve= 0
Exp/Cntr=0.3,0.1

Type RM Length L Ch R = 1,31780,511,511,511
BEGIN DESCRIPTION:
North Hunting Creek 60.0
END DESCRIPTION:
XS GIS Cut Line= 4
      1476880.50       847466.36      1476936.39       847298.68
      1476948.81       847159.94      1476944.67       847081.29
#Sta/Elev= 30
  4708.4  845.84  4722.4  844.43  4734.1  842.78  4746.1  841.55  4774.7  837.83
  4827.4  829.04  4842.4  826.81  4854.0  825.47  4867.8  823.62  4879.9  822.17
  4892.3  821.20  4898.2  821.03  4915.0  820.64  4925.6  820.61  4939.0  821.65
  4955.0  822.59  4970.0  810.77  4971.8  808.67  4971.9  808.67  4972.9  806.67
  5027.1  806.67  5028.1  808.67  5030.6  812.21  5048.4  819.78  5054.4  822.02
  5064.6  826.16  5069.7  829.71  5086.5  842.85  5094.3  847.09  5103.2  853.27
#Mann=4,-1,0
  4708.4    0.06       0  4854.0    0.12       0  4971.9    0.04       0
  5028.1    0.12       0
Bank Sta=4971.9,5028.1
XS Rating Curve= 0
Exp/Cntr=0.3,0.1

Type RM Length L Ch R = 1,31269,496,496,496
BEGIN DESCRIPTION:
North Hunting Creek 59.0
END DESCRIPTION:
XS GIS Cut Line= 4
      1477632.12       847453.97      1477599.00       847340.09
      1477394.00       847075.05      1477066.86       847039.85
#Sta/Elev= 30
  4640.2  836.09  4696.4  827.56  4725.6  823.87  4742.8  822.57  4806.3  819.67
  4856.1  818.74  4882.0  819.59  4935.0  821.77  4959.0  820.01  4961.0  808.05
  4971.9  808.05  4972.9  806.05  5027.1  806.05  5028.1  808.05  5032.8  808.09
  5034.4  816.47  5037.6  819.64  5054.0  823.49  5070.7  824.63  5085.2  824.51
  5151.1  821.92  5171.9  821.76  5191.2  824.92  5211.8  826.60  5228.7  829.10
  5244.1  829.80  5333.4  838.95  5385.6  843.09  5408.2  846.43  5422.9  847.66
#Mann=4,-1,0
  4640.2    0.06       0  4882.0    0.12       0  4971.9    0.04       0
  5028.1    0.12       0
#XS Ineff=2,0
       0                 5070.70    0.00  824.63
Permanent Ineff=
       F       F
Bank Sta=4971.9,5028.1
XS Rating Curve= 0
Exp/Cntr=0.3,0.1

Type RM Length L Ch R = 1,30773,499,499,499
BEGIN DESCRIPTION:
North Hunting Creek 58.0
END DESCRIPTION:
XS GIS Cut Line= 4
      1477338.09       846708.55      1477284.26       846762.38
      1477149.67       846930.10      1477052.34       847021.22
#Sta/Elev= 30
  4866.8  856.65  4886.2  844.47  4903.1  833.06  4906.7  830.82  4920.1  822.99
  4924.7  821.13  4940.7  817.45  4963.9  810.68  4968.6  810.63  4971.3  807.86
  4972.3  805.86  5027.7  805.86  5028.7  807.86  5029.5  816.76  5036.7  818.21
  5049.0  821.63  5053.9  821.11  5064.3  820.56  5082.0  821.02  5099.7  825.52
  5100.7  825.57  5117.7  824.87  5136.2  825.19  5148.2  825.66  5183.0  828.32
  5204.2  830.53  5255.3  838.19  5270.5  841.28  5273.5  842.15  5291.3  846.18
#Mann=3,-1,0
  4866.8    0.12       0  4971.3    0.04       0  5028.7    0.12       0
#XS Ineff=2,0
       0                 5049.00    0.00  821.63
Permanent Ineff=
       F       F
Bank Sta=4971.3,5028.7
XS Rating Curve= 0
Exp/Cntr=0.3,0.1

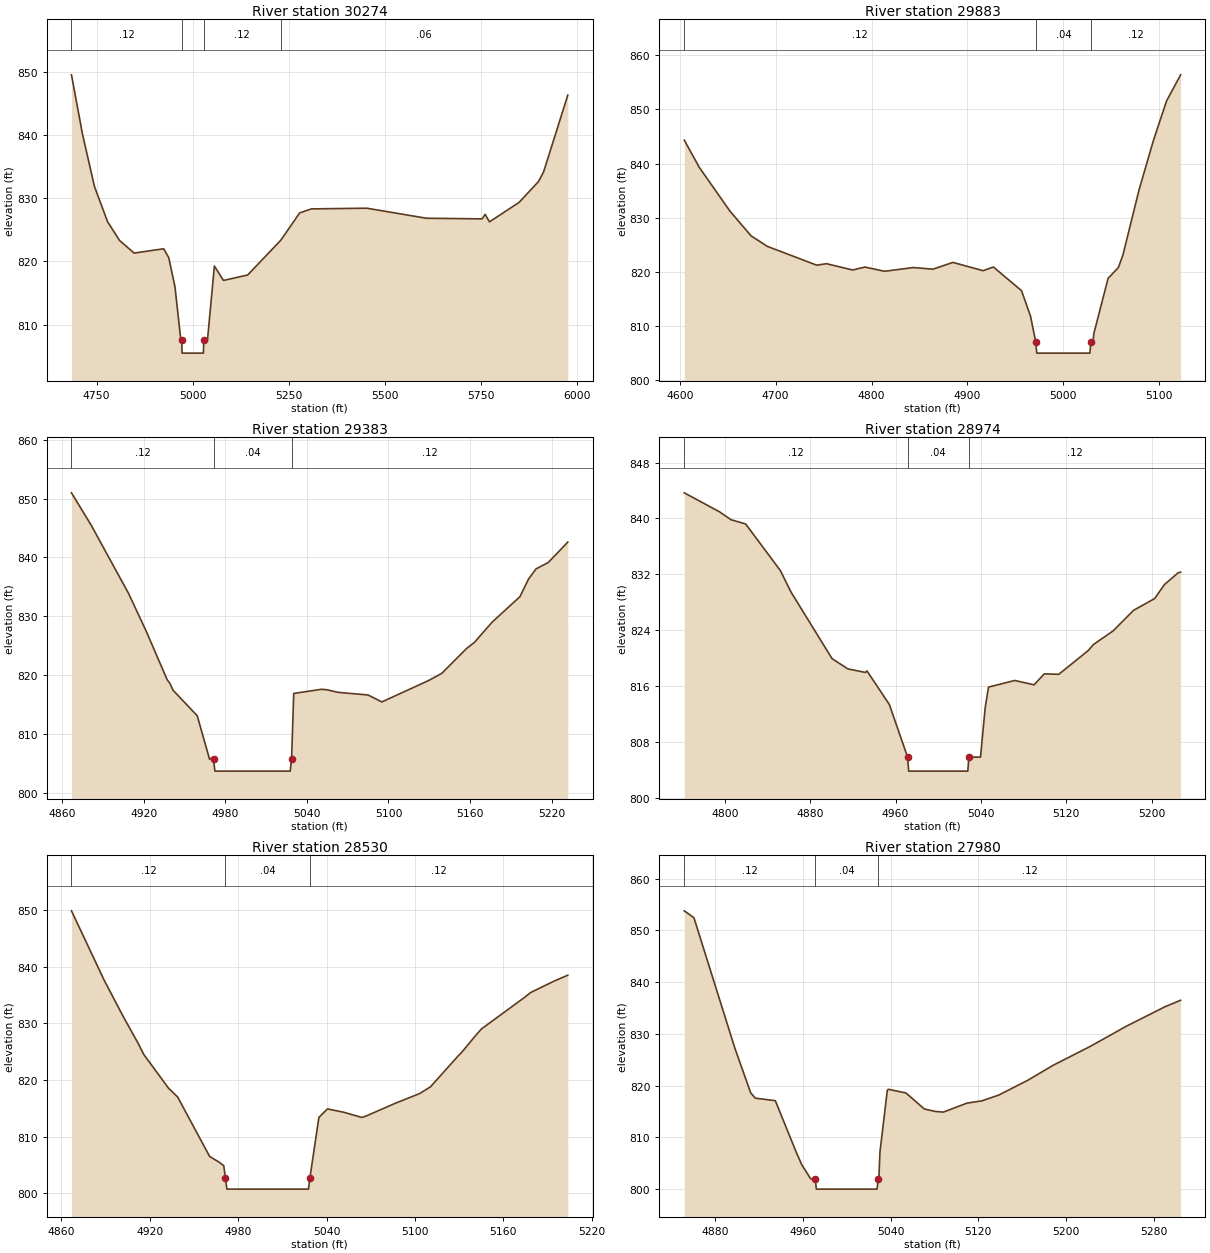
Type RM Length L Ch R = 1,30274,391,391,391
BEGIN DESCRIPTION:
North Hunting Creek 57.0
END DESCRIPTION:
XS GIS Cut Line= 6
      1477269.75       846443.49      1477133.10       846393.80
      1476774.88       846410.37      1476650.64       846480.77
      1476248.93       846219.87      1476106.10       846302.67
#Sta/Elev= 30
  4684.6  849.53  4713.0  840.22  4744.2  831.89  4778.7  826.26  4809.6  823.33
  4847.5  821.33  4924.3  822.01  4937.6  820.60  4953.7  816.04  4969.1  807.54
  4971.3  807.50  4972.3  805.50  5027.7  805.50  5028.7  807.50  5038.2  807.50
  5056.3  819.28  5079.9  817.00  5142.9  817.86  5229.0  823.36  5278.2  827.69
  5308.9  828.32  5452.5  828.43  5607.7  826.84  5752.7  826.74  5760.4  827.46
  5771.8  826.27  5849.1  829.36  5899.3  832.65  5912.7  834.19  5975.5  846.32
#Mann=4,-1,0
  4684.6    0.12       0  4971.3    0.04       0  5028.7    0.12       0
  5229.0    0.06       0
Bank Sta=4971.3,5028.7
XS Rating Curve= 0
Exp/Cntr=0.3,0.1

Type RM Length L Ch R = 1,29883,500,500,500
BEGIN DESCRIPTION:
North Hunting Creek 56.0
END DESCRIPTION:
XS GIS Cut Line= 4
      1477344.30       846350.32      1477236.63       846279.92
      1477077.19       846012.81      1477039.90       845944.43
#Sta/Elev= 30
  4604.7  844.32  4620.4  839.28  4652.3  831.23  4674.3  826.66  4691.3  824.71
  4742.8  821.24  4753.0  821.51  4780.3  820.35  4793.1  820.89  4813.5  820.11
  4843.5  820.80  4864.0  820.50  4884.9  821.75  4916.3  820.22  4927.1  820.90
  4956.4  816.53  4965.8  811.82  4971.3  807.00  4972.3  805.00  5027.7  805.00
  5028.7  807.00  5031.1  807.06  5031.7  808.51  5046.7  818.81  5057.4  820.80
  5062.2  823.14  5078.9  835.09  5094.1  844.35  5107.6  851.53  5122.3  856.38
#Mann=3,-1,0
  4604.7    0.12       0  4971.3    0.04       0  5028.7    0.12       0
Bank Sta=4971.3,5028.7
XS Rating Curve= 0
Exp/Cntr=0.3,0.1

Type RM Length L Ch R = 1,29383,409,409,409
BEGIN DESCRIPTION:
North Hunting Creek 55.0
END DESCRIPTION:
XS GIS Cut Line= 4
      1477640.43       845890.65      1477553.44       845840.94
      1477414.71       845776.75      1477313.28       845729.14
#Sta/Elev= 30
  4866.8  850.97  4881.4  845.44  4908.9  833.85  4921.8  827.48  4937.2  819.25
  4939.2  818.65  4941.5  817.48  4959.3  813.15  4968.4  805.75  4969.5  805.95
  4971.3  805.75  4972.3  803.75  5027.7  803.75  5028.7  805.75  5030.3  816.93
  5050.6  817.63  5054.6  817.56  5063.1  817.11  5085.0  816.67  5095.1  815.49
  5129.6  819.13  5139.2  820.34  5157.3  824.53  5163.1  825.57  5176.3  829.04
  5196.7  833.35  5202.9  836.29  5208.5  838.06  5217.5  839.14  5231.9  842.61
#Mann=3,-1,0
  4866.8    0.12       0  4971.3    0.04       0  5028.7    0.12       0
Bank Sta=4971.3,5028.7
XS Rating Curve= 0
Exp/Cntr=0.3,0.1

Type RM Length L Ch R = 1,28974,444,444,444
BEGIN DESCRIPTION:
North Hunting Creek 54.0
END DESCRIPTION:
XS GIS Cut Line= 4
      1477814.34       845650.42      1477768.79       845486.86
      1477605.21       845420.60      1477495.46       845375.04
#Sta/Elev= 30
  4762.0  843.67  4794.8  840.97  4805.9  839.81  4819.5  839.21  4852.0  832.54
  4862.1  829.43  4900.5  819.91  4915.3  818.44  4931.8  817.93  4933.2  818.15
  4954.2  813.33  4971.3  805.79  4972.3  803.79  5027.7  803.79  5028.7  805.79
  5039.6  805.80  5044.0  812.89  5047.1  815.83  5071.6  816.78  5089.8  816.16
  5099.4  817.73  5112.9  817.66  5140.4  821.05  5145.4  821.93  5163.8  823.88
  5183.0  826.83  5202.8  828.52  5212.0  830.53  5224.9  832.22  5227.1  832.30
#Mann=3,-1,0
  4762.0    0.12       0  4971.3    0.04       0  5028.7    0.12       0
Bank Sta=4971.3,5028.7
XS Rating Curve= 0
Exp/Cntr=0.3,0.1

Type RM Length L Ch R = 1,28530,550,550,550
BEGIN DESCRIPTION:
North Hunting Creek 53.0
END DESCRIPTION:
XS GIS Cut Line= 4
      1477936.50       845016.83      1477837.12       845031.32
      1477710.81       845025.11      1477601.02       845016.82
#Sta/Elev= 30
  4866.8  849.83  4888.8  837.70  4901.7  831.31  4912.2  826.40  4915.9  824.50
  4932.7  818.56  4938.9  817.00  4960.6  806.53  4967.2  805.48  4970.2  804.90
  4971.3  802.76  4972.3  800.76  5027.7  800.76  5028.7  802.76  5034.8  813.41
  5040.6  814.90  5051.6  814.32  5063.9  813.40  5066.5  813.61  5086.8  815.91
  5103.2  817.61  5110.6  818.81  5129.4  824.26  5131.6  824.83  5141.2  827.84
  5145.2  829.01  5174.4  834.56  5178.6  835.43  5194.7  837.46  5203.8  838.48
#Mann=3,-1,0
  4866.8    0.12       0  4971.3    0.04       0  5028.7    0.12       0
Bank Sta=4971.3,5028.7
XS Rating Curve= 0
Exp/Cntr=0.3,0.1

Type RM Length L Ch R = 1,27980,502,502,502
BEGIN DESCRIPTION:
North Hunting Creek 52.0
END DESCRIPTION:
XS GIS Cut Line= 4
      1477692.20       844474.30      1477594.85       844530.22
      1477476.83       844623.40      1477416.79       844803.52
#Sta/Elev= 30
  4851.9  853.76  4860.7  852.43  4898.1  827.19  4912.4  818.64  4916.6  817.59
  4934.9  817.10  4954.1  807.09  4959.0  804.74  4967.1  802.02  4971.3  802.02
  4972.3  800.02  5027.7  800.02  5028.7  802.02  5029.3  802.02  5030.3  807.18
  5037.0  819.09  5037.9  819.30  5054.0  818.59  5070.8  815.49  5080.6  815.03
  5088.1  814.89  5109.6  816.63  5123.1  817.06  5138.6  818.18  5164.9  821.02
  5188.0  823.91  5222.1  827.59  5254.8  831.46  5290.1  835.23  5304.4  836.49
#Mann=3,-1,0
  4851.9    0.12       0  4971.3    0.04       0  5028.7    0.12       0
#XS Ineff=2,0
       0                 5037.00    0.00  819.09
Permanent Ineff=
       F       F
Bank Sta=4971.3,5028.7
XS Rating Curve= 0
Exp/Cntr=0.3,0.1

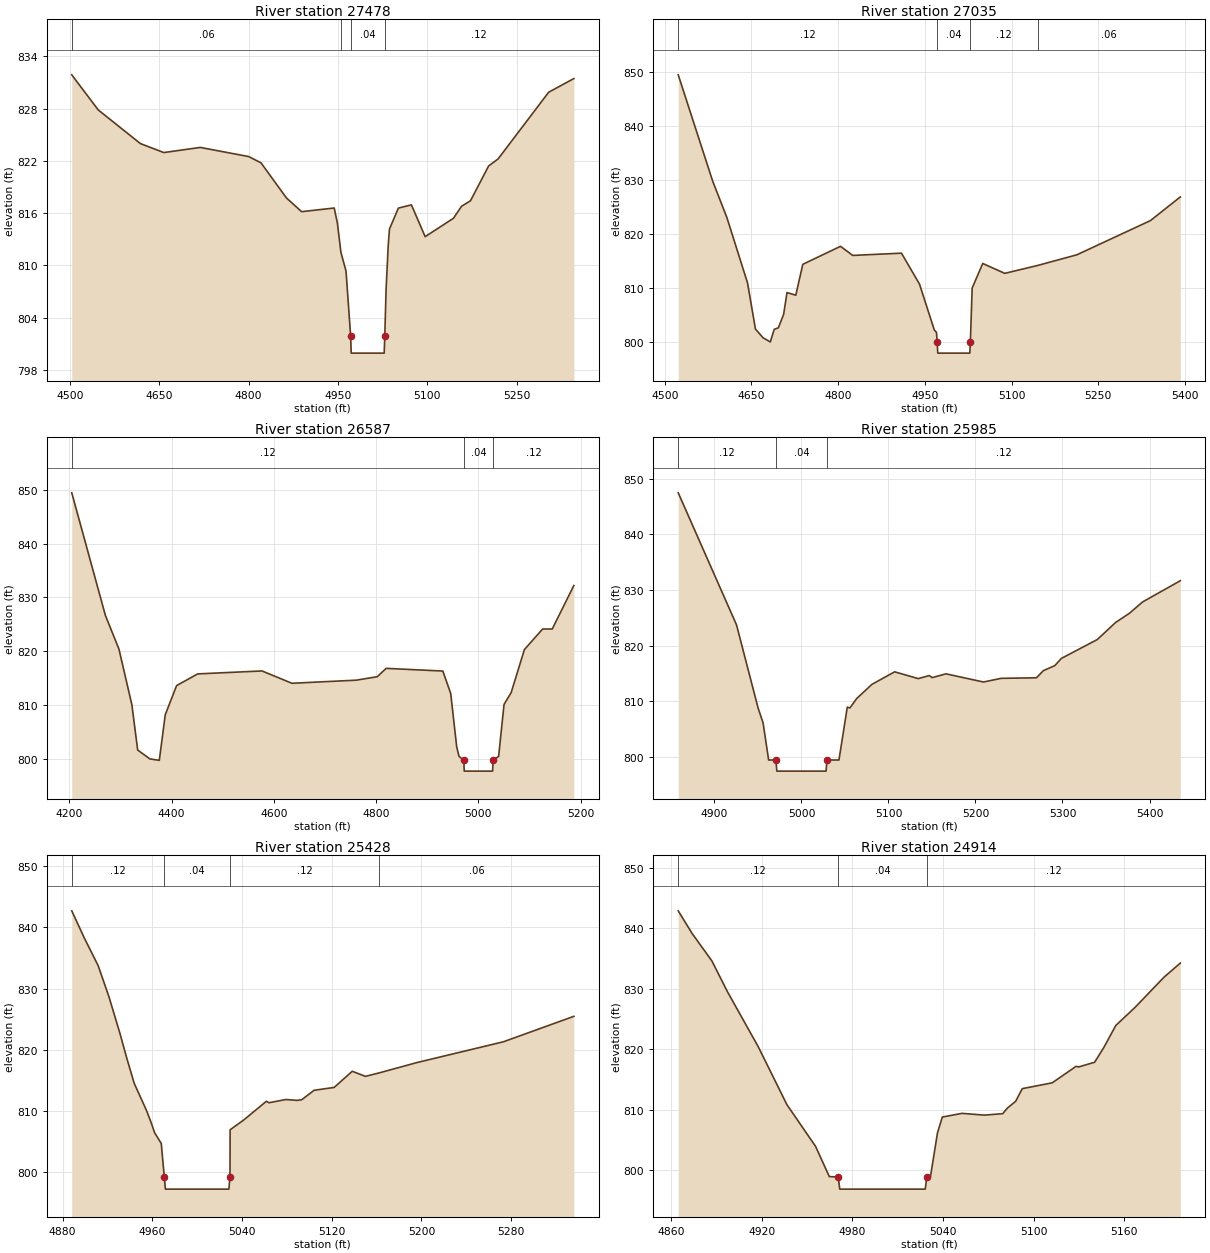
Type RM Length L Ch R = 1,27478,443,443,443
BEGIN DESCRIPTION:
North Hunting Creek 51.0
END DESCRIPTION:
XS GIS Cut Line= 4
      1477721.13       844229.95      1477472.69       844033.27
      1477174.51       844194.78      1477026.90       844309.93
#Sta/Elev= 30
  4503.0  831.89  4547.4  827.86  4618.3  823.99  4657.6  822.96  4718.8  823.55
  4800.2  822.50  4820.8  821.78  4863.5  817.75  4889.0  816.17  4943.8  816.59
  4949.2  814.81  4955.0  811.50  4963.6  809.35  4971.3  801.92  4972.3  799.92
  5027.7  799.92  5028.7  801.92  5030.9  807.27  5034.5  812.33  5036.6  814.18
  5051.5  816.58  5073.4  816.95  5096.5  813.30  5144.0  815.41  5157.6  816.79
  5172.7  817.43  5203.1  821.42  5219.0  822.23  5303.9  829.89  5346.2  831.46
#Mann=4,-1,0
  4503.0    0.06       0  4955.0    0.12       0  4971.3    0.04       0
  5028.7    0.12       0
#XS Ineff=2,0
       0                 5073.40    0.00  816.95
Permanent Ineff=
       F       F
Bank Sta=4971.3,5028.7
XS Rating Curve= 0
Exp/Cntr=0.3,0.1

Type RM Length L Ch R = 1,27035,448,448,448
BEGIN DESCRIPTION:
North Hunting Creek 50.0
END DESCRIPTION:
XS GIS Cut Line= 4
      1477514.10       843594.29      1477385.72       843631.56
      1476919.82       843813.78      1476826.64       844029.14
#Sta/Elev= 30
  4523.3  849.44  4582.7  829.80  4607.7  822.93  4643.2  810.88  4656.9  802.34
  4669.9  800.74  4682.6  799.95  4689.3  802.28  4696.5  802.57  4705.6  805.05
  4711.5  809.10  4726.7  808.61  4738.8  814.33  4804.0  817.67  4825.2  815.98
  4909.5  816.40  4940.7  810.67  4966.3  802.17  4970.1  801.71  4971.3  799.88
  4972.3  797.88  5027.7  797.88  5028.7  799.88  5031.8  809.93  5050.1  814.49
  5088.2  812.66  5145.0  814.12  5213.0  816.10  5340.2  822.43  5391.9  826.82
#Mann=4,-1,0
  4523.3    0.12       0  4971.3    0.04       0  5028.7    0.12       0
  5145.0    0.06       0
#XS Ineff=2,0
    0.00 4804.00  817.67               0
Permanent Ineff=
       F       F
Bank Sta=4971.3,5028.7
XS Rating Curve= 0
Exp/Cntr=0.3,0.1

Type RM Length L Ch R = 1,26587,602,602,602
BEGIN DESCRIPTION:
North Little Hunting Creek 49.5
END DESCRIPTION:
XS GIS Cut Line= 5
      1477506.71       843577.10      1477178.73       843688.00
      1476850.79       843437.91      1476787.08       843360.05
      1476834.26       843246.83
#Sta/Elev= 30
  4204.7  849.42  4270.4  826.68  4297.0  820.40  4322.3  810.05  4333.6  801.67
  4357.5  800.02  4375.9  799.75  4387.5  808.20  4409.7  813.63  4450.9  815.80
  4576.8  816.35  4635.2  814.06  4761.4  814.64  4802.1  815.28  4819.6  816.83
  4930.4  816.33  4945.8  812.17  4957.5  802.27  4962.0  800.51  4971.3  799.75
  4972.3  797.75  5027.7  797.75  5028.7  799.75  5039.5  800.49  5050.1  810.14
  5063.9  812.30  5089.9  820.32  5125.5  824.13  5144.4  824.14  5186.6  832.21
#Mann=3,-1,0
  4204.7    0.12       0  4971.3    0.04       0  5028.7    0.12       0
#XS Ineff=2,0
    0.00 4819.60  816.83               0
Permanent Ineff=
       F       F
Bank Sta=4971.3,5028.7
XS Rating Curve= 0
Exp/Cntr=0.3,0.1

Type RM Length L Ch R = 1,25985,557,557,557
BEGIN DESCRIPTION:
North Hunting Creek 49.0
END DESCRIPTION:
XS GIS Cut Line= 4
      1477499.56       843563.22      1477404.35       843550.81
      1477120.68       843376.87      1477008.87       843279.56
#Sta/Elev= 30
  4858.4  847.46  4925.4  823.73  4950.2  808.79  4955.9  806.14  4962.3  799.46
  4970.7  799.46  4971.7  797.46  5028.3  797.46  5029.3  799.46  5043.1  799.46
  5052.7  808.96  5055.7  808.81  5063.6  810.52  5081.0  813.05  5107.1  815.30
  5134.3  814.08  5146.9  814.63  5150.2  814.26  5166.1  814.94  5209.2  813.47
  5229.5  814.13  5270.1  814.23  5278.0  815.51  5291.2  816.42  5298.7  817.71
  5340.0  821.10  5361.2  824.19  5376.8  825.80  5391.9  827.84  5435.4  831.67
#Mann=3,-1,0
  4858.4    0.12       0  4970.7    0.04       0  5029.3    0.12       0
#XS Ineff=2,0
       0                 5107.10    0.00  815.30
Permanent Ineff=
       F       F
Bank Sta=4970.7,5029.3
XS Rating Curve= 0
Exp/Cntr=0.3,0.1

Type RM Length L Ch R = 1,25428,514,514,514
BEGIN DESCRIPTION:
North Hunting Creek 48.0
END DESCRIPTION:
XS GIS Cut Line= 4
      1477474.77       842973.10      1477385.72       842968.95
      1477238.70       842979.31      1477050.24       843074.57
#Sta/Elev= 30
  4888.2  842.72  4899.4  838.27  4911.7  833.77  4921.4  828.64  4931.3  822.58
  4937.1  818.71  4943.9  814.49  4954.6  810.16  4958.9  808.12  4962.1  806.41
  4968.0  804.66  4970.7  799.19  4971.7  797.19  5028.3  797.19  5029.3  799.19
  5029.4  806.90  5041.8  808.54  5061.8  811.57  5064.0  811.32  5079.1  811.85
  5089.1  811.71  5093.2  811.81  5104.3  813.36  5122.2  813.83  5138.3  816.47
  5150.0  815.64  5162.0  816.19  5196.1  817.90  5273.2  821.30  5335.9  825.46
#Mann=4,-1,0
  4888.2    0.12       0  4970.7    0.04       0  5029.3    0.12       0
  5162.0    0.06       0
Bank Sta=4970.7,5029.3
XS Rating Curve= 0
Exp/Cntr=0.3,0.1

Type RM Length L Ch R = 1,24914,515,515,515
BEGIN DESCRIPTION:
North Hunting Creek 47.0
END DESCRIPTION:
XS GIS Cut Line= 4
      1477389.91       842463.72      1477292.54       842465.79
      1477174.51       842474.07      1477058.58       842486.49
#Sta/Elev= 30
  4864.8  842.85  4874.0  839.11  4887.1  834.57  4897.3  829.53  4917.8  820.39
  4936.7  810.86  4955.7  803.96  4964.8  798.97  4970.7  798.90  4971.7  796.90
  5028.3  796.90  5029.3  798.90  5031.7  798.90  5036.4  806.21  5039.6  808.80
  5052.6  809.41  5067.4  809.12  5079.6  809.36  5082.6  810.27  5088.1  811.39
  5092.5  813.49  5112.3  814.45  5128.1  817.17  5129.9  817.08  5140.4  817.85
  5146.6  820.34  5154.4  823.92  5167.2  826.92  5186.3  831.89  5197.1  834.22
#Mann=3,-1,0
  4864.8    0.12       0  4970.7    0.04       0  5029.3    0.12       0
Bank Sta=4970.7,5029.3
XS Rating Curve= 0
Exp/Cntr=0.3,0.1

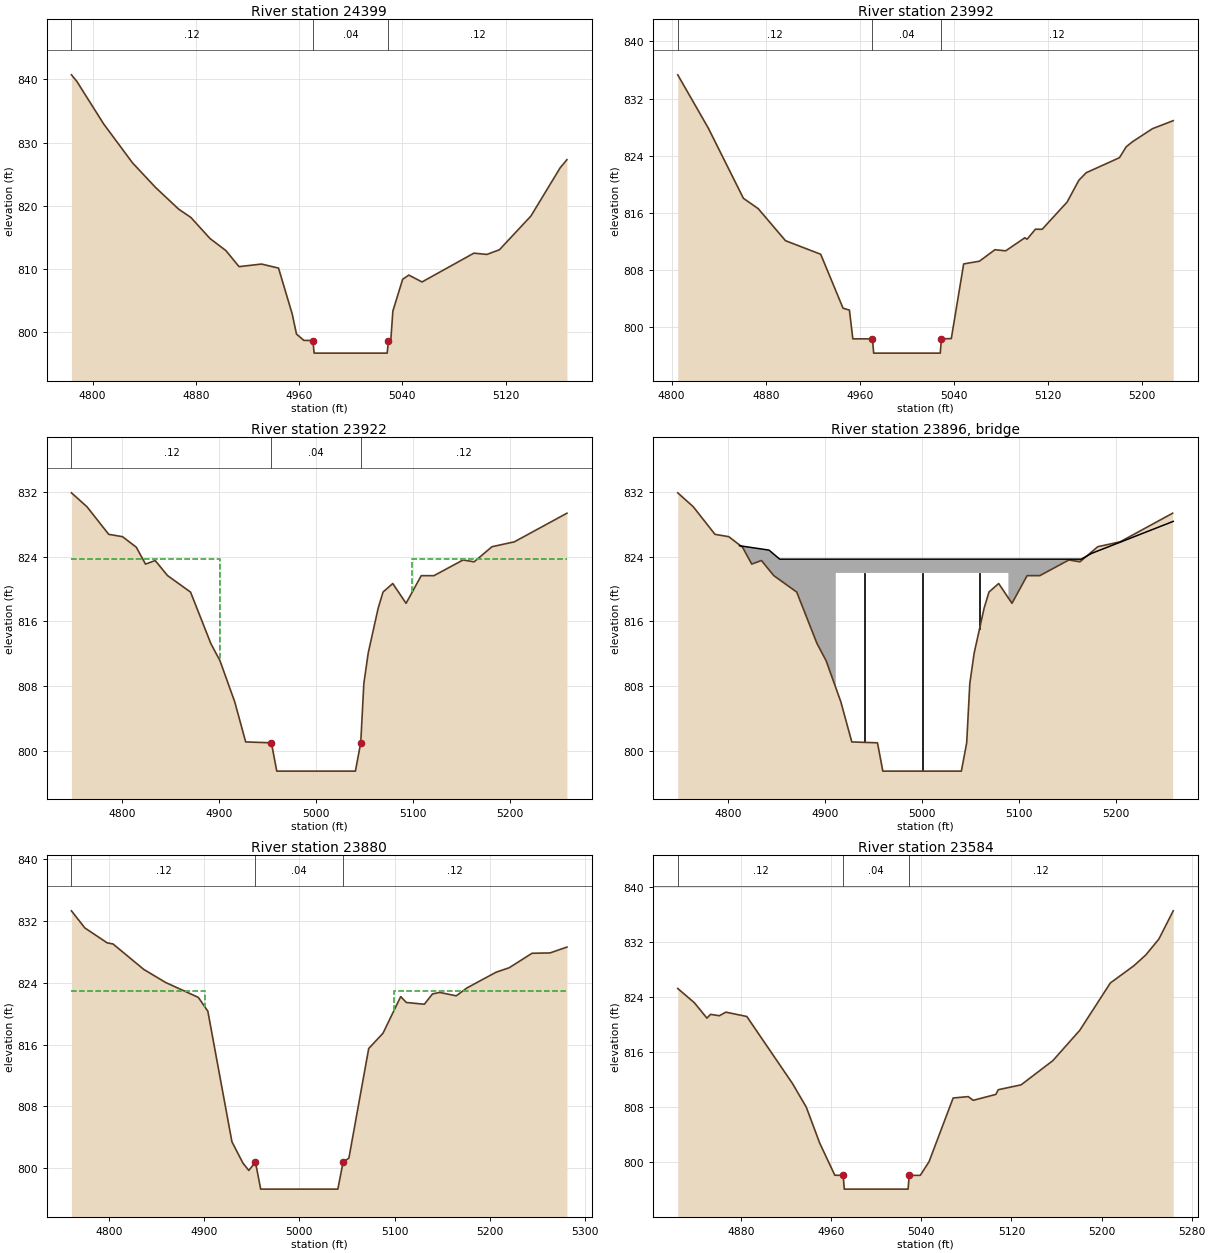
Type RM Length L Ch R = 1,24399,407,407,407
BEGIN DESCRIPTION:
North Hunting Creek 46.0
END DESCRIPTION:
XS GIS Cut Line= 4
      1477356.73       842030.95      1477226.28       841966.76
      1477120.68       841962.62      1476988.16       841972.97
#Sta/Elev= 30
  4783.6  840.74  4787.7  839.73  4808.5  832.97  4831.0  826.76  4848.8  822.87
  4866.7  819.43  4876.2  818.11  4891.0  814.77  4903.3  812.86  4913.5  810.31
  4930.9  810.72  4944.1  810.08  4954.7  802.80  4958.0  799.62  4963.7  798.61
  4970.7  798.59  4971.7  796.59  5028.3  796.59  5029.3  798.59  5031.1  798.59
  5032.7  803.26  5040.3  808.31  5045.1  808.97  5055.3  807.88  5095.5  812.45
  5105.6  812.25  5115.3  812.99  5139.7  818.34  5162.4  826.00  5167.6  827.28
#Mann=3,-1,0
  4783.6    0.12       0  4970.7    0.04       0  5029.3    0.12       0
Bank Sta=4970.7,5029.3
XS Rating Curve= 0
Exp/Cntr=0.3,0.1

Type RM Length L Ch R = 1,23992,70,70,70
BEGIN DESCRIPTION:
North Hunting Creek 45.0
END DESCRIPTION:
XS GIS Cut Line= 4
      1477191.10       841492.58      1477081.33       841523.64
      1476998.51       841608.54      1476926.04       841782.46
#Sta/Elev= 30
  4805.2  835.33  4831.3  827.83  4861.0  818.03  4873.6  816.58  4896.8  812.09
  4926.7  810.19  4945.7  802.63  4951.1  802.37  4954.0  798.34  4970.7  798.34
  4971.7  796.34  5028.3  796.34  5029.3  798.34  5037.7  798.38  5048.2  808.84
  5061.6  809.22  5074.8  810.83  5083.9  810.67  5100.2  812.50  5102.1  812.30
  5109.2  813.70  5114.9  813.69  5136.1  817.50  5146.1  820.56  5152.3  821.61
  5180.6  823.72  5186.4  825.26  5191.7  825.96  5208.6  827.78  5226.3  828.91
#Mann=3,-1,0
  4805.2    0.12       0  4970.7    0.04       0  5029.3    0.12       0
Bank Sta=4970.7,5029.3
XS Rating Curve= 0
Exp/Cntr=0.5,0.3

Type RM Length L Ch R = 1,23922,42,42,42
BEGIN DESCRIPTION:
Barnard Mill Rd - US
END DESCRIPTION:
XS GIS Cut Line= 4
      1477025.43       841283.44      1476994.37       841438.75
      1476959.17       841620.96      1476911.53       841780.44
#Sta/Elev= 30
  4748.0  831.90  4764.0  830.18  4786.4  826.77  4800.6  826.48  4814.8  825.18
  4824.3  823.09  4834.3  823.53  4847.0  821.67  4870.7  819.63  4891.6  813.27
  4901.0  811.15  4916.2  806.07  4927.5  801.11  4954.0  801.00  4959.5  797.50
  5040.5  797.50  5046.0  801.00  5049.2  808.32  5053.7  812.09  5064.0  817.66
  5069.0  819.64  5079.0  820.69  5092.7  818.24  5108.3  821.66  5121.4  821.66
  5151.4  823.60  5162.8  823.37  5181.2  825.24  5204.2  825.84  5258.4  829.38
#Mann=3,-1,0
  4748.0    0.12       0  4954.0    0.04       0  5046.0    0.12       0
#XS Ineff=2,0
    0.00 4901.00  823.70 5099.00    0.00  823.70
Permanent Ineff=
       F       F
Bank Sta=4954,5046
XS Rating Curve= 0
Exp/Cntr=0.5,0.3

Type RM Length L Ch R =3,23896,,,
BEGIN DESCRIPTION:
Barnard Mill Rd - TOR
Structure ID: LDS_NLHC_02
Approximate Survey Structure
END DESCRIPTION:
Bridge Culvert--1,0,-1,-1,0
Deck Dist Width WeirC Skew NumUp NumDn MinLoCord MaxHiCord MaxSubmerge Is_Ogee
13,26,3,,10,10,,,,0,1,1,,,
  4811.7  4842.1  4853.2  4911.0  4911.0  5089.0  5089.0  5164.1  5174.7  5259.0
  825.36  824.82  823.70  823.70  823.70  823.70  823.70  823.70  824.41  828.37
  777.50  777.50  777.50  777.50  822.00  822.00  777.50  777.50  777.50  777.50
  4811.7  4842.1  4853.2  4911.0  4911.0  5089.0  5089.0  5164.1  5174.7  5259.0
  825.36  824.82  823.70  823.70  823.70  823.70  823.70  823.70  824.41  828.37
  777.50  777.50  777.50  777.50  822.00  822.00  777.50  777.50  777.50  777.50
Pier Skew, UpSta & Num, DnSta & Num=,4940.7,2,4940.7,2,0,0,0,0,0
       1       1
  799.01  822.00
       1       1
  800.66  822.00
Pier Skew, UpSta & Num, DnSta & Num=,5000,2,5000,2,0,0,0,0,0
       1       1
  797.50  822.00
       1       1
  797.25  822.00
Pier Skew, UpSta & Num, DnSta & Num=,5059.3,2,5059.3,2,0,0,0,0,0
       1       1
  815.12  822.00
       1       1
  804.34  822.00
Abutment Skew #Up #Dn=,2,2
  4911.0  4978.5
  822.00  797.50
  4911.0  4978.5
  822.00  797.25
Abutment Skew #Up #Dn=,2,2
  5021.5  5089.0
  797.50  822.00
  5021.5  5089.0
  797.25  822.00
BR Coef=1,1,0,1.25,0,,,0.8,0,2,0,
WSPro=,,,, 1 ,,,, 0 ,,,, 0 ,,,,-1 ,-1 ,-1 , 0 , 0 , 0 , 0 , 0
BC Design=,,0,,0,,,,,,

Type RM Length L Ch R = 1,23880,296,296,296
BEGIN DESCRIPTION:
Barnard Mill Rd - DS
END DESCRIPTION:
XS GIS Cut Line= 4
      1476996.43       841268.98      1476959.17       841434.61
      1476934.32       841562.99      1476890.84       841778.31
#Sta/Elev= 30
  4760.8  833.33  4774.9  831.11  4798.3  829.18  4804.5  829.03  4836.8  825.73
  4859.7  824.04  4894.0  822.11  4904.0  820.32  4929.3  803.39  4940.7  800.66
  4947.0  799.67  4954.0  800.75  4959.5  797.25  5040.5  797.25  5046.0  800.75
  5052.1  801.27  5072.9  815.48  5087.9  817.46  5106.5  822.21  5112.4  821.45
  5131.3  821.22  5139.9  822.56  5147.5  822.75  5164.8  822.31  5176.0  823.33
  5206.6  825.37  5220.4  825.95  5244.4  827.83  5263.2  827.87  5281.0  828.63
#Mann=3,-1,0
  4760.8    0.12       0  4954.0    0.04       0  5046.0    0.12       0
#XS Ineff=2,0
    0.00 4901.00  823.00 5099.00    0.00  823.00
Permanent Ineff=
       F       F
Bank Sta=4954,5046
XS Rating Curve= 0
Exp/Cntr=0.5,0.3

Type RM Length L Ch R = 1,23584,167,167,167
BEGIN DESCRIPTION:
North Hunting Creek 44.0
END DESCRIPTION:
XS GIS Cut Line= 4
      1476611.28       841395.23      1476667.20       841519.50
      1476679.63       841625.10      1476737.59       841813.49
#Sta/Elev= 30
  4823.9  825.25  4838.7  823.17  4849.8  820.94  4853.0  821.49  4860.8  821.29
  4866.6  821.81  4885.2  821.18  4925.7  811.45  4938.0  808.00  4949.9  802.78
  4963.3  798.12  4970.7  798.10  4971.7  796.10  5028.3  796.10  5029.3  798.10
  5039.1  798.10  5046.9  800.08  5068.3  809.34  5081.7  809.54  5086.1  809.00
  5106.2  809.86  5108.3  810.54  5128.6  811.25  5156.8  814.77  5180.7  819.18
  5207.8  826.05  5228.6  828.54  5239.2  830.11  5250.8  832.41  5263.6  836.53
#Mann=3,-1,0
  4823.9    0.12       0  4970.7    0.04       0  5029.3    0.12       0
Bank Sta=4970.7,5029.3
XS Rating Curve= 0
Exp/Cntr=0.3,0.1