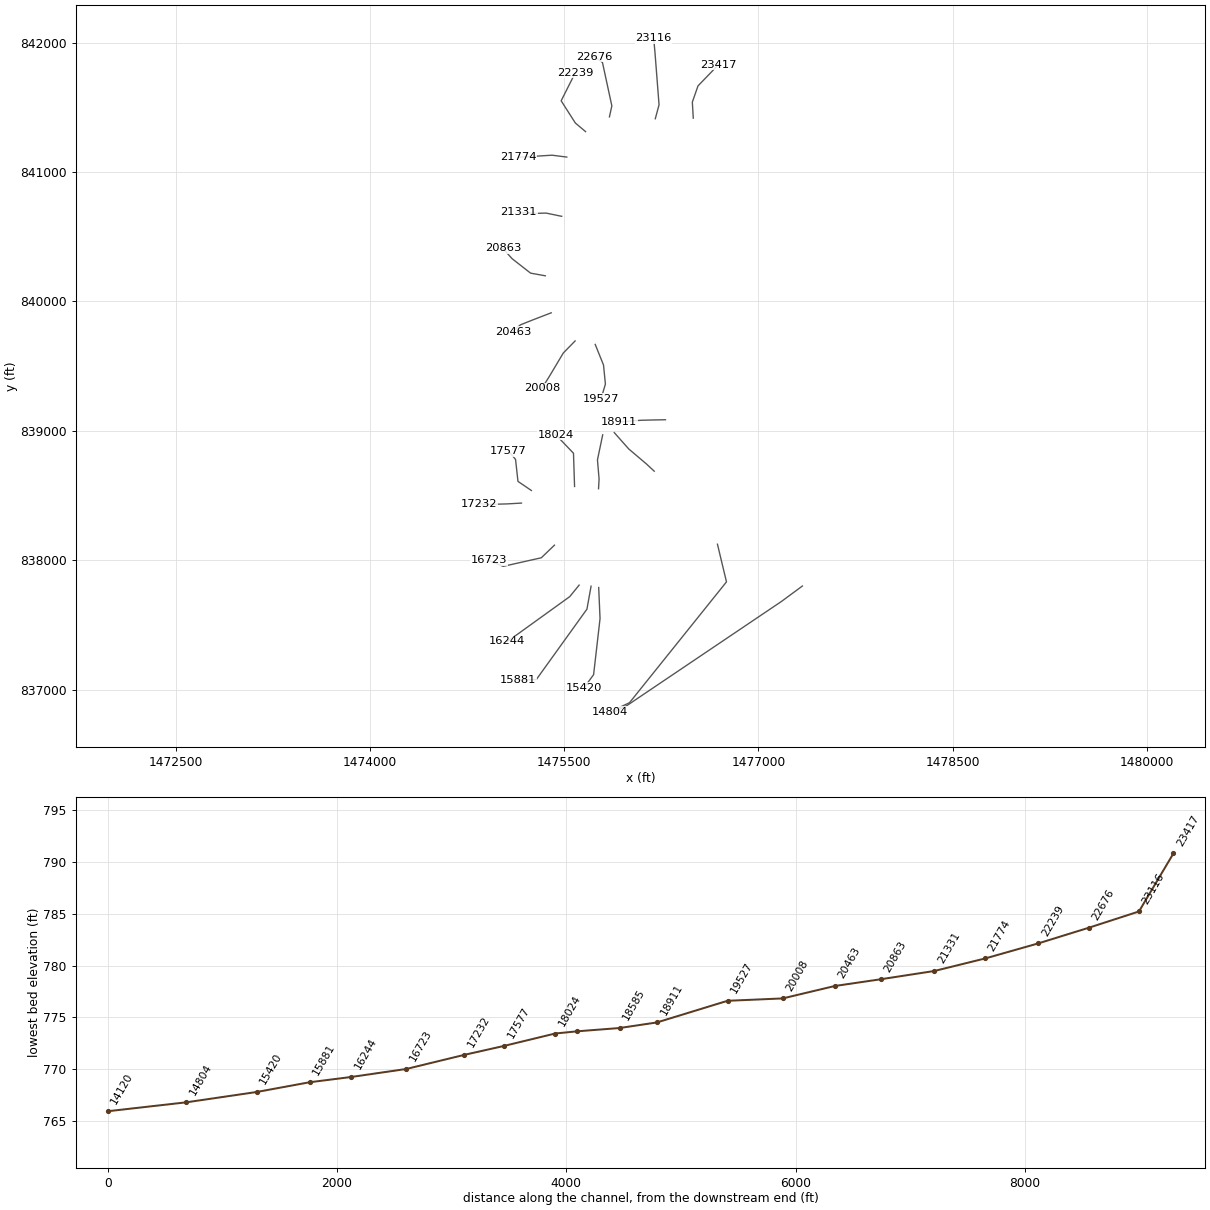
HEC-RAS study North Little Hunting Creek.prj: North Little Hunting Creek Limited Detail Study

--- North Little Hunting Creek.g01 (geometry) --- (continued)

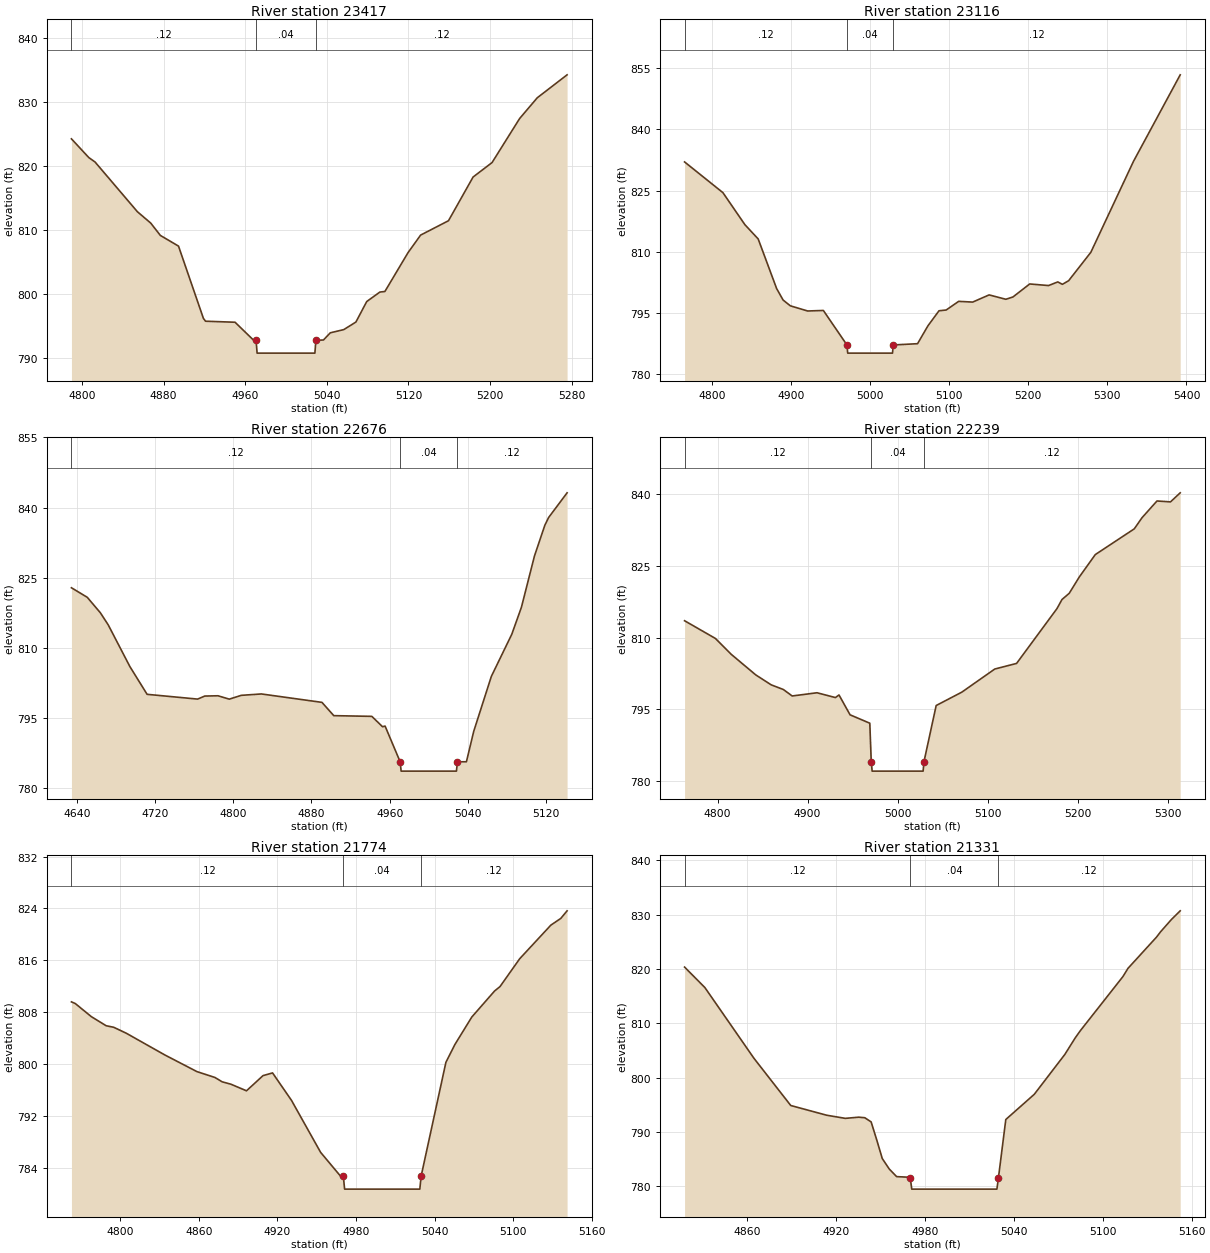
Type RM Length L Ch R = 1,23417,301,301,301
BEGIN DESCRIPTION:
North Little Hunting Creek 43.5
END DESCRIPTION:
XS GIS Cut Line= 4
      1476496.65       841416.41      1476489.36       841540.27
      1476533.09       841665.61      1476691.92       841830.27
#Sta/Elev= 30
  4789.8  824.27  4806.8  821.35  4812.9  820.66  4854.4  812.90  4867.5  811.12
  4876.9  809.20  4894.7  807.53  4919.1  796.25  4921.2  795.81  4950.1  795.65
  4968.1  792.87  4970.7  792.83  4971.7  790.83  5028.3  790.83  5029.3  792.83
  5036.7  792.88  5043.4  794.00  5056.6  794.50  5068.5  795.68  5079.1  798.88
  5092.0  800.36  5096.9  800.45  5119.6  806.52  5131.9  809.25  5159.2  811.49
  5183.3  818.31  5201.9  820.57  5228.9  827.44  5246.2  830.68  5275.4  834.26
#Mann=3,-1,0
  4789.8    0.12       0  4970.7    0.04       0  5029.3    0.12       0
Bank Sta=4970.7,5029.3
XS Rating Curve= 0
Exp/Cntr=0.3,0.1

Type RM Length L Ch R = 1,23116,440,440,440
BEGIN DESCRIPTION:
North Little Hunting Creek 43.0
END DESCRIPTION:
XS GIS Cut Line= 4
      1476203.39       841411.87      1476232.37       841519.50
      1476201.31       841919.14      1476190.95       842033.06
#Sta/Elev= 30
  4765.4  832.05  4813.9  824.52  4841.7  816.68  4858.5  813.18  4881.8  801.04
  4890.0  798.22  4899.1  796.81  4921.0  795.54  4940.9  795.67  4970.7  787.22
  4971.7  785.22  5028.3  785.22  5029.3  787.22  5060.0  787.53  5073.1  791.90
  5087.1  795.59  5096.2  795.78  5112.0  797.90  5129.7  797.72  5150.5  799.48
  5171.6  798.41  5180.6  798.97  5201.8  802.16  5225.6  801.77  5237.3  802.66
  5243.1  802.07  5251.0  802.95  5279.1  809.91  5333.0  832.18  5392.1  853.38
#Mann=3,-1,0
  4765.4    0.12       0  4970.7    0.04       0  5029.3    0.12       0
#XS Ineff=2,0
       0                 5150.50    0.00  799.48
Permanent Ineff=
       F       F
Bank Sta=4970.7,5029.3
XS Rating Curve= 0
Exp/Cntr=0.3,0.1

Type RM Length L Ch R = 1,22676,437,437,437
BEGIN DESCRIPTION:
North Hunting Creek 42.0
END DESCRIPTION:
XS GIS Cut Line= 4
      1475849.31       841426.35      1475867.93       841511.22
      1475795.46       841846.66      1475733.35       841892.22
#Sta/Elev= 30
  4634.4  822.84  4650.6  820.80  4664.0  817.49  4672.0  814.92  4694.2  805.99
  4711.8  800.06  4763.5  799.04  4770.8  799.69  4784.3  799.75  4795.9  799.03
  4808.1  799.84  4828.7  800.14  4890.7  798.34  4902.8  795.50  4941.7  795.35
  4952.7  793.13  4955.3  793.27  4970.7  785.64  4971.7  783.64  5028.3  783.64
  5029.3  785.64  5038.5  785.64  5046.0  792.16  5064.0  803.89  5084.9  812.89
  5094.8  818.69  5108.1  829.62  5118.7  836.19  5122.6  837.86  5141.5  843.14
#Mann=3,-1,0
  4634.4    0.12       0  4970.7    0.04       0  5029.3    0.12       0
Bank Sta=4970.7,5029.3
XS Rating Curve= 0
Exp/Cntr=0.3,0.1

Type RM Length L Ch R = 1,22239,465,465,465
BEGIN DESCRIPTION:
North Hunting Creek 41.0
END DESCRIPTION:
XS GIS Cut Line= 4
      1475665.04       841312.41      1475586.33       841378.70
      1475476.58       841550.56      1475586.34       841768.01
#Sta/Elev= 30
  4763.4  813.50  4797.7  809.80  4815.2  806.50  4842.5  802.20  4859.6  800.13
  4873.1  799.16  4882.9  797.81  4910.5  798.48  4930.9  797.48  4934.9  798.02
  4947.2  793.88  4969.1  792.13  4970.7  784.14  4971.7  782.14  5028.3  782.14
  5029.3  784.14  5042.8  795.82  5071.3  798.61  5107.9  803.43  5132.1  804.60
  5177.0  816.04  5182.5  817.92  5190.6  819.23  5201.8  822.64  5219.5  827.29
  5262.8  832.66  5271.3  834.96  5288.0  838.47  5303.0  838.28  5313.8  840.17
#Mann=3,-1,0
  4763.4    0.12       0  4970.7    0.04       0  5029.3    0.12       0
Bank Sta=4970.7,5029.3
XS Rating Curve= 0
Exp/Cntr=0.3,0.1

Type RM Length L Ch R = 1,21774,443,443,443
BEGIN DESCRIPTION:
North Hunting Creek 40.0
END DESCRIPTION:
XS GIS Cut Line= 3
      1475520.07       841115.73      1475406.18       841130.22
      1475143.21       841113.65
#Sta/Elev= 30
  4762.8  809.57  4765.7  809.32  4778.0  807.29  4789.3  805.89  4795.1  805.65
  4804.6  804.74  4834.1  801.38  4858.6  798.81  4872.3  797.91  4877.8  797.24
  4884.5  796.87  4896.4  795.85  4909.0  798.19  4916.3  798.61  4930.8  794.36
  4953.0  786.35  4968.2  782.68  4970.3  782.68  4971.3  780.68  5028.7  780.68
  5029.7  782.68  5048.6  800.24  5055.4  802.97  5068.4  807.24  5085.8  811.26
  5089.9  811.93  5104.9  816.22  5128.7  821.41  5136.3  822.45  5141.1  823.62
#Mann=3,-1,0
  4762.8    0.12       0  4970.3    0.04       0  5029.7    0.12       0
Bank Sta=4970.3,5029.7
XS Rating Curve= 0
Exp/Cntr=0.3,0.1

Type RM Length L Ch R = 1,21331,468,468,468
BEGIN DESCRIPTION:
North Hunting Creek 39.0
END DESCRIPTION:
XS GIS Cut Line= 4
      1475480.76       840658.11      1475360.63       840682.96
      1475279.87       840680.89      1475149.39       840689.17
#Sta/Elev= 29
  4818.1  820.36  4831.8  816.59  4864.9  803.56  4889.7  794.87  4913.9  793.08
  4926.5  792.50  4935.5  792.72  4939.6  792.62  4943.9  791.85  4947.8  788.42
  4951.4  785.11  4956.1  783.18  4961.1  781.77  4969.6  781.66  4970.3  781.47
  4971.3  779.47  5028.7  779.47  5029.7  781.47  5034.7  792.29  5053.9  796.93
  5074.5  804.27  5081.6  807.36  5085.0  808.66  5113.7  818.62  5117.1  820.13
  5136.3  825.87  5139.1  826.87  5146.4  829.13  5152.3  830.72
#Mann=3,-1,0
  4818.1    0.12       0  4970.3    0.04       0  5029.7    0.12       0
Bank Sta=4970.3,5029.7
XS Rating Curve= 0
Exp/Cntr=0.3,0.1

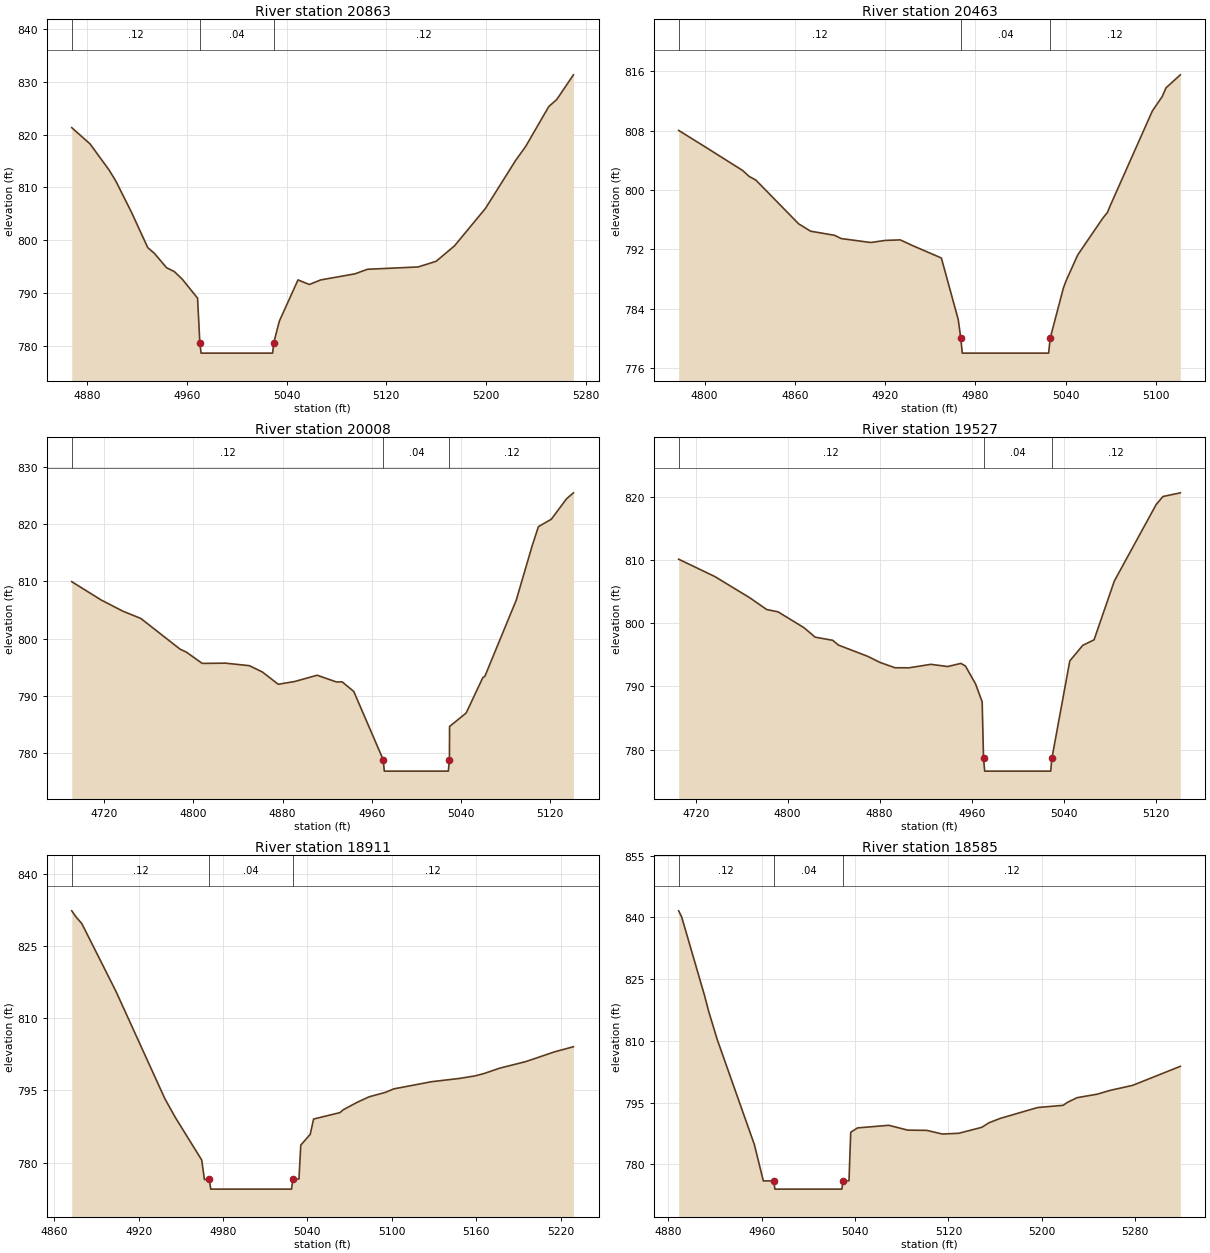
Type RM Length L Ch R = 1,20863,400,400,400
BEGIN DESCRIPTION:
North Hunting Creek 38.0
END DESCRIPTION:
XS GIS Cut Line= 4
      1475354.37       840198.44      1475240.53       840219.14
      1475097.65       840330.95      1475027.26       840409.62
#Sta/Elev= 30
  4867.5  821.32  4882.2  818.24  4897.5  813.30  4903.0  811.17  4915.5  805.29
  4928.5  798.63  4933.9  797.53  4943.6  794.83  4949.8  794.10  4956.2  792.66
  4968.5  789.07  4970.3  780.67  4971.3  778.67  5028.7  778.67  5029.7  780.67
  5034.1  784.70  5049.1  792.52  5058.2  791.65  5067.4  792.52  5094.9  793.67
  5104.8  794.53  5145.5  794.97  5160.0  796.04  5174.8  798.98  5199.6  806.05
  5223.8  815.12  5231.8  817.74  5250.4  825.31  5256.8  826.64  5270.2  831.31
#Mann=3,-1,0
  4867.5    0.12       0  4970.3    0.04       0  5029.7    0.12       0
Bank Sta=4970.3,5029.7
XS Rating Curve= 0
Exp/Cntr=0.3,0.1

Type RM Length L Ch R = 1,20463,455,455,455
BEGIN DESCRIPTION:
North Hunting Creek 37.0
END DESCRIPTION:
XS GIS Cut Line= 4
      1475399.97       839912.68      1475244.67       839852.63
      1475161.84       839819.50      1475103.89       839767.76
#Sta/Elev= 30
  4782.8  808.02  4801.9  805.61  4825.4  802.61  4829.7  801.81  4834.1  801.33
  4862.5  795.44  4870.5  794.44  4886.4  793.89  4890.8  793.45  4910.0  792.93
  4910.9  792.93  4920.2  793.20  4930.1  793.27  4938.3  792.50  4957.4  790.83
  4968.6  782.55  4970.3  780.02  4971.3  778.02  5028.7  778.02  5029.7  780.02
  5038.5  786.80  5040.4  787.82  5048.0  791.24  5064.6  796.17  5067.8  796.98
  5069.9  798.01  5097.6  810.63  5104.2  812.59  5106.7  813.75  5116.2  815.50
#Mann=3,-1,0
  4782.8    0.12       0  4970.3    0.04       0  5029.7    0.12       0
Bank Sta=4970.3,5029.7
XS Rating Curve= 0
Exp/Cntr=0.3,0.1

Type RM Length L Ch R = 1,20008,481,481,481
BEGIN DESCRIPTION:
North Hunting Creek 36.0
END DESCRIPTION:
XS GIS Cut Line= 4
      1475584.25       839695.26      1475493.15       839602.08
      1475383.40       839417.79      1475327.52       839328.79
#Sta/Elev= 30
  4691.0  809.93  4717.4  806.73  4736.9  804.77  4752.9  803.51  4788.2  798.13
  4793.7  797.63  4808.0  795.65  4828.8  795.69  4850.3  795.25  4862.0  794.14
  4876.2  792.00  4891.1  792.49  4911.1  793.58  4928.4  792.40  4933.4  792.43
  4943.9  790.75  4970.3  778.82  4971.3  776.82  5028.7  776.82  5029.7  778.82
  5029.8  784.62  5044.7  786.98  5059.7  793.19  5061.4  793.36  5089.6  806.70
  5104.0  816.27  5109.5  819.55  5121.1  820.85  5134.7  824.42  5140.9  825.46
#Mann=3,-1,0
  4691.0    0.12       0  4970.3    0.04       0  5029.7    0.12       0
Bank Sta=4970.3,5029.7
XS Rating Curve= 0
Exp/Cntr=0.3,0.1

Type RM Length L Ch R = 1,19527,616,616,616
BEGIN DESCRIPTION:
North Hunting Creek 35.0
END DESCRIPTION:
XS GIS Cut Line= 4
      1475739.57       839668.31      1475803.74       839508.90
      1475818.24       839361.89      1475785.11       839250.06
#Sta/Elev= 30
  4705.2  810.13  4736.7  807.38  4767.0  804.03  4781.8  802.16  4791.6  801.80
  4814.1  799.30  4823.9  797.79  4839.2  797.29  4844.1  796.54  4869.4  794.77
  4880.2  793.80  4893.3  792.95  4905.4  792.94  4924.5  793.49  4939.1  793.14
  4950.6  793.64  4954.6  793.22  4963.4  790.38  4969.1  787.56  4970.3  778.59
  4971.3  776.59  5028.7  776.59  5029.7  778.59  5045.3  794.03  5056.6  796.50
  5066.4  797.37  5084.0  806.67  5120.4  818.78  5126.3  820.05  5141.4  820.63
#Mann=3,-1,0
  4705.2    0.12       0  4970.3    0.04       0  5029.7    0.12       0
Bank Sta=4970.3,5029.7
XS Rating Curve= 0
Exp/Cntr=0.3,0.1

Type RM Length L Ch R = 1,18911,326,326,326
BEGIN DESCRIPTION:
North Hunting Creek 34.0
END DESCRIPTION:
XS GIS Cut Line= 4
      1476282.02       839086.49      1476174.39       839084.42
      1476093.64       839082.35      1475925.93       839069.93
#Sta/Elev= 30
  4872.5  832.27  4875.5  831.02  4879.7  829.60  4903.9  815.57  4938.7  793.27
  4946.0  789.44  4964.9  780.53  4966.8  776.50  4970.3  776.50  4971.3  774.50
  5028.7  774.50  5029.7  776.50  5034.0  776.61  5035.3  783.64  5042.0  785.87
  5044.4  789.05  5063.1  790.38  5065.5  790.98  5075.3  792.51  5083.8  793.66
  5095.5  794.59  5101.4  795.31  5128.3  796.80  5148.4  797.49  5159.2  798.01
  5165.6  798.50  5176.8  799.62  5195.2  800.97  5215.7  803.00  5229.1  804.06
#Mann=3,-1,0
  4872.5    0.12       0  4970.3    0.04       0  5029.7    0.12       0
Bank Sta=4970.3,5029.7
XS Rating Curve= 0
Exp/Cntr=0.3,0.1

Type RM Length L Ch R = 1,18585,371,371,371
BEGIN DESCRIPTION:
North Hunting Creek 33.0
END DESCRIPTION:
XS GIS Cut Line= 4
      1476195.11       838688.92      1476135.05       838744.83
      1475998.39       838860.79      1475886.56       838987.12
#Sta/Elev= 30
  4888.8  841.58  4891.4  840.10  4911.1  820.91  4914.5  817.21  4921.9  810.29
  4953.7  784.79  4961.4  775.96  4970.3  775.96  4971.3  773.96  5028.7  773.96
  5029.7  775.96  5034.8  775.97  5036.3  787.78  5042.2  788.84  5068.9  789.47
  5085.3  788.29  5101.4  788.24  5115.0  787.34  5128.9  787.53  5148.7  788.98
  5154.9  790.10  5164.5  791.15  5196.5  793.79  5218.3  794.32  5222.1  795.05
  5230.3  796.18  5247.6  797.03  5258.6  797.95  5277.9  799.17  5318.8  803.80
#Mann=3,-1,0
  4888.8    0.12       0  4970.3    0.04       0  5029.7    0.12       0
#XS Ineff=2,0
       0                 5068.90    0.00  789.47
Permanent Ineff=
       F       F
Bank Sta=4970.3,5029.7
XS Rating Curve= 0
Exp/Cntr=0.3,0.1

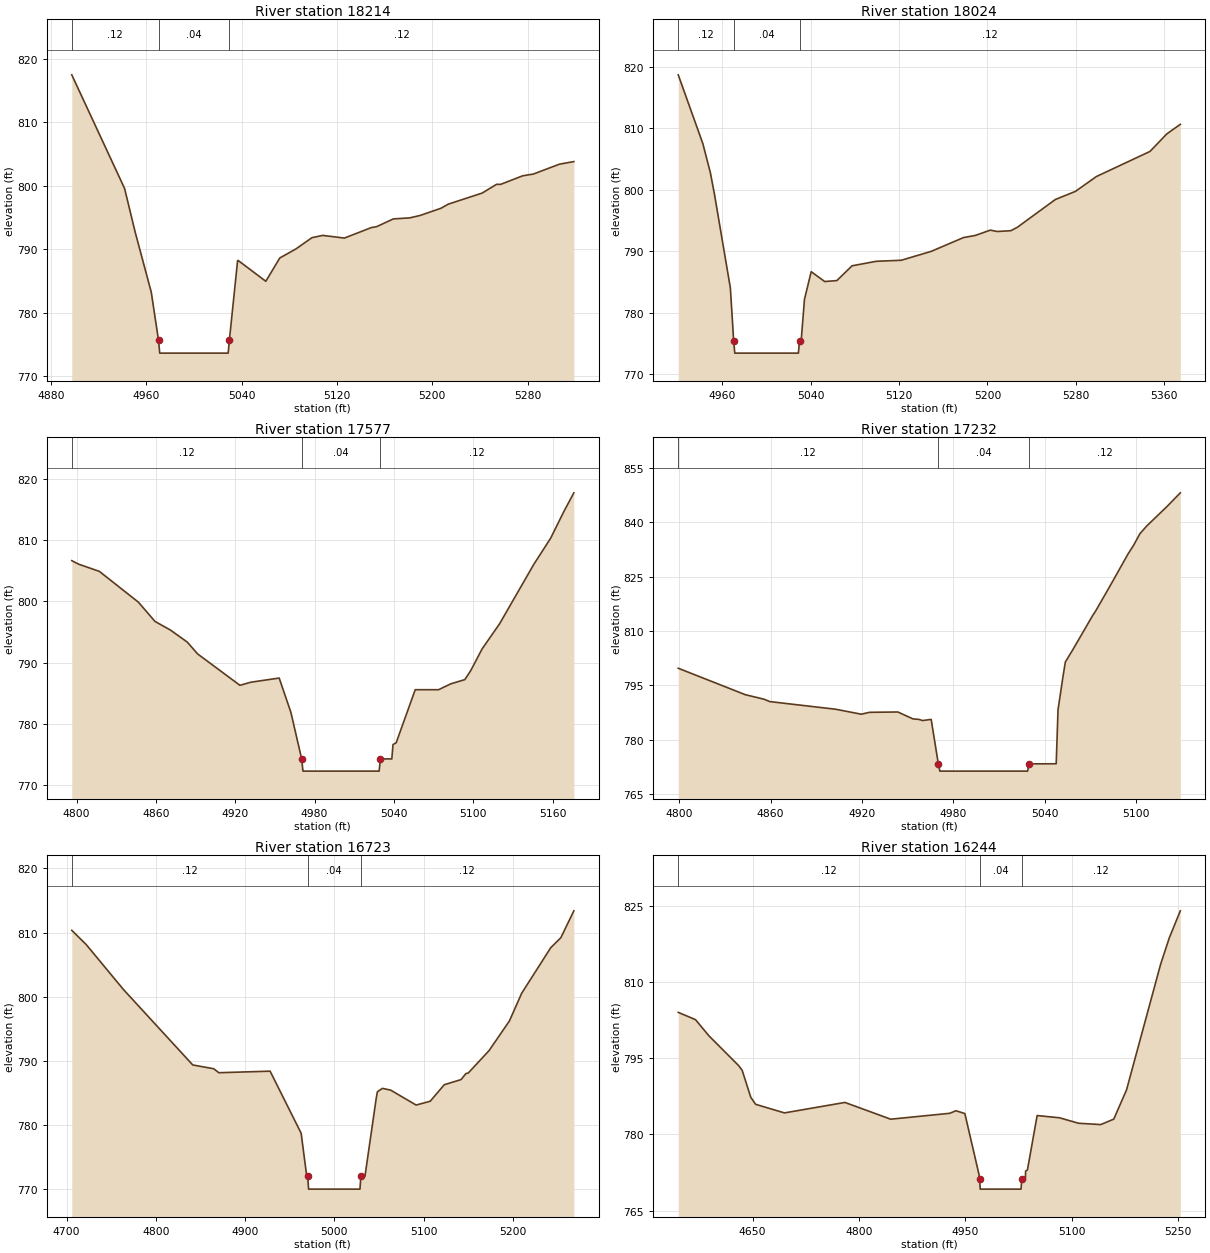
Type RM Length L Ch R = 1,18214,190,190,190
BEGIN DESCRIPTION:
North Little Hunting Creek 32.5
END DESCRIPTION:
XS GIS Cut Line= 4
      1475765.24       838553.46      1475769.42       838628.69
      1475756.89       838776.29      1475797.28       838969.85
#Sta/Elev= 30
  4897.5  817.49  4941.8  799.59  4950.7  792.70  4964.2  783.24  4970.3  775.64
  4971.3  773.64  5028.7  773.64  5029.7  775.64  5036.6  788.18  5037.0  788.25
  5060.3  784.96  5072.0  788.63  5085.4  790.04  5099.0  791.83  5108.0  792.19
  5126.2  791.77  5148.8  793.42  5153.3  793.57  5167.3  794.79  5181.0  794.95
  5189.7  795.33  5207.3  796.47  5213.3  797.11  5241.8  798.86  5253.9  800.24
  5257.3  800.23  5275.8  801.58  5284.8  801.86  5306.6  803.41  5318.7  803.82
#Mann=3,-1,0
  4897.5    0.12       0  4970.3    0.04       0  5029.7    0.12       0
Bank Sta=4970.3,5029.7
XS Rating Curve= 0
Exp/Cntr=0.3,0.1

Type RM Length L Ch R = 1,18024,447,447,447
BEGIN DESCRIPTION:
North Little Hunting Creek 32.0
END DESCRIPTION:
XS GIS Cut Line= 3
      1475580.12       838570.88      1475571.83       838827.66
      1475435.19       838970.51
#Sta/Elev= 30
  4920.0  818.71  4942.3  807.51  4949.1  802.78  4952.7  799.39  4967.2  784.05
  4970.2  775.43  4971.2  773.43  5028.8  773.43  5029.8  775.43  5031.3  775.43
  5034.3  782.19  5040.4  786.68  5052.6  785.08  5063.6  785.23  5077.4  787.64
  5099.3  788.37  5122.0  788.54  5149.1  789.99  5178.3  792.23  5189.0  792.58
  5202.6  793.44  5208.8  793.22  5221.2  793.35  5227.0  793.90  5261.5  798.43
  5279.7  799.75  5298.6  802.16  5347.1  806.24  5362.4  809.10  5374.6  810.66
#Mann=3,-1,0
  4920.0    0.12       0  4970.2    0.04       0  5029.8    0.12       0
Bank Sta=4970.2,5029.8
XS Rating Curve= 0
Exp/Cntr=0.3,0.1

Type RM Length L Ch R = 1,17577,345,345,345
BEGIN DESCRIPTION:
North Hunting Creek 31.0
END DESCRIPTION:
XS GIS Cut Line= 4
      1475246.74       838539.84      1475143.21       838610.24
      1475124.57       838780.04      1475070.73       838844.23
#Sta/Elev= 30
  4796.3  806.69  4801.5  806.11  4817.2  804.93  4846.7  799.89  4859.3  796.73
  4870.9  795.33  4883.6  793.37  4891.5  791.42  4923.5  786.28  4931.9  786.79
  4953.2  787.47  4962.1  781.82  4970.2  774.23  4971.2  772.23  5028.8  772.23
  5029.8  774.23  5038.4  774.23  5039.3  776.58  5041.7  776.87  5056.1  785.56
  5073.8  785.56  5083.0  786.52  5093.6  787.21  5098.1  788.68  5106.7  792.24
  5119.9  796.34  5145.7  806.04  5158.6  810.38  5168.6  814.75  5176.1  817.79
#Mann=3,-1,0
  4796.3    0.12       0  4970.2    0.04       0  5029.8    0.12       0
#XS Ineff=2,0
    0.00 4953.20  787.47               0
Permanent Ineff=
       F       F
Bank Sta=4970.2,5029.8
XS Rating Curve= 0
Exp/Cntr=0.3,0.1

Type RM Length L Ch R = 1,17232,509,509,509
BEGIN DESCRIPTION:
North Hunting Creek 30.0
END DESCRIPTION:
XS GIS Cut Line= 4
      1475170.12       838442.52      1475058.31       838436.31
      1474917.51       838432.17      1474840.90       838438.38
#Sta/Elev= 30
  4799.4  799.75  4843.4  792.46  4855.7  791.21  4859.5  790.55  4902.8  788.44
  4919.6  787.07  4925.0  787.59  4943.6  787.68  4953.6  785.77  4957.4  785.64
  4959.8  785.32  4965.5  785.64  4970.2  773.37  4971.2  771.37  5028.8  771.37
  5029.8  773.37  5047.6  773.40  5048.8  788.30  5052.2  797.83  5053.6  801.46
  5058.6  804.92  5071.6  814.33  5073.4  815.46  5083.2  822.62  5094.9  831.36
  5098.3  833.57  5102.6  836.87  5107.0  838.96  5120.4  844.38  5129.1  848.13
#Mann=3,-1,0
  4799.4    0.12       0  4970.2    0.04       0  5029.8    0.12       0
Bank Sta=4970.2,5029.8
XS Rating Curve= 0
Exp/Cntr=0.3,0.1

Type RM Length L Ch R = 1,16723,479,479,479
BEGIN DESCRIPTION:
North Hunting Creek 29.0
END DESCRIPTION:
XS GIS Cut Line= 4
      1475424.82       838117.44      1475323.35       838020.11
      1475029.32       837953.85      1474917.55       837999.38
#Sta/Elev= 30
  4705.8  810.35  4722.0  808.13  4763.8  801.11  4841.4  789.36  4864.9  788.77
  4870.6  788.15  4928.1  788.39  4962.9  778.70  4969.1  772.07  4970.2  772.00
  4971.2  770.00  5028.8  770.00  5029.8  772.00  5034.4  772.00  5046.9  784.05
  5048.3  785.18  5054.0  785.71  5063.3  785.43  5091.7  783.11  5107.5  783.70
  5123.3  786.28  5142.1  787.08  5147.5  788.01  5150.2  788.11  5173.5  791.60
  5196.3  796.22  5210.0  800.53  5242.7  807.66  5253.9  809.19  5268.5  813.39
#Mann=3,-1,0
  4705.8    0.12       0  4970.2    0.04       0  5029.8    0.12       0
#XS Ineff=2,0
       0                 5054.00    0.00  785.71
Permanent Ineff=
       F       F
Bank Sta=4970.2,5029.8
XS Rating Curve= 0
Exp/Cntr=0.3,0.1

Type RM Length L Ch R = 1,16244,363,363,363
BEGIN DESCRIPTION:
North Hunting Creek 28.0
END DESCRIPTION:
XS GIS Cut Line= 4
      1475615.32       837808.91      1475542.84       837719.86
      1475134.93       837425.83      1475060.39       837374.07
#Sta/Elev= 30
  4545.1  804.04  4569.5  802.60  4588.2  799.45  4630.1  793.59  4635.3  792.63
  4647.5  787.30  4654.3  785.93  4695.0  784.24  4780.3  786.30  4844.9  783.00
  4928.1  784.16  4937.0  784.66  4949.5  784.11  4969.5  772.10  4970.2  771.23
  4971.2  769.23  5028.8  769.23  5029.8  771.23  5034.9  771.23  5035.2  772.78
  5037.8  773.01  5051.5  783.72  5083.0  783.28  5110.0  782.20  5141.2  781.94
  5159.6  783.01  5177.6  788.76  5225.7  813.50  5238.0  818.72  5253.5  824.03
#Mann=3,-1,0
  4545.1    0.12       0  4970.2    0.04       0  5029.8    0.12       0
#XS Ineff=2,0
    0.00 4937.00  784.66               0
Permanent Ineff=
       F       F
Bank Sta=4970.2,5029.8
XS Rating Curve= 0
Exp/Cntr=0.3,0.1

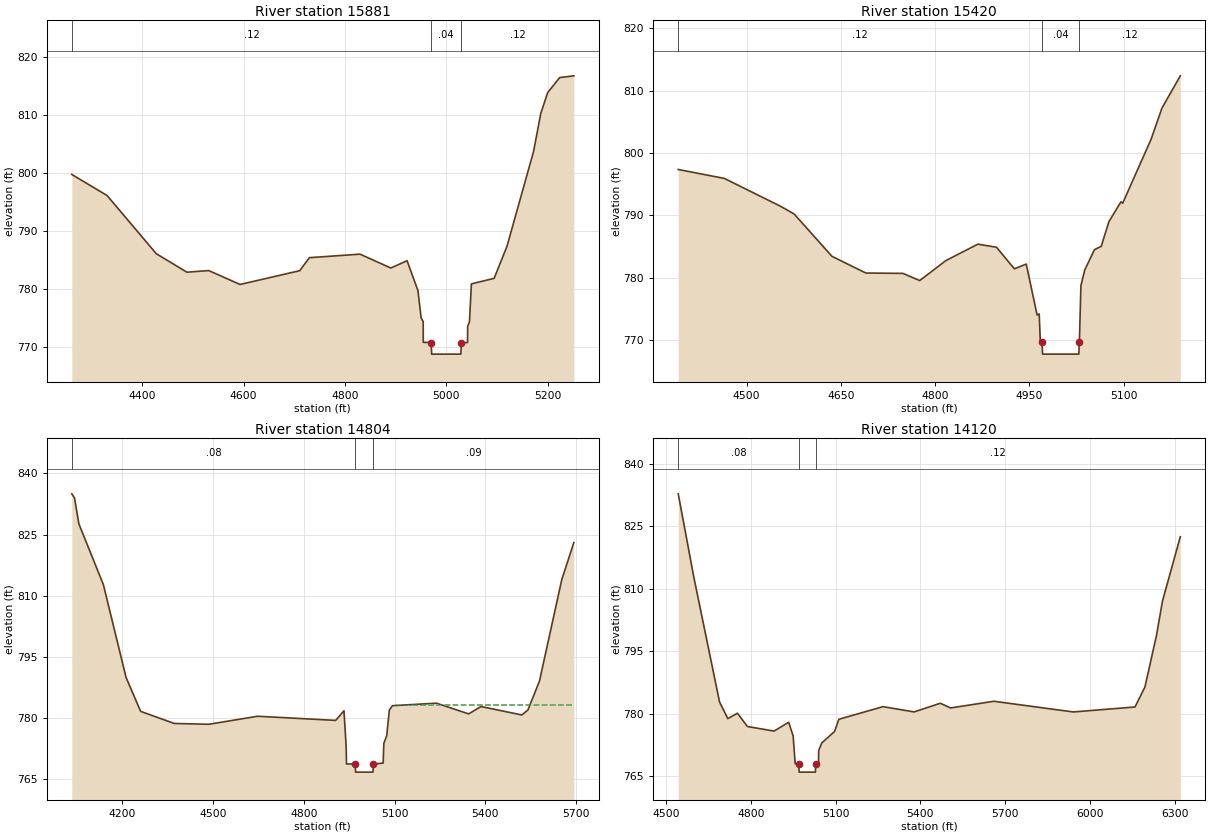
Type RM Length L Ch R = 1,15881,461,461,461
BEGIN DESCRIPTION:
North Little Hunting Creek 27.5
END DESCRIPTION:
XS GIS Cut Line= 4
      1475707.54       837800.59      1475675.72       837623.30
      1475284.82       837079.38      1475143.89       837076.35
#Sta/Elev= 30
  4260.9  799.78  4330.6  796.13  4427.8  786.07  4488.2  782.88  4531.2  783.16
  4593.1  780.76  4710.8  783.14  4729.8  785.39  4829.8  786.00  4890.6  783.60
  4922.6  784.86  4944.1  779.71  4950.4  774.98  4954.5  774.32  4954.6  770.76
  4970.2  770.72  4971.2  768.72  5028.8  768.72  5029.8  770.72  5042.0  770.72
  5042.2  773.47  5045.8  774.33  5049.6  780.86  5094.5  781.82  5119.8  787.34
  5172.3  803.74  5186.6  810.34  5200.1  813.91  5223.9  816.52  5251.8  816.82
#Mann=3,-1,0
  4260.9    0.12       0  4970.2    0.04       0  5029.8    0.12       0
#XS Ineff=2,0
    0.00 4922.60  784.86               0
Permanent Ineff=
       F       F
Bank Sta=4970.2,5029.8
XS Rating Curve= 0
Exp/Cntr=0.3,0.1

Type RM Length L Ch R = 1,15420,616,616,616
BEGIN DESCRIPTION:
North Little Hunting Creek 27.0
END DESCRIPTION:
XS GIS Cut Line= 4
      1475766.47       837790.31      1475776.83       837550.07
      1475727.13       837117.31      1475654.64       837017.90
#Sta/Elev= 30
  4391.3  797.35  4464.7  795.92  4554.0  791.47  4575.8  790.22  4636.0  783.44
  4689.9  780.77  4749.0  780.71  4775.6  779.56  4817.4  782.77  4868.2  785.39
  4897.8  784.90  4926.3  781.44  4945.2  782.20  4962.5  774.05  4965.8  774.22
  4967.6  769.79  4970.2  769.78  4971.2  767.78  5028.8  767.78  5029.8  769.78
  5032.2  778.76  5038.4  781.29  5053.8  784.51  5064.6  785.05  5076.7  788.98
  5095.9  792.17  5098.7  791.95  5143.9  802.19  5161.2  807.18  5190.4  812.35
#Mann=3,-1,0
  4391.3    0.12       0  4970.2    0.04       0  5029.8    0.12       0
#XS Ineff=2,0
    0.00 4868.20  785.39               0
Permanent Ineff=
       F       F
Bank Sta=4970.2,5029.8
XS Rating Curve= 0
Exp/Cntr=0.3,0.1

Type RM Length L Ch R = 1,14804,684,684,684
BEGIN DESCRIPTION:
North Little Hunting Creek 26.5
END DESCRIPTION:
XS GIS Cut Line= 4
      1476683.27       838124.79      1476752.96       837833.90
      1476004.50       836900.60      1475856.01       836830.90
#Sta/Elev= 30
  4033.2  835.01  4042.3  833.99  4056.8  827.63  4137.6  812.77  4212.7  790.00
  4260.8  781.68  4372.0  778.71  4486.1  778.51  4647.6  780.48  4905.5  779.46
  4932.9  781.83  4940.2  772.95  4941.2  768.78  4970.2  768.78  4971.2  766.78
  5028.8  766.78  5029.8  768.78  5062.4  768.99  5064.7  773.83  5074.2  775.71
  5082.8  781.98  5093.1  783.07  5238.6  783.68  5345.0  781.06  5386.0  782.86
  5520.7  780.80  5541.0  782.03  5579.1  789.11  5652.9  813.99  5692.7  823.07
#Mann=3,-1,0
  4033.2    0.08       0  4970.2    0.04       0  5029.8    0.09       0
#XS Ineff=2,0
       0                 5103.90    0.00  783.24
Permanent Ineff=
       F       F
Bank Sta=4970.2,5029.8
XS Rating Curve= 0
Exp/Cntr=0.3,0.1

Type RM Length L Ch R = 1,14120,613,613,613
BEGIN DESCRIPTION:
North Little Hunting Creek 26.0
END DESCRIPTION:
XS GIS Cut Line= 4
      1477339.06       837801.97      1477177.64       837682.83
      1475986.13       836879.52      1475863.10       836818.00
#Sta/Elev= 30
  4543.8  832.84  4599.2  812.70  4689.8  782.81  4719.1  778.79  4753.2  780.09
  4788.4  776.89  4882.6  775.79  4934.3  777.90  4950.1  774.63  4957.4  767.92
  4970.2  767.92  4971.2  765.92  5028.8  765.92  5029.8  767.92  5039.9  767.97
  5040.3  771.09  5051.2  772.93  5096.6  775.69  5111.7  778.63  5267.9  781.66
  5377.9  780.40  5470.4  782.48  5506.8  781.35  5659.6  782.96  5940.5  780.39
  6158.8  781.58  6194.0  786.40  6234.7  798.77  6256.0  807.06  6319.0  822.53
#Mann=3,-1,0
  4543.8    0.08       0  4970.2    0.04       0  5029.8    0.12       0
#XS Ineff=2,0
       0                 5267.90    0.00  781.66
Permanent Ineff=
       F       F
Bank Sta=4970.2,5029.8
XS Rating Curve= 0
Exp/Cntr=0.3,0.1