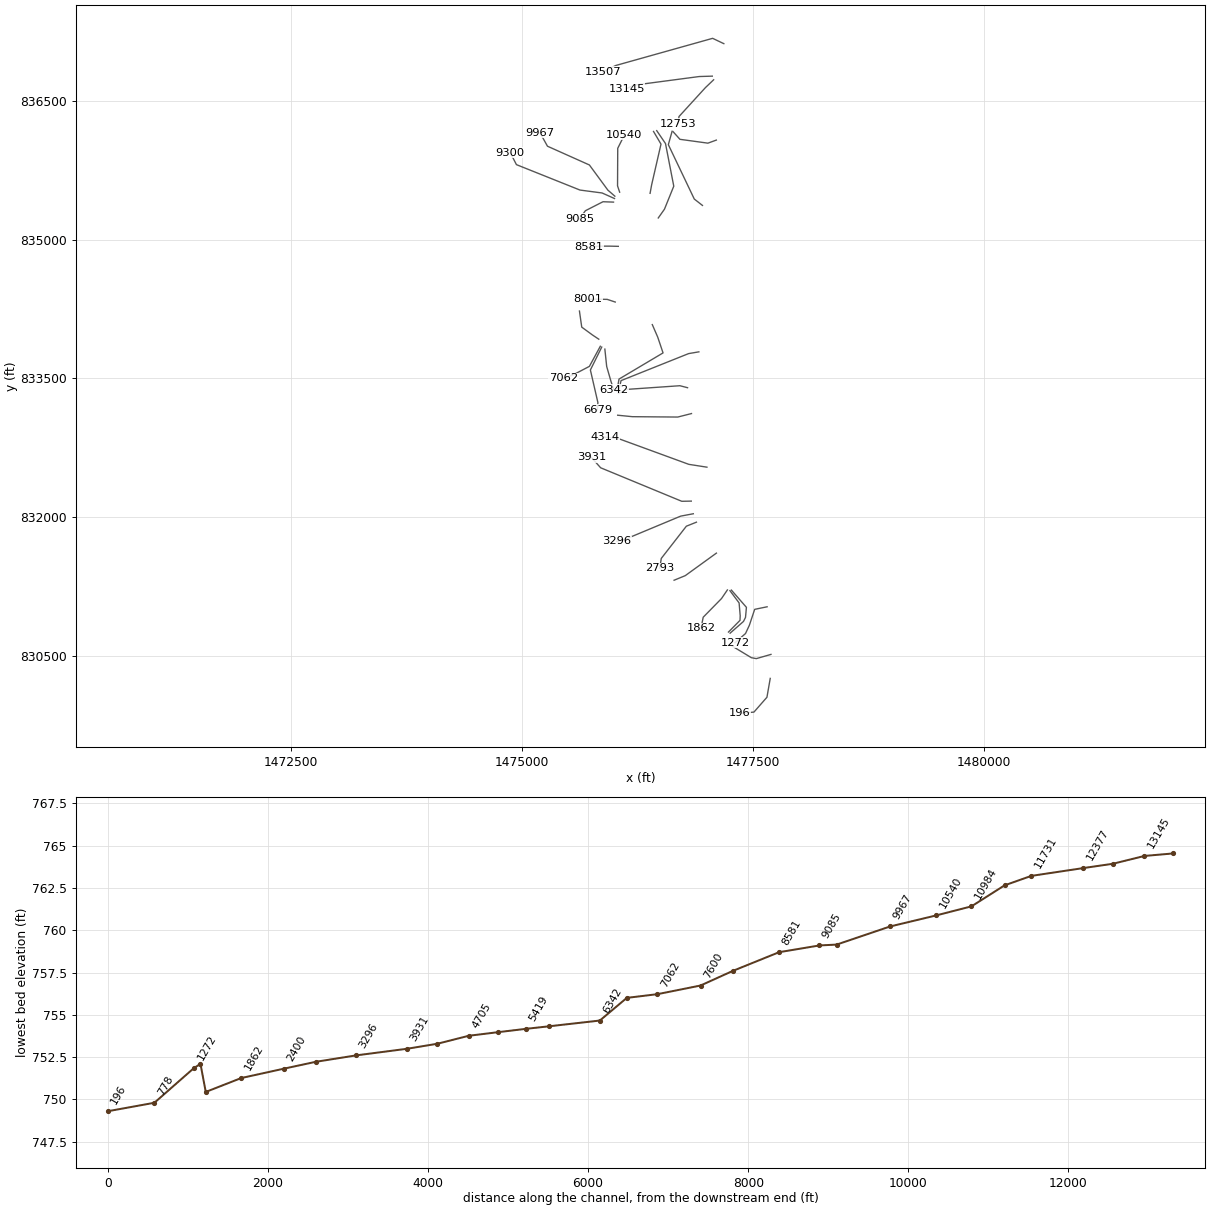
HEC-RAS study North Little Hunting Creek.prj: North Little Hunting Creek Limited Detail Study

--- North Little Hunting Creek.g01 (geometry) --- (continued)

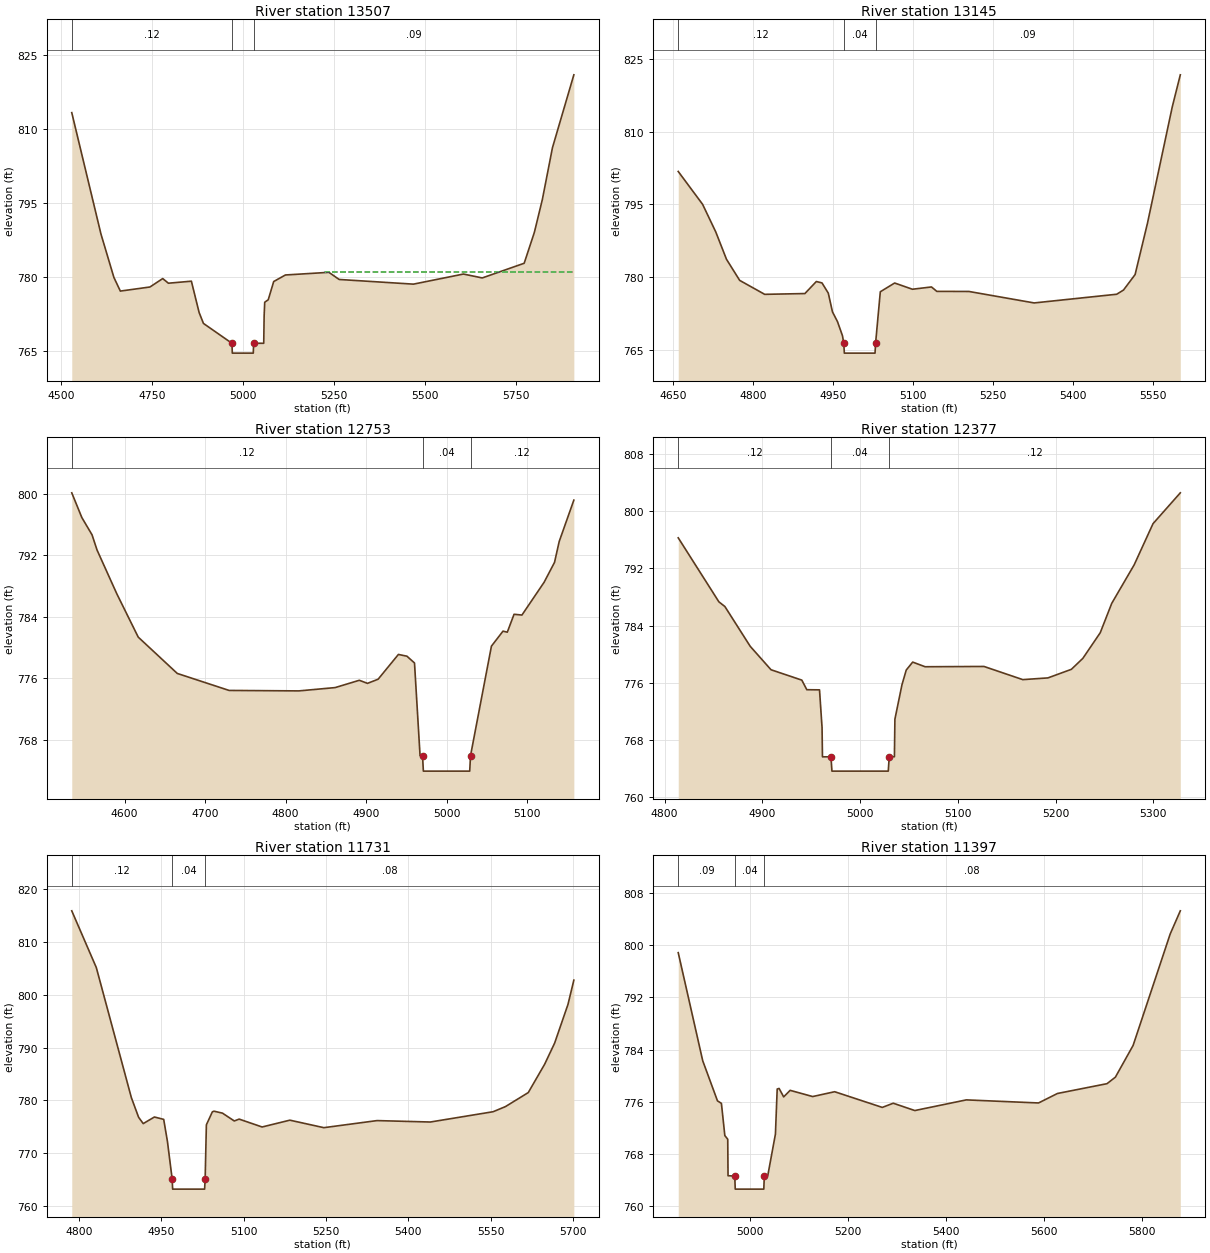
Type RM Length L Ch R = 1,13507,362,362,362
BEGIN DESCRIPTION:
North Little Hunting Creek 25.5
END DESCRIPTION:
XS GIS Cut Line= 4
      1477183.28       837118.76      1477062.04       837176.34
      1476013.59       836882.41      1475874.23       836812.74
#Sta/Elev= 30
  4530.3  813.38  4610.4  788.75  4646.0  779.91  4663.7  777.14  4745.0  777.97
  4780.1  779.68  4795.7  778.74  4858.8  779.15  4880.1  772.78  4892.0  770.57
  4970.2  766.54  4971.2  764.54  5028.8  764.54  5029.8  766.54  5057.5  766.54
  5058.6  772.04  5060.2  774.87  5069.9  775.38  5084.9  779.08  5117.0  780.41
  5236.5  780.95  5264.6  779.50  5468.7  778.55  5606.0  780.60  5657.6  779.81
  5772.8  782.79  5800.8  789.07  5822.7  795.73  5850.5  806.27  5909.2  821.06
#Mann=3,-1,0
  4530.3    0.12       0  4970.2    0.04       0  5029.8    0.09       0
#XS Ineff=2,0
       0                 5226.30    0.00  780.96
Permanent Ineff=
       F       F
Bank Sta=4970.2,5029.8
XS Rating Curve= 0
Exp/Cntr=0.3,0.1

Type RM Length L Ch R = 1,13145,392,392,392
BEGIN DESCRIPTION:
North Hunting Creek 25.0
END DESCRIPTION:
XS GIS Cut Line= 4
      1477058.59       836767.37      1476917.75       836763.23
      1476213.73       836670.05      1476130.89       836632.77
#Sta/Elev= 30
  4659.6  801.78  4705.3  795.02  4730.0  789.34  4750.1  783.71  4774.9  779.36
  4821.8  776.49  4897.2  776.65  4918.7  779.13  4929.3  778.84  4941.1  776.74
  4948.9  772.90  4958.4  770.86  4967.7  767.98  4970.2  766.39  4971.2  764.39
  5028.8  764.39  5029.8  766.39  5038.7  777.02  5065.6  778.82  5098.9  777.54
  5134.7  778.01  5144.7  777.10  5205.0  777.08  5327.3  774.72  5482.2  776.51
  5494.9  777.37  5516.7  780.56  5539.9  791.13  5586.4  815.07  5601.5  821.67
#Mann=3,-1,0
  4659.6    0.12       0  4970.2    0.04       0  5029.8    0.09       0
Bank Sta=4970.2,5029.8
XS Rating Curve= 0
Exp/Cntr=0.3,0.1

Type RM Length L Ch R = 1,12753,376,376,376
BEGIN DESCRIPTION:
North Hunting Creek 24.0
END DESCRIPTION:
XS GIS Cut Line= 4
      1477073.07       836728.04      1476984.01       836643.13
      1476698.26       836330.46      1476687.92       836253.88
#Sta/Elev= 30
  4534.3  800.11  4546.8  796.90  4559.5  794.65  4565.7  792.68  4590.2  787.00
  4616.9  781.35  4665.4  776.63  4729.8  774.42  4816.5  774.36  4861.6  774.79
  4891.6  775.74  4901.8  775.34  4915.0  775.88  4940.2  779.10  4950.8  778.87
  4960.2  777.99  4967.1  765.94  4970.2  765.93  4971.2  763.93  5028.8  763.93
  5029.8  765.93  5055.8  780.18  5070.2  782.13  5075.5  781.99  5083.9  784.32
  5093.7  784.22  5121.3  788.49  5134.2  791.07  5140.0  793.78  5158.2  799.16
#Mann=3,-1,0
  4534.3    0.12       0  4970.2    0.04       0  5029.8    0.12       0
Bank Sta=4970.2,5029.8
XS Rating Curve= 0
Exp/Cntr=0.3,0.1

Type RM Length L Ch R = 1,12377,646,646,646
BEGIN DESCRIPTION:
North Little Hunting Creek 23.0
END DESCRIPTION:
XS GIS Cut Line= 4
      1477102.03       836075.77      1477010.93       836042.64
      1476708.62       836084.05      1476634.08       836166.88
#Sta/Elev= 30
  4814.0  796.28  4855.6  787.33  4861.7  786.68  4887.6  781.12  4908.9  777.84
  4940.4  776.39  4945.5  775.05  4958.5  775.03  4961.1  769.73  4961.5  765.67
  4970.2  765.67  4971.2  763.67  5028.8  763.67  5029.8  765.67  5035.1  765.68
  5035.6  770.93  5042.8  775.73  5047.2  777.80  5053.8  778.91  5066.5  778.26
  5126.7  778.30  5166.4  776.46  5192.1  776.70  5216.1  777.90  5227.8  779.43
  5245.6  783.01  5257.4  787.13  5280.3  792.50  5299.6  798.26  5327.5  802.57
#Mann=3,-1,0
  4814.0    0.12       0  4970.2    0.04       0  5029.8    0.12       0
Bank Sta=4970.2,5029.8
XS Rating Curve= 0
Exp/Cntr=0.3,0.1

Type RM Length L Ch R = 1,11731,334,334,334
BEGIN DESCRIPTION:
North Little Hunting Creek 22.0
END DESCRIPTION:
XS GIS Cut Line= 4
      1476952.06       835368.96      1476863.62       835438.17
      1476583.04       836026.24      1476623.70       836170.95
#Sta/Elev= 30
  4787.2  815.88  4831.9  805.14  4895.7  780.53  4908.9  776.81  4917.3  775.61
  4937.7  776.86  4954.6  776.41  4961.4  772.23  4969.9  765.21  4970.9  763.21
  5029.1  763.21  5030.1  765.21  5032.3  775.38  5043.2  777.84  5046.2  777.96
  5061.6  777.59  5083.1  776.11  5092.0  776.46  5133.8  774.97  5184.3  776.26
  5246.2  774.84  5343.1  776.18  5440.1  775.91  5554.4  777.86  5576.9  778.83
  5618.4  781.48  5648.2  786.84  5666.4  790.84  5690.7  798.16  5701.4  802.76
#Mann=3,-1,0
  4787.2    0.12       0  4969.9    0.04       0  5030.1    0.08       0
Bank Sta=4969.9,5030.1
XS Rating Curve= 0
Exp/Cntr=0.3,0.1

Type RM Length L Ch R = 1,11397,413,413,413
BEGIN DESCRIPTION:
North Little Hunting Creek 21.5
END DESCRIPTION:
XS GIS Cut Line= 5
      1476474.09       835233.43      1476541.17       835328.47
      1476641.77       835577.18      1476552.35       836038.28
      1476457.32       836178.03
#Sta/Elev= 30
  4854.7  798.82  4904.6  782.29  4934.7  776.15  4942.7  775.77  4949.7  770.84
  4955.6  770.28  4956.2  764.70  4969.9  764.65  4970.9  762.65  5029.1  762.65
  5030.1  764.65  5037.1  764.68  5052.8  771.07  5056.4  777.96  5060.3  778.05
  5069.6  776.76  5082.8  777.76  5128.7  776.81  5173.5  777.55  5270.6  775.15
  5292.9  775.79  5336.9  774.67  5441.8  776.30  5589.0  775.83  5627.6  777.28
  5728.6  778.78  5745.7  779.78  5781.8  784.63  5857.4  801.68  5878.0  805.22
#Mann=3,-1,0
  4854.7    0.09       0  4969.9    0.04       0  5030.1    0.08       0
Bank Sta=4969.9,5030.1
XS Rating Curve= 0
Exp/Cntr=0.3,0.1

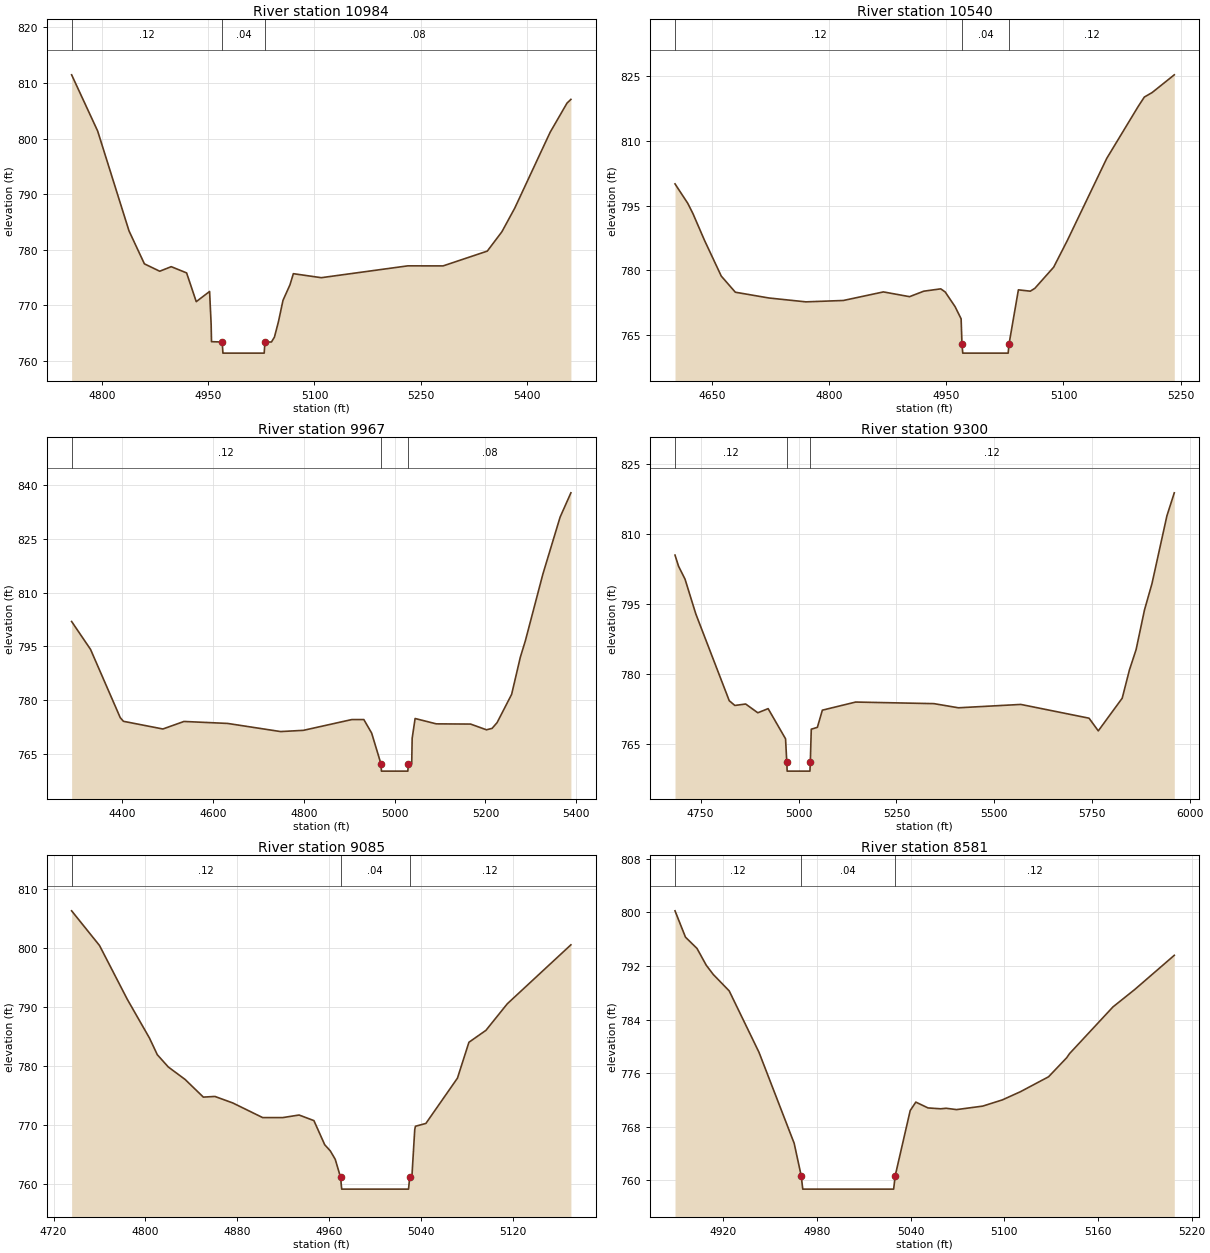
Type RM Length L Ch R = 1,10984,444,444,444
BEGIN DESCRIPTION:
North Hunting Creek 21.0
END DESCRIPTION:
XS GIS Cut Line= 4
      1476385.59       835500.09      1476402.39       835591.92
      1476503.62       836032.29      1476422.89       836168.91
#Sta/Elev= 30
  4757.6  811.47  4794.3  801.36  4838.5  783.40  4860.2  777.47  4881.8  776.14
  4898.0  776.96  4919.7  775.84  4933.3  770.67  4952.1  772.50  4954.3  766.59
  4954.8  763.47  4969.9  763.41  4970.9  761.41  5029.1  761.41  5030.1  763.41
  5039.3  763.41  5043.5  764.28  5049.2  767.07  5055.6  770.91  5065.4  773.69
  5070.2  775.70  5109.6  774.98  5231.6  777.11  5281.3  777.10  5343.6  779.76
  5364.2  783.24  5382.4  787.51  5432.2  801.13  5456.0  806.38  5461.5  807.05
#Mann=3,-1,0
  4757.6    0.12       0  4969.9    0.04       0  5030.1    0.08       0
Bank Sta=4969.9,5030.1
XS Rating Curve= 0
Exp/Cntr=0.3,0.1

Type RM Length L Ch R = 1,10540,573,573,573
BEGIN DESCRIPTION:
North Hunting Creek 20.0
END DESCRIPTION:
XS GIS Cut Line= 4
      1476056.36       835512.57      1476033.59       835580.89
      1476035.66       835986.73      1476108.12       836131.66
#Sta/Elev= 30
  4602.1  800.02  4618.4  795.54  4625.0  793.18  4639.9  786.96  4661.4  778.69
  4679.4  774.96  4722.6  773.62  4769.9  772.73  4817.9  773.05  4869.2  775.03
  4902.7  773.93  4920.9  775.20  4942.7  775.74  4948.4  775.01  4961.1  771.61
  4968.8  768.80  4969.9  762.87  4970.9  760.87  5029.1  760.87  5030.1  762.87
  5042.2  775.51  5057.4  775.20  5063.3  775.86  5087.4  780.75  5104.9  786.92
  5155.4  805.91  5196.1  818.04  5203.6  820.10  5213.6  821.15  5242.0  825.25
#Mann=3,-1,0
  4602.1    0.12       0  4969.9    0.04       0  5030.1    0.12       0
Bank Sta=4969.9,5030.1
XS Rating Curve= 0
Exp/Cntr=0.3,0.1

Type RM Length L Ch R = 1,9967,667,667,667
BEGIN DESCRIPTION:
North Hunting Creek 19.0
END DESCRIPTION:
XS GIS Cut Line= 5
      1476004.57       835469.09      1475929.24       835534.26
      1475729.20       835806.59      1475275.73       836009.51
      1475194.99       836154.42
#Sta/Elev= 30
  4288.2  801.94  4329.8  794.18  4395.3  775.14  4402.4  774.11  4489.3  771.97
  4535.8  774.07  4631.8  773.52  4748.7  771.25  4798.8  771.59  4905.7  774.60
  4932.1  774.60  4949.3  770.84  4969.9  762.22  4970.9  760.22  5029.1  760.22
  5030.1  762.22  5037.6  762.22  5038.6  769.37  5045.1  774.89  5091.8  773.40
  5167.4  773.34  5202.4  771.74  5214.8  772.15  5225.7  773.74  5257.8  781.63
  5276.9  791.96  5288.1  796.59  5326.6  815.14  5364.6  831.04  5388.4  837.82
#Mann=3,-1,0
  4288.2    0.12       0  4969.9    0.04       0  5030.1    0.08       0
Bank Sta=4969.9,5030.1
XS Rating Curve= 0
Exp/Cntr=0.3,0.1

Type RM Length L Ch R = 1,9300,215,215,215
BEGIN DESCRIPTION:
North Little Hunting Creek 18.5
END DESCRIPTION:
XS GIS Cut Line= 5
      1476000.64       835443.76      1475866.76       835503.65
      1475627.12       835535.37      1474939.93       835810.25
      1474872.97       835940.63
#Sta/Elev= 30
  4684.5  805.47  4693.4  803.11  4710.1  800.31  4737.6  792.86  4823.0  774.25
  4837.3  773.23  4864.9  773.54  4896.0  771.66  4922.3  772.55  4966.8  766.08
  4969.9  761.15  4970.9  759.15  5029.1  759.15  5030.1  761.15  5032.5  768.14
  5048.1  768.54  5060.8  772.22  5145.8  773.96  5345.8  773.62  5408.3  772.73
  5567.7  773.45  5741.9  770.50  5765.5  767.78  5826.6  774.79  5845.1  780.86
  5862.1  785.21  5883.5  793.71  5902.6  799.35  5940.8  813.90  5959.6  818.82
#Mann=3,-1,0
  4684.5    0.12       0  4969.9     0.4       0  5030.1    0.12       0
Bank Sta=4969.9,5030.1
XS Rating Curve= 0
Exp/Cntr=0.3,0.1

Type RM Length L Ch R = 1,9085,504,504,504
BEGIN DESCRIPTION:
North Hunting Creek 18.0
END DESCRIPTION:
XS GIS Cut Line= 4
      1475990.11       835404.88      1475876.22       835409.02
      1475685.72       835311.70      1475623.57       835224.70
#Sta/Elev= 30
  4735.7  806.34  4760.0  800.45  4784.2  791.31  4803.5  784.74  4810.3  781.92
  4819.9  779.83  4834.5  777.72  4850.4  774.72  4860.5  774.83  4876.0  773.73
  4902.1  771.24  4919.5  771.24  4933.8  771.68  4946.7  770.73  4956.1  766.64
  4961.0  765.58  4965.3  764.15  4969.9  761.10  4970.9  759.10  5029.1  759.10
  5030.1  761.10  5032.0  761.10  5034.5  769.19  5035.1  769.77  5044.2  770.25
  5071.7  777.94  5081.7  784.03  5096.5  786.05  5115.1  790.56  5170.5  800.57
#Mann=3,-1,0
  4735.7    0.12       0  4969.9    0.04       0  5030.1    0.12       0
Bank Sta=4969.9,5030.1
XS Rating Curve= 0
Exp/Cntr=0.3,0.1

Type RM Length L Ch R = 1,8581,580,580,580
BEGIN DESCRIPTION:
North Hunting Creek 17.0
END DESCRIPTION:
XS GIS Cut Line= 4
      1476041.91       834926.56      1475948.69       834928.63
      1475828.59       834928.63      1475722.96       834916.21
#Sta/Elev= 27
  4889.1  800.24  4895.8  796.31  4903.2  794.62  4909.1  792.12  4913.6  790.74
  4923.8  788.29  4942.9  779.11  4965.4  765.54  4969.9  760.70  4970.9  758.70
  5029.1  758.70  5030.1  760.70  5039.7  770.43  5043.3  771.69  5051.1  770.82
  5059.2  770.69  5062.7  770.77  5069.4  770.57  5086.1  771.09  5098.6  772.01
  5110.2  773.23  5128.3  775.47  5139.9  778.31  5141.7  778.92  5169.5  785.89
  5183.4  788.48  5208.8  793.60
#Mann=3,-1,0
  4889.1    0.12       0  4969.9    0.04       0  5030.1    0.12       0
Bank Sta=4969.9,5030.1
XS Rating Curve= 0
Exp/Cntr=0.3,0.1

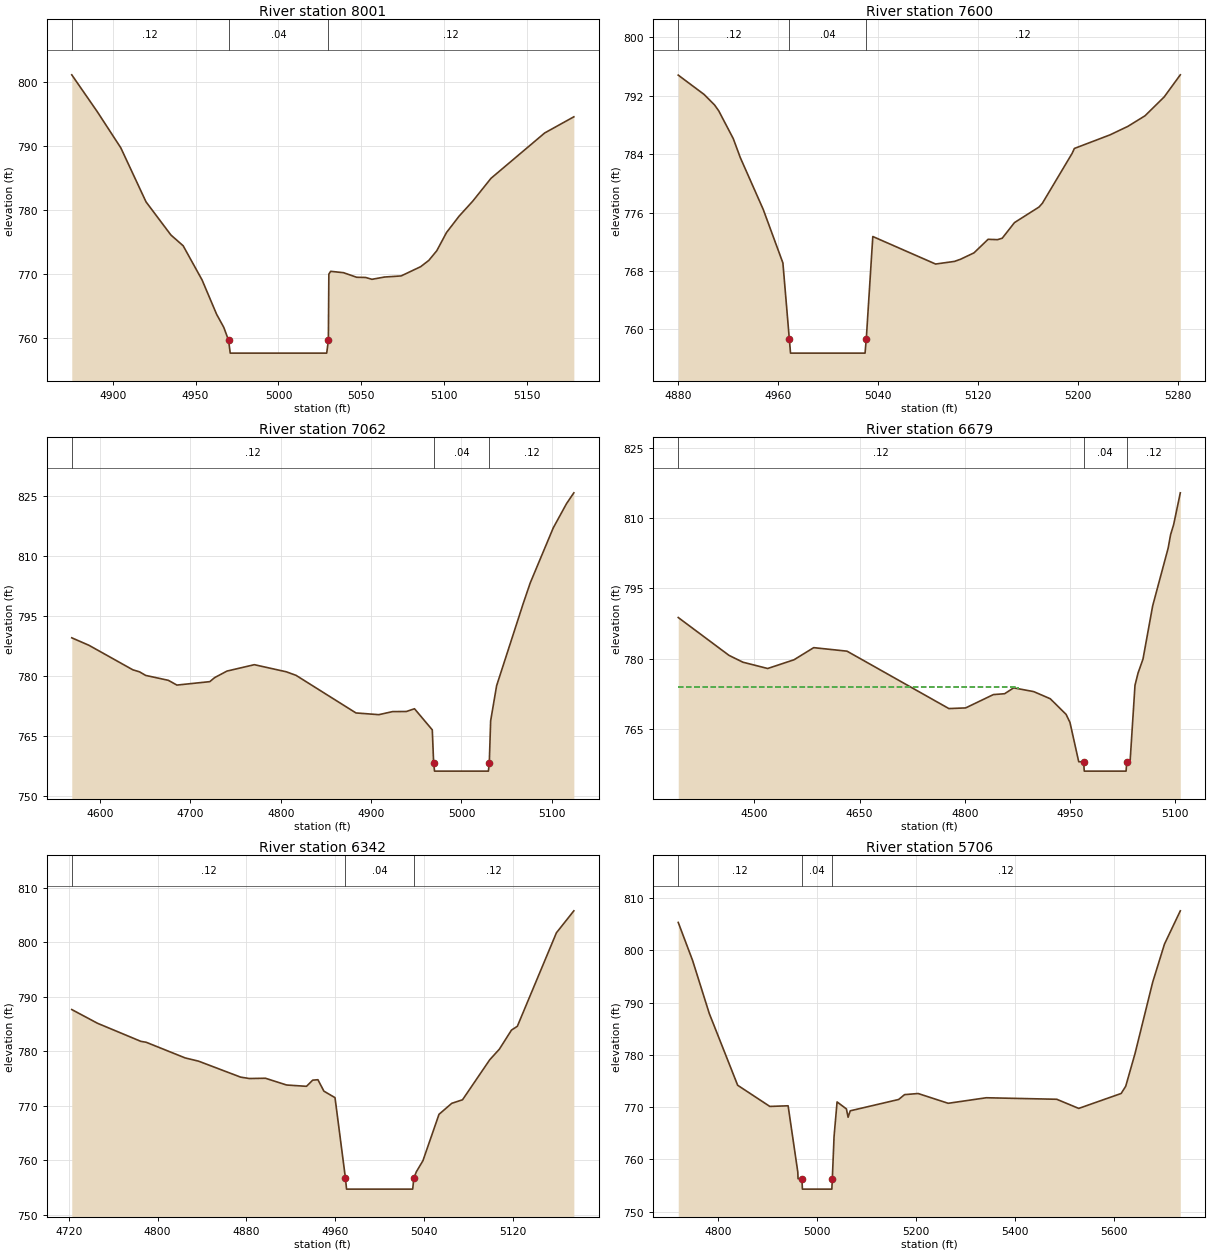
Type RM Length L Ch R = 1,8001,401,401,401
BEGIN DESCRIPTION:
North Hunting Creek 16.0
END DESCRIPTION:
XS GIS Cut Line= 4
      1476008.75       834324.00      1475921.77       834352.99
      1475797.53       834355.06      1475710.60       834352.99
#Sta/Elev= 30
  4875.3  801.14  4890.8  795.33  4904.9  789.71  4920.1  781.26  4935.1  776.08
  4942.5  774.39  4953.9  769.05  4962.7  763.66  4967.0  761.63  4969.9  759.59
  4970.9  757.59  5029.1  757.59  5030.1  759.59  5030.4  769.96  5031.5  770.39
  5039.2  770.18  5047.2  769.46  5052.6  769.43  5056.4  769.14  5064.0  769.50
  5074.0  769.67  5085.8  771.12  5090.7  772.10  5095.5  773.61  5101.4  776.47
  5109.0  779.03  5117.3  781.40  5128.2  784.94  5160.6  792.04  5178.2  794.57
#Mann=3,-1,0
  4875.3    0.12       0  4969.9    0.04       0  5030.1    0.12       0
Bank Sta=4969.9,5030.1
XS Rating Curve= 0
Exp/Cntr=0.3,0.1

Type RM Length L Ch R = 1,7600,538,538,538
BEGIN DESCRIPTION:
North Hunting Creek 15.0
END DESCRIPTION:
XS GIS Cut Line= 4
      1475830.65       833922.31      1475762.33       833967.85
      1475646.38       834052.75      1475621.53       834226.66
#Sta/Elev= 30
  4880.4  794.83  4901.1  792.18  4909.5  790.73  4912.8  789.93  4924.4  786.13
  4930.0  783.54  4948.4  776.41  4964.1  769.09  4969.2  758.73  4970.2  756.73
  5029.8  756.73  5030.8  758.73  5036.0  772.71  5086.2  768.94  5101.3  769.30
  5106.2  769.60  5116.9  770.47  5128.2  772.33  5135.7  772.28  5139.5  772.48
  5149.3  774.62  5168.9  776.75  5171.6  777.27  5195.4  784.11  5197.2  784.78
  5225.8  786.65  5240.0  787.81  5253.7  789.26  5269.0  791.84  5281.9  794.87
#Mann=3,-1,0
  4880.4    0.12       0  4969.2    0.04       0  5030.8    0.12       0
Bank Sta=4969.2,5030.8
XS Rating Curve= 0
Exp/Cntr=0.3,0.1

Type RM Length L Ch R = 1,7062,383,383,383
BEGIN DESCRIPTION:
North Hunting Creek 14.0
END DESCRIPTION:
XS GIS Cut Line= 4
      1475847.24       833845.70      1475729.20       833628.27
      1475546.98       833533.02      1475449.68       833499.89
#Sta/Elev= 30
  4568.6  789.56  4587.8  787.67  4636.2  781.56  4643.7  781.04  4650.4  780.16
  4675.5  778.93  4685.0  777.74  4721.4  778.60  4726.8  779.61  4740.4  781.24
  4770.7  782.84  4806.1  781.06  4816.9  780.17  4883.2  770.77  4908.6  770.34
  4923.8  771.11  4939.0  771.13  4948.0  771.82  4967.7  766.54  4969.2  758.22
  4970.2  756.22  5029.8  756.22  5030.8  758.22  5032.3  768.80  5038.9  777.58
  5068.3  798.10  5076.1  803.28  5101.6  817.05  5116.3  823.12  5124.4  825.82
#Mann=3,-1,0
  4568.6    0.12       0  4969.2    0.04       0  5030.8    0.12       0
Bank Sta=4969.2,5030.8
XS Rating Curve= 0
Exp/Cntr=0.3,0.1

Type RM Length L Ch R = 1,6679,337,337,337
BEGIN DESCRIPTION:
North Little Hunting Creek 13.0
END DESCRIPTION:
XS GIS Cut Line= 4
      1475862.67       833836.84      1475739.87       833589.27
      1475821.09       833236.67      1475815.15       833159.38
#Sta/Elev= 30
  4391.4  788.78  4463.8  780.70  4483.5  779.25  4518.9  777.90  4556.4  779.76
  4584.5  782.35  4632.0  781.60  4777.2  769.35  4801.1  769.49  4840.6  772.33
  4856.7  772.52  4869.5  773.77  4898.1  772.97  4921.7  771.45  4944.3  768.11
  4949.8  766.40  4962.3  758.00  4969.2  758.00  4970.2  756.00  5029.8  756.00
  5030.8  758.00  5035.5  758.00  5042.5  774.32  5046.9  776.95  5053.9  779.91
  5067.7  791.27  5089.8  803.61  5093.2  806.43  5097.6  808.61  5107.1  815.39
#Mann=3,-1,0
  4391.4    0.12       0  4969.2    0.04       0  5030.8    0.12       0
#XS Ineff=2,0
    0.00 4875.30  773.92               0
Permanent Ineff=
       F       F
Bank Sta=4969.2,5030.8
XS Rating Curve= 0
Exp/Cntr=0.3,0.1

Type RM Length L Ch R = 1,6342,636,636,636
BEGIN DESCRIPTION:
North Little Hunting Creek 12.0
END DESCRIPTION:
XS GIS Cut Line= 4
      1475896.37       833815.07      1475916.17       833626.91
      1475963.72       833462.49      1475993.42       833375.37
#Sta/Elev= 30
  4722.6  787.62  4745.8  785.10  4784.9  781.78  4789.6  781.62  4824.8  778.74
  4836.8  778.15  4874.7  775.22  4882.6  774.96  4897.1  775.01  4916.2  773.77
  4934.1  773.53  4939.7  774.66  4944.4  774.74  4949.8  772.64  4959.8  771.45
  4969.2  756.66  4970.2  754.66  5029.8  754.66  5030.8  756.66  5033.1  757.85
  5039.0  759.87  5053.5  768.39  5065.0  770.41  5074.7  771.06  5099.2  778.40
  5107.9  780.35  5118.8  783.85  5124.1  784.55  5159.3  801.71  5175.0  805.74
#Mann=3,-1,0
  4722.6    0.12       0  4969.2    0.04       0  5030.8    0.12       0
Bank Sta=4969.2,5030.8
XS Rating Curve= 0
Exp/Cntr=0.3,0.1

Type RM Length L Ch R = 1,5706,287,287,287
BEGIN DESCRIPTION:
North Little Hunting Creek 11.0
END DESCRIPTION:
XS GIS Cut Line= 5
      1476409.52       834079.89      1476468.44       833944.05
      1476525.72       833773.86      1476049.51       833490.75
      1476026.60       833358.17
#Sta/Elev= 30
  4718.9  805.37  4748.0  798.08  4781.7  787.95  4839.2  774.20  4904.3  770.15
  4941.3  770.27  4960.9  757.59  4961.4  756.32  4969.2  756.32  4970.2  754.32
  5029.8  754.32  5030.8  756.32  5034.3  764.38  5040.4  771.01  5059.3  769.67
  5062.7  768.08  5067.0  769.31  5165.0  771.48  5177.0  772.41  5204.4  772.62
  5265.3  770.75  5342.4  771.81  5485.0  771.52  5529.5  769.77  5615.4  772.63
  5624.6  774.01  5643.5  780.29  5679.1  793.90  5703.0  801.21  5735.1  807.59
#Mann=3,-1,0
  4718.9    0.12       0  4969.2    0.04       0  5030.8    0.12       0
Bank Sta=4969.2,5030.8
XS Rating Curve= 0
Exp/Cntr=0.3,0.1

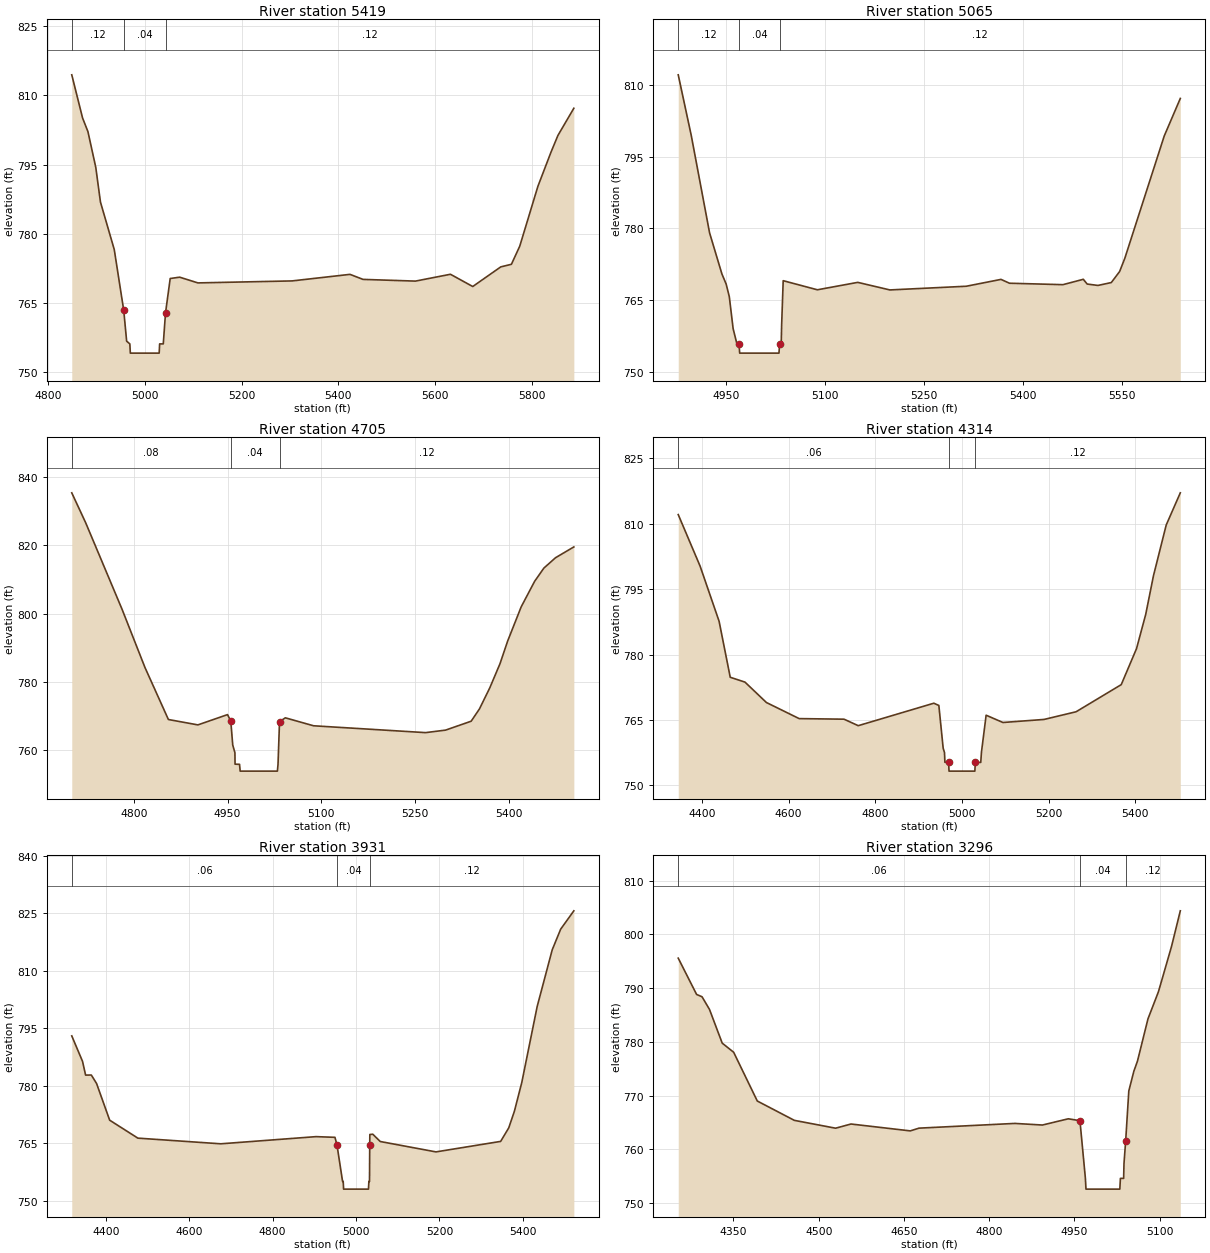
Type RM Length L Ch R = 1,5419,354,354,354
BEGIN DESCRIPTION:
North Little Hunting Creek 10.0
END DESCRIPTION:
XS GIS Cut Line= 4
      1476913.22       833785.43      1476801.74       833766.21
      1476071.45       833474.10      1476040.97       833339.68
#Sta/Elev= 30
  4849.2  814.45  4871.5  805.11  4882.6  802.15  4898.8  794.42  4908.5  786.89
  4937.0  776.61  4956.6  763.43  4962.6  756.76  4969.2  756.17  4970.2  754.17
  5029.8  754.17  5030.8  756.17  5038.3  756.17  5042.9  762.86  5052.6  770.33
  5072.2  770.62  5109.8  769.38  5304.4  769.81  5424.1  771.23  5451.2  770.14
  5559.4  769.77  5631.7  771.25  5677.8  768.60  5735.7  772.85  5757.7  773.41
  5774.9  777.33  5812.4  790.29  5839.3  797.65  5853.8  801.32  5886.7  807.21
#Mann=3,-1,0
  4849.2    0.12       0  4956.6    0.04       0  5042.9    0.12       0
Bank Sta=4956.6,5042.9
XS Rating Curve= 0
Exp/Cntr=0.3,0.1

Type RM Length L Ch R = 1,5065,360,360,360
BEGIN DESCRIPTION:
North Little Hunting Creek 9.5
END DESCRIPTION:
XS GIS Cut Line= 4
      1476790.73       833397.54      1476707.97       833419.00
      1476131.84       833379.16      1476044.49       833334.72
#Sta/Elev= 30
  4877.1  812.06  4896.8  799.43  4924.6  779.08  4943.3  770.50  4949.7  768.40
  4954.5  765.76  4960.3  759.08  4965.9  755.98  4969.2  755.97  4970.2  753.97
  5029.8  753.97  5030.8  755.97  5033.2  755.97  5033.8  759.71  5036.2  769.09
  5088.0  767.19  5149.2  768.74  5197.9  767.16  5313.7  767.93  5366.3  769.36
  5379.2  768.56  5460.2  768.26  5491.1  769.38  5496.9  768.39  5513.3  768.10
  5533.5  768.70  5546.1  771.00  5554.0  773.77  5613.7  799.28  5638.1  807.13
#Mann=3,-1,0
  4877.1    0.12       0  4969.2    0.04       0  5030.8    0.12       0
Bank Sta=4969.2,5030.8
XS Rating Curve= 0
Exp/Cntr=0.3,0.1

Type RM Length L Ch R = 1,4705,391,391,391
BEGIN DESCRIPTION:
North Little Hunting Creek 9.0
END DESCRIPTION:
XS GIS Cut Line= 4
      1476833.33       833117.81      1476684.77       833080.17
      1476193.50       833084.13      1476035.03       833099.98
#Sta/Elev= 30
  4700.6  835.45  4723.0  826.61  4781.2  801.23  4817.8  784.18  4855.3  768.91
  4902.5  767.33  4950.0  770.35  4955.2  768.43  4958.3  761.43  4961.8  759.17
  4962.0  755.80  4969.2  755.76  4970.2  753.76  5029.8  753.76  5030.8  755.76
  5033.2  768.27  5042.5  769.41  5087.7  767.07  5267.0  765.06  5299.1  765.80
  5340.0  768.41  5353.3  772.02  5369.9  778.23  5386.1  785.26  5398.4  791.92
  5420.1  801.98  5441.6  809.47  5456.4  813.35  5475.1  816.40  5504.4  819.57
#Mann=3,-1,0
  4700.6    0.08       0  4955.2    0.04       0  5033.2    0.12       0
Bank Sta=4955.2,5033.2
XS Rating Curve= 0
Exp/Cntr=0.3,0.1

Type RM Length L Ch R = 1,4314,383,383,383
BEGIN DESCRIPTION:
North Little Hunting Creek 8.5
END DESCRIPTION:
XS GIS Cut Line= 4
      1477000.60       832537.94      1476804.51       832568.58
      1476050.62       832844.39      1475894.33       832862.78
#Sta/Elev= 30
  4345.3  812.11  4395.9  800.26  4439.6  787.65  4465.3  774.81  4499.3  773.70
  4548.8  769.02  4624.4  765.33  4727.9  765.20  4760.7  763.71  4935.1  768.86
  4946.7  768.35  4956.7  758.53  4959.7  757.56  4960.7  755.32  4969.2  755.29
  4970.2  753.29  5029.8  753.29  5030.8  755.29  5043.4  755.29  5045.0  757.62
  5055.8  766.11  5094.6  764.44  5189.4  765.14  5263.4  766.90  5367.6  773.12
  5402.9  781.39  5424.1  789.24  5442.0  798.11  5471.4  809.73  5503.9  817.10
#Mann=3,-1,0
  4345.3    0.06       0  4969.2    0.04       0  5030.8    0.12       0
Bank Sta=4969.2,5030.8
XS Rating Curve= 0
Exp/Cntr=0.3,0.1

Type RM Length L Ch R = 1,3931,635,635,635
BEGIN DESCRIPTION:
North Little Hunting Creek 8.0
END DESCRIPTION:
XS GIS Cut Line= 4
      1476831.33       832170.93      1476728.35       832168.95
      1475850.80       832531.46      1475749.76       832644.38
#Sta/Elev= 30
  4318.3  792.96  4344.1  786.32  4351.5  782.73  4365.2  782.75  4377.8  780.54
  4409.2  770.97  4476.8  766.29  4675.7  764.81  4904.0  766.68  4949.4  766.50
  4954.2  764.57  4967.7  755.00  4969.2  754.99  4970.2  752.99  5029.8  752.99
  5030.8  754.99  5032.3  754.99  5032.8  764.41  5033.1  767.24  5040.2  767.31
  5058.0  765.41  5191.7  762.70  5346.8  765.44  5366.2  768.97  5379.7  773.29
  5397.4  780.77  5434.4  800.64  5470.5  815.43  5490.8  820.81  5522.3  825.58
#Mann=3,-1,0
  4318.3    0.06       0  4954.2    0.04       0  5032.8    0.12       0
Bank Sta=4954.2,5032.8
XS Rating Curve= 0
Exp/Cntr=0.3,0.1

Type RM Length L Ch R = 1,3296,503,503,503
BEGIN DESCRIPTION:
North Little Hunting Creek 7.0
END DESCRIPTION:
XS GIS Cut Line= 4
      1476853.18       832034.25      1476716.47       832008.50
      1476118.23       831758.90      1476025.15       831735.14
#Sta/Elev= 30
  4252.8  795.59  4285.1  788.84  4294.7  788.40  4307.8  786.05  4330.2  779.77
  4350.3  778.08  4391.9  769.00  4457.1  765.40  4529.7  763.94  4556.8  764.72
  4661.1  763.44  4676.4  763.95  4845.2  764.83  4893.6  764.53  4939.1  765.69
  4959.6  765.34  4969.2  754.60  4970.2  752.60  5029.8  752.60  5030.8  754.60
  5036.5  754.60  5037.1  757.35  5040.1  761.63  5045.6  770.88  5054.5  774.56
  5060.8  776.42  5079.3  784.29  5097.7  789.33  5120.7  797.75  5136.2  804.40
#Mann=3,-1,0
  4252.8    0.06       0  4959.6    0.04       0  5040.1    0.12       0
Bank Sta=4959.6,5040.1
XS Rating Curve= 0
Exp/Cntr=0.3,0.1

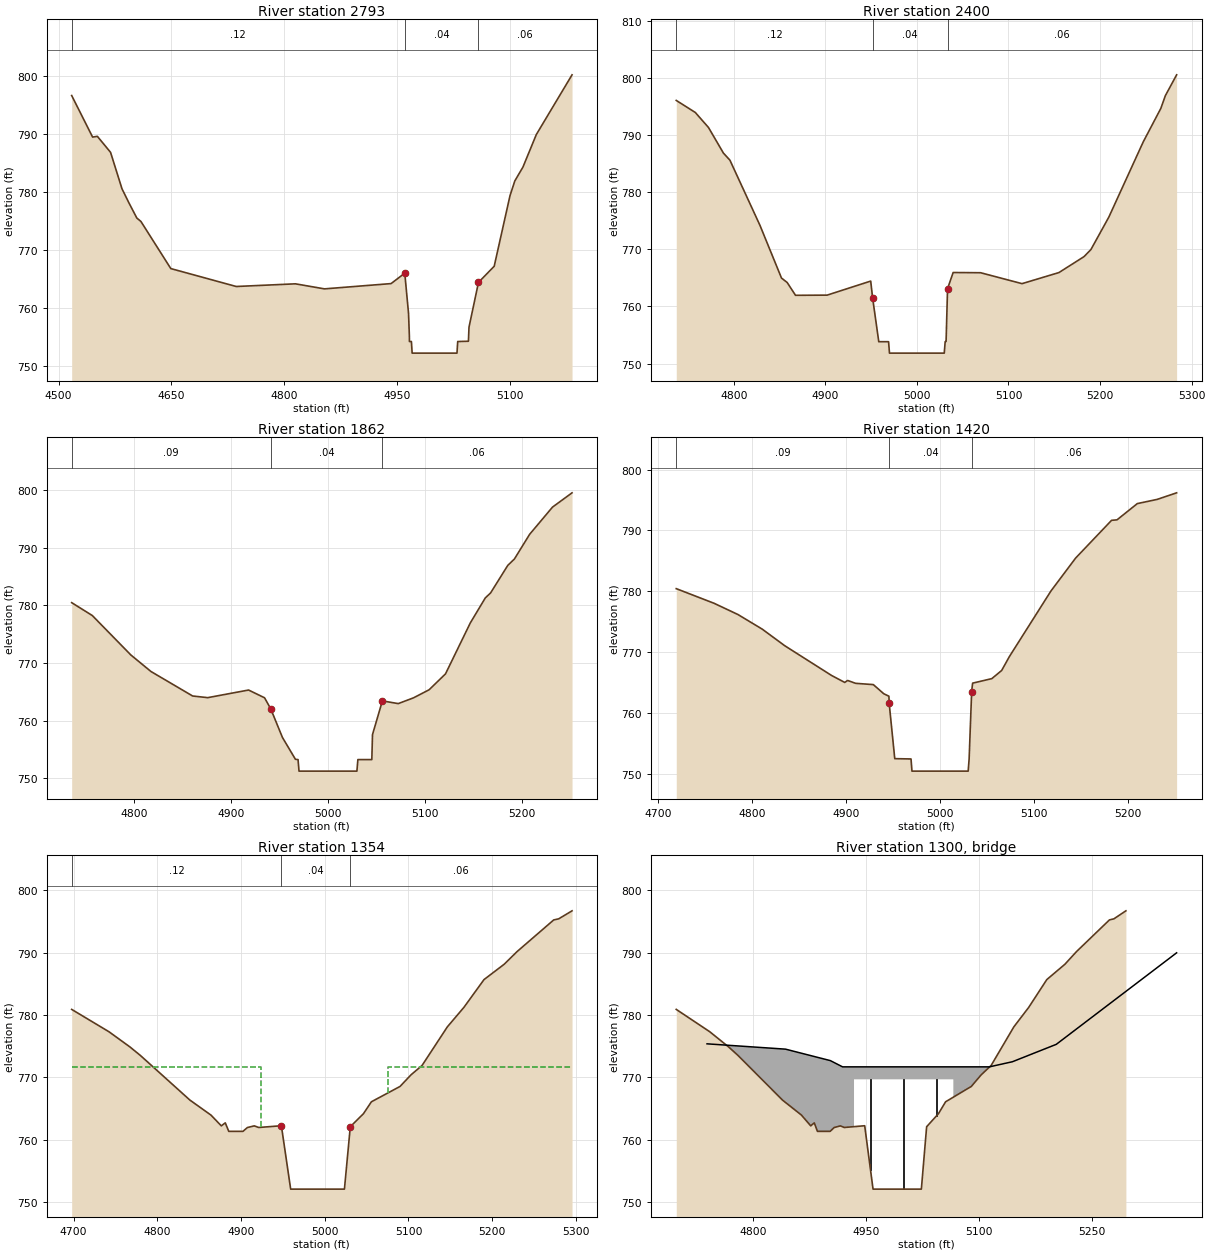
Type RM Length L Ch R = 1,2793,393,393,393
BEGIN DESCRIPTION:
North Little Hunting Creek 6.0
END DESCRIPTION:
XS GIS Cut Line= 4
      1476886.84       831943.13      1476777.87       831899.54
      1476506.49       831550.90      1476490.65       831445.96
#Sta/Elev= 30
  4517.5  796.64  4545.3  789.48  4551.7  789.60  4569.2  786.84  4584.4  780.56
  4593.7  778.11  4604.1  775.52  4609.6  774.92  4649.3  766.80  4736.3  763.71
  4815.0  764.17  4853.6  763.30  4942.2  764.21  4960.4  766.01  4965.4  759.06
  4966.5  755.21  4966.6  754.22  4969.2  754.22  4970.2  752.22  5029.8  752.22
  5030.8  754.22  5045.0  754.27  5045.8  756.70  5058.4  764.42  5079.3  767.20
  5100.3  779.37  5106.7  781.91  5117.5  784.30  5135.3  789.91  5182.8  800.21
#Mann=3,-1,0
  4517.5    0.12       0  4960.4    0.04       0  5058.4    0.06       0
Bank Sta=4960.4,5058.4
XS Rating Curve= 0
Exp/Cntr=0.3,0.1

Type RM Length L Ch R = 1,2400,538,538,538
BEGIN DESCRIPTION:
North Little Hunting Creek 5.0
END DESCRIPTION:
XS GIS Cut Line= 4
      1477102.77       831608.37      1477009.64       831541.00
      1476765.99       831364.70      1476645.13       831315.17
#Sta/Elev= 30
  4737.3  796.05  4758.1  793.94  4772.5  791.31  4788.8  786.83  4795.9  785.59
  4828.7  774.18  4852.2  764.96  4858.4  764.18  4867.5  761.94  4902.0  761.97
  4949.6  764.43  4951.7  761.46  4958.4  753.82  4969.1  753.82  4970.1  751.82
  5029.9  751.82  5030.9  753.82  5031.9  753.86  5033.5  763.09  5039.6  765.93
  5069.6  765.89  5114.8  763.98  5155.1  765.92  5182.5  768.71  5190.0  769.94
  5209.6  775.63  5247.2  788.81  5266.4  794.67  5271.3  796.88  5283.6  800.53
#Mann=3,-1,0
  4737.3    0.12       0  4951.7    0.04       0  5033.5    0.06       0
Bank Sta=4951.7,5033.5
XS Rating Curve= 0
Exp/Cntr=0.3,0.1

Type RM Length L Ch R = 1,1862,442,442,442
BEGIN DESCRIPTION:
North Little Hunting Creek 4.0
END DESCRIPTION:
XS GIS Cut Line= 4
      1477221.61       831210.20      1477158.21       831117.08
      1476960.12       830915.03      1476936.35       830796.20
#Sta/Elev= 30
  4735.3  780.45  4756.6  778.22  4796.4  771.39  4817.2  768.52  4860.2  764.28
  4875.8  763.99  4918.0  765.31  4934.5  763.97  4940.9  762.05  4953.0  757.09
  4966.4  753.31  4969.1  753.26  4970.1  751.26  5029.9  751.26  5030.9  753.26
  5045.3  753.26  5046.0  757.59  5056.2  763.43  5072.6  762.96  5088.4  763.96
  5104.5  765.36  5121.4  768.11  5147.0  776.93  5162.5  781.27  5168.0  782.14
  5185.7  786.90  5192.6  788.02  5208.3  792.29  5231.9  797.00  5252.1  799.48
#Mann=3,-1,0
  4735.3    0.09       0  4940.9    0.04       0  5056.2    0.06       0
Bank Sta=4940.9,5056.2
XS Rating Curve= 0
Exp/Cntr=0.3,0.1

Type RM Length L Ch R = 1,1420,66,66,66
BEGIN DESCRIPTION:
 North Little Hunting Creek 3.0
END DESCRIPTION:
XS GIS Cut Line= 5
      1477249.35       831202.23      1477348.38       831069.54
      1477360.26       830930.88      1477358.28       830881.35
      1477233.49       830754.58
#Sta/Elev= 30
  4719.4  780.43  4759.7  778.02  4785.0  776.18  4810.8  773.78  4834.8  771.05
  4884.6  766.16  4898.6  765.02  4901.7  765.34  4910.2  764.87  4929.0  764.66
  4940.1  763.16  4945.6  762.75  4945.8  761.68  4951.8  752.49  4969.1  752.44
  4970.1  750.44  5029.9  750.44  5030.9  752.44  5033.6  763.52  5034.6  764.90
  5055.0  765.64  5065.5  766.98  5073.7  769.26  5117.9  780.04  5144.2  785.46
  5182.4  791.66  5188.2  791.74  5209.8  794.41  5230.9  795.10  5251.6  796.18
#Mann=3,-1,0
  4719.4    0.09       0  4945.8    0.04       0  5033.6    0.06       0
Bank Sta=4945.8,5033.6
XS Rating Curve= 0
Exp/Cntr=0.5,0.3

Type RM Length L Ch R = 1,1354,82,82,82
BEGIN DESCRIPTION:
Hunting Creek Rd - US
END DESCRIPTION:
XS GIS Cut Line= 5
      1477265.19       831208.19      1477427.62       831022.00
      1477417.71       830913.05      1477395.92       830869.47
      1477251.33       830742.70
#Sta/Elev= 30
  4697.8  780.91  4742.3  777.33  4767.3  774.90  4779.9  773.52  4839.0  766.37
  4864.1  763.97  4876.5  762.24  4881.2  762.72  4885.4  761.36  4902.3  761.36
  4907.6  761.97  4915.8  762.24  4921.1  761.98  4948.2  762.26  4959.3  752.10
  5023.5  752.10  5030.5  762.10  5046.2  764.19  5055.7  766.10  5089.9  768.56
  5103.0  770.42  5116.2  771.92  5146.4  778.11  5166.2  781.24  5190.2  785.69
  5214.2  788.14  5229.7  790.18  5273.4  795.25  5279.4  795.43  5295.3  796.71
#Mann=3,-1,0
  4697.8    0.12       0  4948.2    0.04       0  5030.5    0.06       0
#XS Ineff=2,0
    0.00 4924.00  771.70 5076.00    0.00  771.70
Permanent Ineff=
       F       F
Bank Sta=4948.2,5030.5
XS Rating Curve= 0
Exp/Cntr=0.5,0.3

Type RM Length L Ch R =3,1300,,,
BEGIN DESCRIPTION:
Hunting Creek Rd - TOR
Structure ID: LDS_NLHC_01
Approximate Survey Structure
END DESCRIPTION:
Bridge Culvert--1,0,-1,-1,0
Deck Dist Width WeirC Skew NumUp NumDn MinLoCord MaxHiCord MaxSubmerge Is_Ogee
47.5,13,3,,12,12,,,,0,1,1,,,
  4738.7  4842.9  4902.6  4918.8  4934.0  4934.0  5066.0  5066.0  5113.9  5144.5
  5202.8  5362.7
  775.39  774.54  772.70  771.70  771.70  771.70  771.70  771.70  771.70  772.52
  775.31  789.98
  732.10  732.10  732.10  732.10  732.10  769.70  769.70  732.10  732.10  732.10
  732.10  732.10
  4738.7  4842.9  4902.6  4918.8  4934.0  4934.0  5066.0  5066.0  5113.9  5144.5
  5202.8  5362.7
  775.39  774.54  772.70  771.70  771.70  771.70  771.70  771.70  771.70  772.52
  775.31  789.98
  732.10  732.10  732.10  732.10  732.10  769.70  769.70  732.10  732.10  732.10
  732.10  732.10
Pier Skew, UpSta & Num, DnSta & Num=,4956,2,4956,2,0,0,0,0,0
       1       1
  756.73  769.70
       1       1
  752.77  769.70
Pier Skew, UpSta & Num, DnSta & Num=,5000,2,5000,2,0,0,0,0,0
       1       1
  752.10  769.70
       1       1
  751.85  769.70
Pier Skew, UpSta & Num, DnSta & Num=,5044,2,5044,2,0,0,0,0,0
       1       1
  763.92  769.70
       1       1
  763.51  769.70
BR Coef=1,1,0,1.25,0,,,0.8,0,2,0,
WSPro=,,,, 1 ,,,, 0 ,,,, 0 ,,,,-1 ,-1 ,-1 , 0 , 0 , 0 , 0 , 0
BC Design=,,0,,0,,,,,,

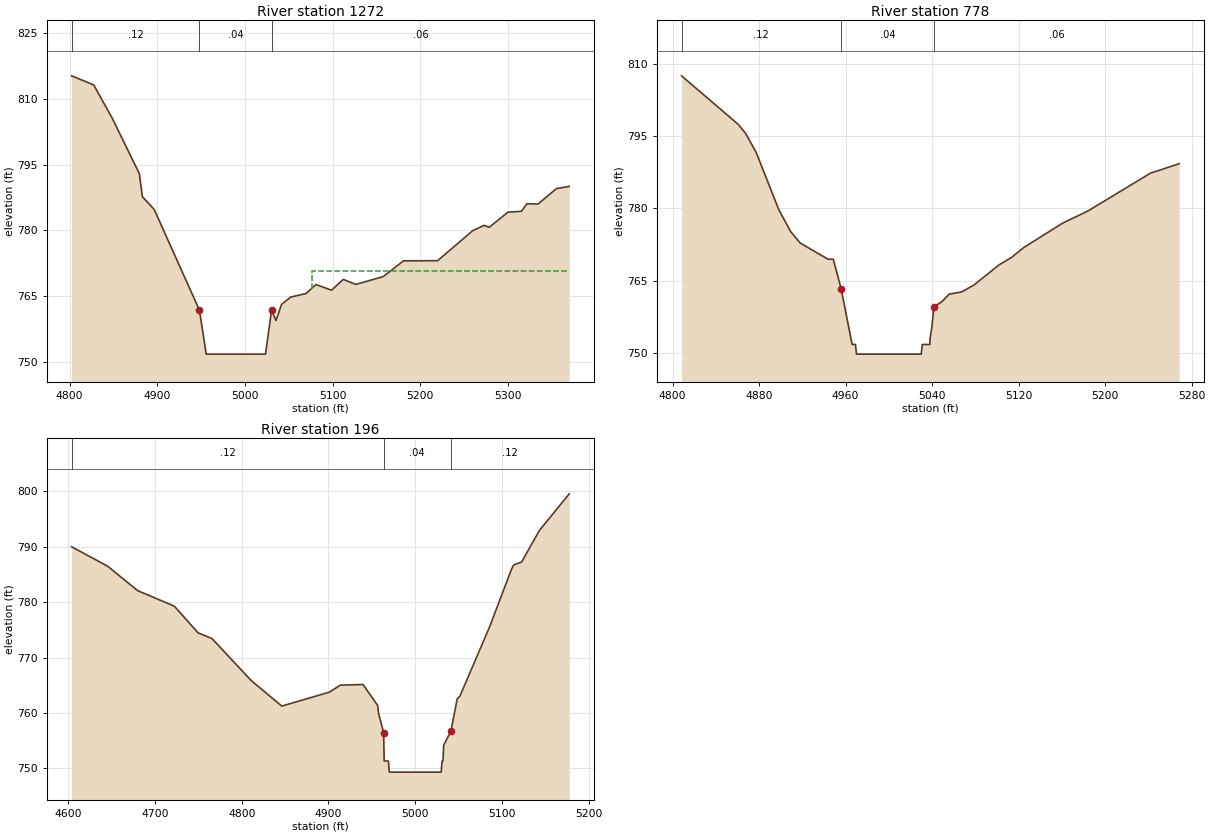
Type RM Length L Ch R = 1,1272,494,494,494
BEGIN DESCRIPTION:
Hunting Creek Rd - DS
END DESCRIPTION:
XS GIS Cut Line= 5
      1477651.43       831027.94      1477516.76       831000.21
      1477459.31       830827.87      1477417.71       830738.73
      1477304.82       830639.70
#Sta/Elev= 30
  4802.3  815.21  4827.6  813.14  4848.6  805.60  4879.6  792.96  4883.1  787.70
  4896.6  784.78  4948.2  761.85  4955.9  751.85  5023.5  751.85  5030.5  761.85
  5035.5  759.50  5041.8  763.16  5052.3  764.84  5069.7  765.64  5081.1  767.69
  5098.9  766.41  5112.2  768.86  5126.6  767.72  5157.9  769.51  5180.9  773.09
  5219.8  773.12  5260.0  779.98  5272.8  781.16  5278.8  780.74  5300.1  784.17
  5315.5  784.36  5321.7  786.09  5334.4  786.02  5355.3  789.53  5370.0  790.04
#Mann=3,-1,0
  4802.3    0.12       0  4948.2    0.04       0  5030.5    0.06       0
#XS Ineff=2,0
    0.00 4924.00  770.70 5076.00    0.00  770.70
Permanent Ineff=
       F       F
Bank Sta=4948.2,5030.5
XS Rating Curve= 0
Exp/Cntr=0.5,0.3

Type RM Length L Ch R = 1,778,582,582,582
BEGIN DESCRIPTION:
North Little Hunting Creek 2.0
END DESCRIPTION:
XS GIS Cut Line= 4
      1477693.09       830512.91      1477534.58       830467.34
      1477481.10       830477.24      1477275.07       830602.05
#Sta/Elev= 30
  4808.3  807.51  4860.8  797.43  4867.5  795.58  4877.2  791.68  4898.2  779.78
  4909.1  775.24  4917.9  772.86  4943.6  769.50  4948.6  769.48  4955.9  763.32
  4966.0  751.83  4969.1  751.80  4970.1  749.80  5029.9  749.80  5030.9  751.80
  5037.9  751.80  5038.1  752.99  5039.8  755.51  5041.7  759.64  5048.7  760.62
  5055.8  762.24  5067.4  762.71  5078.8  764.15  5102.0  768.33  5113.3  769.83
  5124.4  771.86  5160.8  776.98  5184.0  779.47  5241.9  787.33  5268.5  789.29
#Mann=3,-1,0
  4808.3    0.12       0  4955.9    0.04       0  5041.7    0.06       0
Bank Sta=4955.9,5041.7
XS Rating Curve= 0
Exp/Cntr=0.3,0.1

Type RM Length L Ch R = 1,196,0,0,0
BEGIN DESCRIPTION:
North Little Hunting Creek 1.0
END DESCRIPTION:
XS GIS Cut Line= 4
      1477685.13       830253.39      1477649.48       830049.37
      1477508.83       829888.91      1477356.35       829875.05
#Sta/Elev= 30
  4603.9  790.01  4645.5  786.49  4680.2  782.07  4722.4  779.27  4749.6  774.47
  4765.8  773.42  4811.0  765.83  4846.2  761.23  4901.0  763.74  4913.7  765.01
  4939.8  765.12  4956.7  761.34  4957.7  759.94  4963.6  756.41  4964.2  751.33
  4969.1  751.30  4970.1  749.30  5029.9  749.30  5030.9  751.30  5032.0  751.30
  5032.8  754.16  5041.1  756.68  5048.4  762.55  5051.4  762.99  5085.7  775.53
  5110.8  785.88  5113.5  786.72  5122.7  787.25  5143.1  792.95  5177.5  799.56
#Mann=3,-1,0
  4603.9    0.12       0  4963.6    0.04       0  5041.1    0.12       0
Bank Sta=4963.6,5041.1
XS Rating Curve= 0
Exp/Cntr=0.3,0.1

Chan Stop Cuts=-1